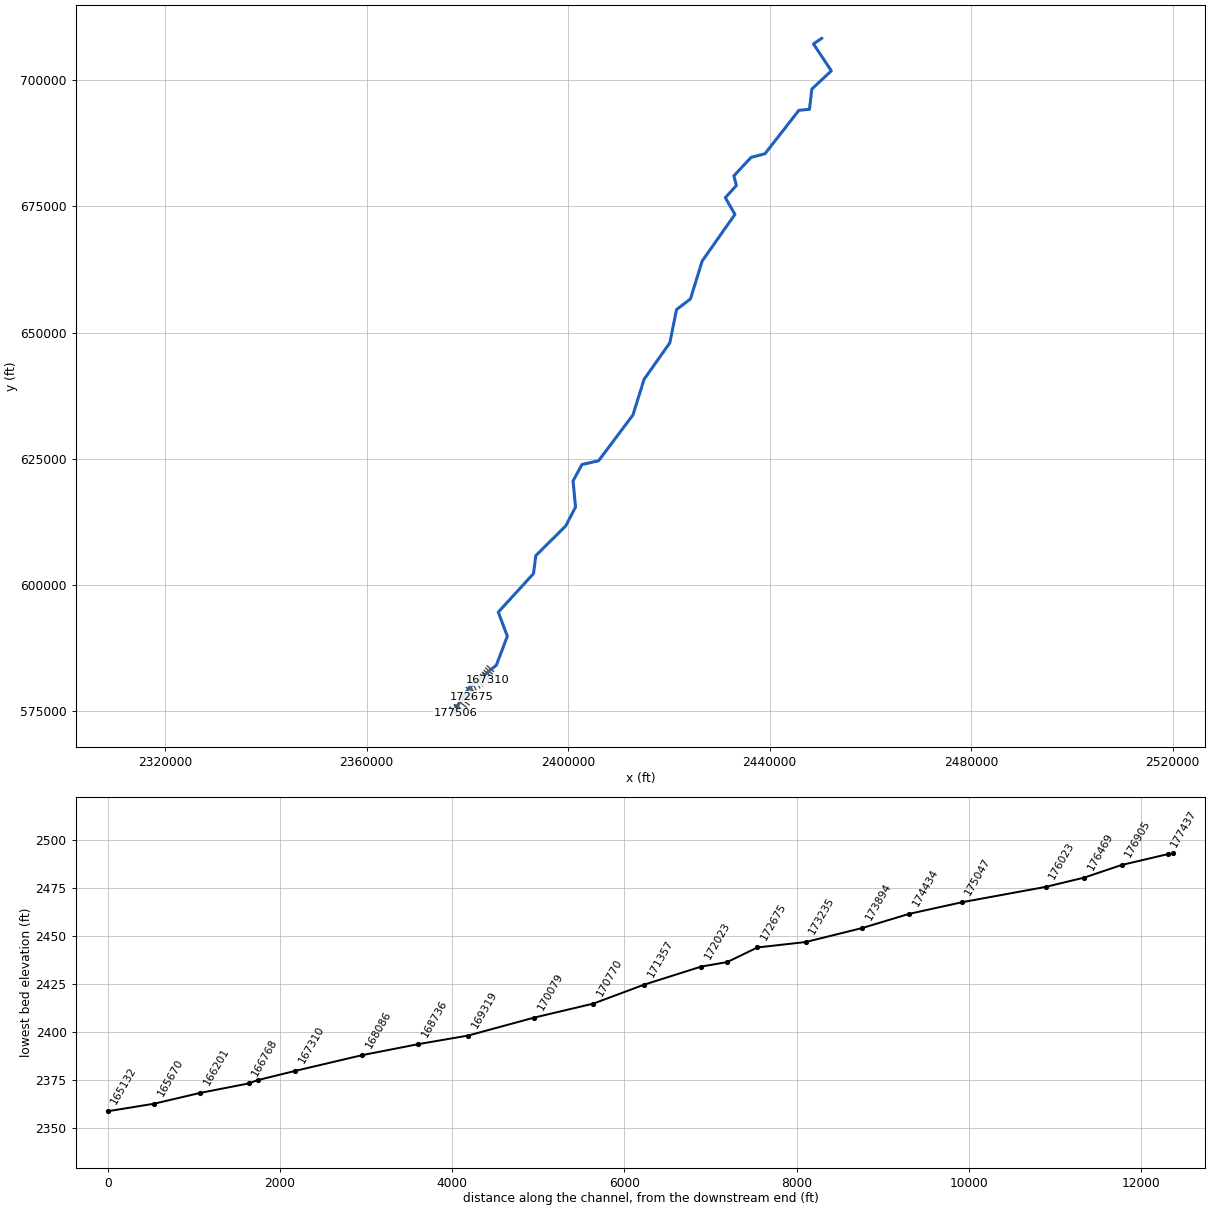
--- NFSBPOTOMC.prj (project) ---

Proj Title=NFSBPOTOMC
Current Plan=p01
Default Exp/Contr=0,0
English Units
Geom File=g01
Flow File=f01
Plan File=p01
BEGIN DESCRIPTION:
Stream Name: North Fork South Branch Potomac River
Flod Zone: Zone A
Pendleton County, WV
WVDHSEM Flood Warning & Analysis Mapping
HEC-RAS Version 5.0.7
Hydrology Method: Gage-weighted regression
Model Notes:
END DESCRIPTION:
DSS Export Rating Curves= 0
DSS Export Rating Curve Sorted= 0
DSS Export Volume Flow Curves= 0
DXF OffsetX= 0
DXF OffsetY= 0
DXF ScaleX= 0
DXF ScaleY= 0

--- NFSBPOTOMC.p01 (plan) ---

Plan Title=Floodplain
Program Version=5.07
Short Identifier=Floodplain
Geom File=g01
Flow File=f01
Subcritical Flow
K Sum by GR= 0
Std Step Tol= 0.01
Critical Tol= 0.01
Num of Std Step Trials= 20
Max Error Tol= 0.3
Flow Tol Ratio= 0.001
Split Flow NTrial= 30
Split Flow Tol= 0.02
Split Flow Ratio= 0.02
Log Output Level= 0
Friction Slope Method= 1
Unsteady Friction Slope Method= 2
Unsteady Bridges Friction Slope Method= 1
Parabolic Critical Depth
Global Vel Dist= 0 , 0 , 0
Global Log Level= 0
CheckData=False
Encroach Param=-1 ,0,0, 0
Mapping Interval=1HOUR
Computation Time Step Use Courant=        0
Computation Time Step Use Time Series=    0
Computation Time Step Count To Double=0
Computation Time Step Max Doubling=0
Computation Time Step Max Halving=0
Computation Time Step Residence Courant=0
Run HTab= 0
Run UNet= 0
Run Sediment= 0
Run PostProcess= 0
Run WQNet= 0
Run RASMapper= 0
UNET Theta= 0
UNET Theta Warmup= 0
UNET ZTol= 0
UNET ZSATol= 0
UNET MxIter= 0
UNET Max Iter WO Improvement= 0
UNET MaxInSteps= 0
UNET DtIC= 0
UNET DtMin= 0
UNET MaxCRTS= 0
UNET WFStab= 0
UNET SFStab= 0
UNET WFX= 1
UNET SFX= 1
UNET 1D Methodology=Finite Difference
UNET DSS MLevel= 1
UNET Pardiso=0
UNET DZMax Abort= 0
UNET Use Existing IB Tables= 0
UNET Froude Reduction=False
UNET Froude Limit= 0
UNET Froude Power= 0
UNET D1 Cores= 0
UNET D2 Coriolis=0
UNET D2 Cores= 0
UNET D2 Theta= 1
UNET D2 Theta Warmup= 1
UNET D2 Z Tol= 0.01
UNET D2 Volume Tol= 0.01
UNET D2 Max Iterations= 20
UNET D2 Equation= 0
UNET D2 RampUpFraction=0.1
UNET D2 TimeSlices= 1
UNET D2 BCVolumeCheck=0
UNET D1D2 MaxIter= 0
UNET D1D2 ZTol=0.01
UNET D1D2 QTol=0.1
UNET D1D2 MinQTol=1
Write IC File= 0
Write IC File at Fixed DateTime=0
Write IC File at Sim End=0
Echo Input=False
Echo Parameters=False
Echo Output=False
Write Detailed= 0
HDF Write Warmup=0
HDF Write Time Slices=0
HDF Flush=0
HDF Face Node Velocities=0
HDF Compression= 1
HDF Chunk Size= 1
HDF Spatial Parts= 1
HDF Use Max Rows=0
HDF Fixed Rows= 1
Calibration Method= 0
Calibration Iterations= 20
Calibration Max Change=0.05
Calibration Tolerance=0.2
Calibration Maximum=1.5
Calibration Minimum=0.5
Calibration Optimization Method= 1
WQ AD Non Conservative
WQ ULTIMATE=-1
WQ Max Comp Step=1HOUR
WQ Output Interval=15MIN
WQ Output Selected Increments= 0
WQ Output face flow=0
WQ Output face velocity=0
WQ Output face area=0
WQ Output face dispersion=0
WQ Output cell volume=0
WQ Output cell surface area=0
WQ Output cell continuity=0
WQ Output cumulative cell continuity=0
WQ Output face conc=0
WQ Output face dconc_dx=0
WQ Output face courant=0
WQ Output face peclet=0
WQ Output face adv mass=0
WQ Output face disp mass=0
WQ Output cell mass=0
WQ Output cell source sink temp=0
WQ Output nsm pathways=0
WQ Output nsm derived pathways=0
WQ Output MaxMinRange=-1
WQ Daily Max Min Mean=-1
WQ Daily Range=0
WQ Daily Time=0
WQ Create Restart=0
WQ Fixed Restart=0
WQ System Summary=0
WQ Write To DSS=0
WQ Use Fixed Temperature=0
Sorting and Armoring Iterations= 10
XS Update Threshold= 0.02
Bed Roughness Predictor= 0
Hydraulics Update Threshold= 0.02
Energy Slope Method= 1
Volume Change Method= 1
Sediment Retention Method= 0
XS Weighting Method= 0
Number of US Weighted Cross Sections= 1
Number of DS Weighted Cross Sections= 1
Upstream XS Weight=0
Main XS Weight=1
Downstream XS Weight=0
Number of DS XS's Weighted with US Boundary= 1
Upstream Boundary Weight= 1
Weight of XSs Associated with US Boundary= 0
Number of US XS's Weighted with DS Boundary= 1
Downstream Boundary Weight= 0.5
Weight of XSs Associated with DS Boundary= 0.5
Percentile Method= 0
Sediment Output Level= 3
Mass or Volume Output= 0
Output Increment Type= 1
Profile and TS Output Increment= 1
XS Output Flag= 0
XS Output Increment= 10
Write Gradation File= 0
Read Gradation Hotstart= 0
Write HDF5 File= 1
Write Binary Output= 1
Write DSS Sediment File= 0
SV Curve= 0
Specific Gage Flag= 0

--- NFSBPOTOMC.f01 (steady flow) ---

Flow Title=Flows
Program Version=5.07
Number of Profiles= 6
Profile Names=P100yr,P10yr,P25yr,P50yr,P500yr,P101yr
River Rch & RM=NFSBPOTOMC,Main            ,177506
    9063    4066    5858    7410   13675   11030
River Rch & RM=NFSBPOTOMC,Main            ,152672
   10643    4763    6870    8697   16086   12953
River Rch & RM=NFSBPOTOMC,Main            ,144390
   16497    7334   10610   13459   25049   20077
River Rch & RM=NFSBPOTOMC,Main            ,128549
   18384    8159   11814   14994   27946   22374
River Rch & RM=NFSBPOTOMC,Main            ,109301
   24977   10346   15212   19806   41944   30860
River Rch & RM=NFSBPOTOMC,Main            ,106401
   27857   11574   16992   22090   46634   34418
River Rch & RM=NFSBPOTOMC,Main            ,82086
   31023   12930   18952   24601   51776   38331
River Rch & RM=NFSBPOTOMC,Main            ,51917
   42983   18082   26382   34086   71072   53109
Boundary for River Rch & Prof#=NFSBPOTOMC,Main            , 1
Up Type= 0
Dn Type= 3
Dn Slope=0.00563
Boundary for River Rch & Prof#=NFSBPOTOMC,Main            , 2
Up Type= 0
Dn Type= 3
Dn Slope=0.00563
Boundary for River Rch & Prof#=NFSBPOTOMC,Main            , 3
Up Type= 0
Dn Type= 3
Dn Slope=0.00563
Boundary for River Rch & Prof#=NFSBPOTOMC,Main            , 4
Up Type= 0
Dn Type= 3
Dn Slope=0.00563
Boundary for River Rch & Prof#=NFSBPOTOMC,Main            , 5
Up Type= 0
Dn Type= 3
Dn Slope=0.00563
Boundary for River Rch & Prof#=NFSBPOTOMC,Main            , 6
Up Type= 0
Dn Type= 3
Dn Slope=0.00563
DSS Import GetInterval= 0
DSS Import GetPeak= 0
DSS Import FillOption= 0

--- NFSBPOTOMC.g01 (geometry) ---

Geom Title=Geometry
Program Version=5.07

River Reach=NFSBPOTOMC      ,Main
Reach XY= 30
2377271.78320184574993.7860388762380384.36031002579708.064011872
2385754.65862453584169.9842218762387931.08143702 589889.17947638
2386124.70578468594656.752290294 2393126.0343017602292.692070872
2393578.99468187605841.7095791252399506.12095094 611717.30609563
2401461.52419236 615465.934425132400978.54057828620637.049410954
2402740.19945651623889.5950712112406035.54654035624633.893779457
2412854.64149794 633688.910774382415080.38507795640780.753874123
2420182.84403309 647993.790301042421517.52410653654578.249244958
2424275.25087452 656690.640033292426605.57495403664197.556777954
2433109.80538386673431.7784669552431203.84003568676738.113061622
2433395.79890636 679156.209275292432899.73690635681067.971527874
2436315.13952437684717.1929039662439079.73012379685444.159953967
2445794.24687845694039.4685507122447909.18556196694248.448119625
2448371.87754995698247.5346096312452251.80843836701862.288863048
2448699.42282662707185.8966541292450318.37857819 708300.67460829

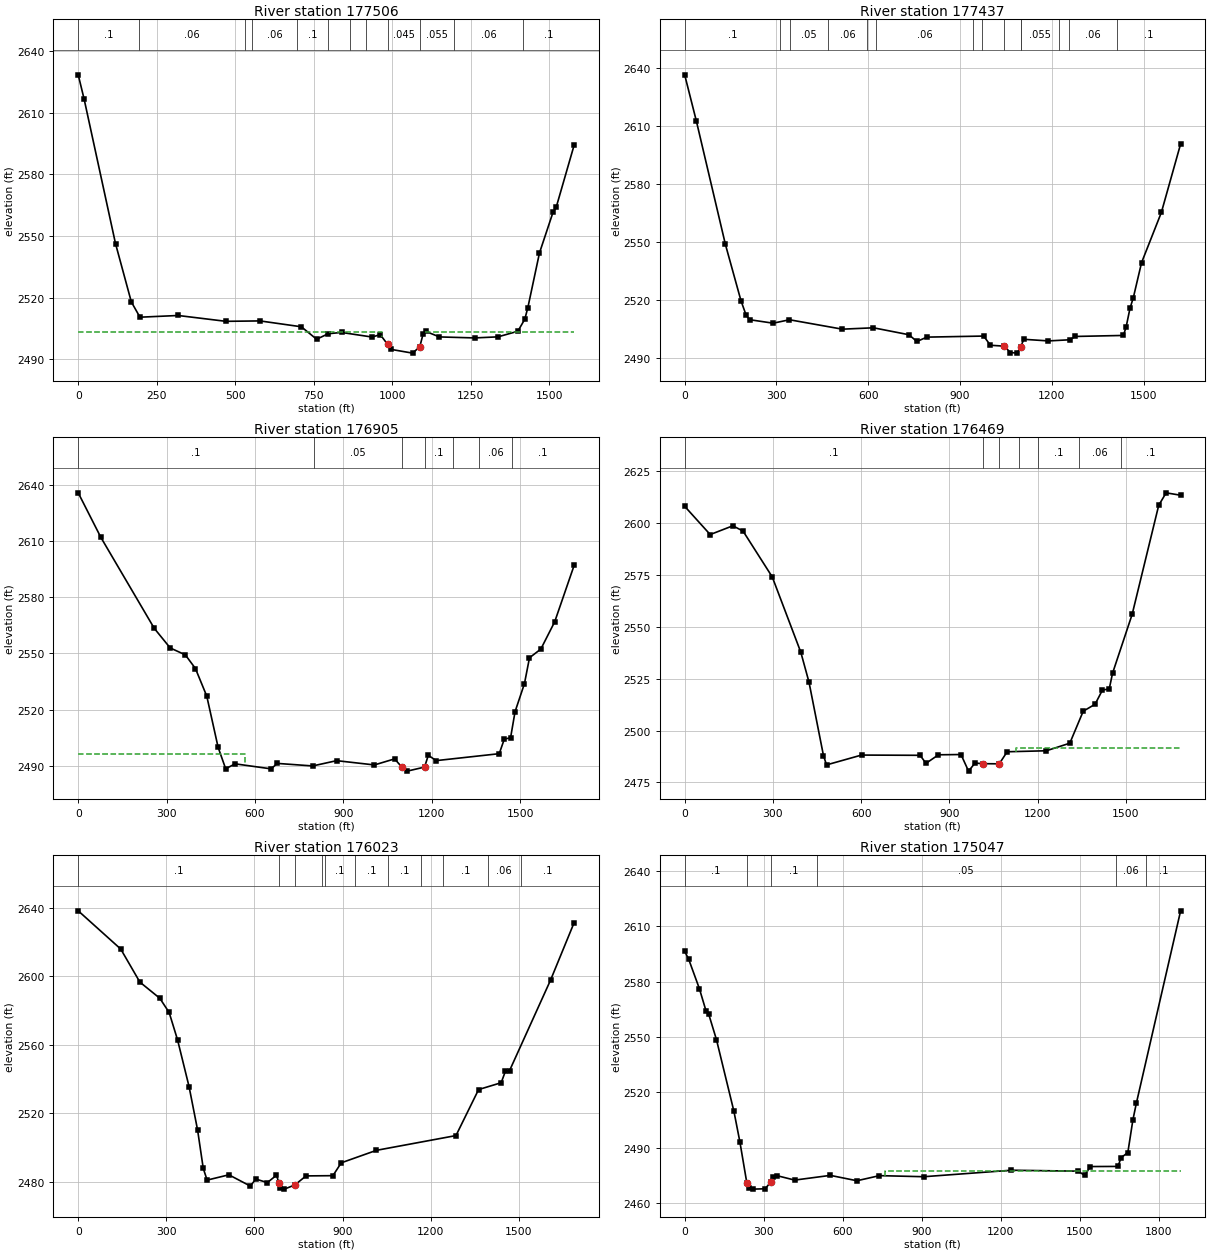
Type RM Length L Ch R = 1 ,177506  ,101.8,68.7,67.2
XS GIS Cut Line= 3
2376513.84377286575736.1618507062377340.31029576574926.666094378
2377618.04432034574607.566338882
#Sta/Elev= 30
       0 2628.48      19 2616.55   118.8 2546.39   169.2 2518.01   196.7 2510.57
   318.3  2511.4   470.6 2508.56   579.2 2508.76   710.7 2505.91   759.6 2499.85
   796.4 2502.53   838.8 2503.15   936.3 2500.91   962.2  2502.1  985.332497.395
   996.5 2494.91  1065.1 2493.09 1088.132496.172    1099 2502.59  1107.5 2503.64
  1150.8 2500.97  1262.6 2500.49    1337    2501  1400.5 2503.73  1422.6 2509.58
  1432.3 2515.16  1469.4 2541.81  1512.8 2561.73  1522.5 2563.94  1579.9 2594.31
#Mann= 12 ,-1 , 0
       0      .1       0  194.52     .06       0  529.84     .05       0
  552.26     .06       0   697.5      .1       0  795.33     .06       0
  865.15     .05       0  916.86    .055       0  985.33    .045       0
 1088.13    .055       0 1196.22     .06       0  1418.5      .1       0
#XS Ineff= 2 , 0
             967  2503.6    1106          2503.6
Permanent Ineff=
       F       F
Bank Sta=985.33,1088.13
XS Rating Curve= 0 ,0
Exp/Cntr=0.5,0.3

Type RM Length L Ch R = 1 ,177437  ,542.6,532.3,521.6
XS GIS Cut Line= 3
2376606.51123843575802.7663763022377459.91668385574884.335470378
2377706.50641379 574612.29926905
#Sta/Elev= 30
       0 2636.49    38.1 2612.66   133.1 2548.85     184 2519.75     201  2512.2
   212.8 2509.93   289.2 2508.14   342.5 2509.92   515.2 2505.05   617.1 2505.76
   733.1 2502.17   758.8 2498.68   791.6 2500.94   977.2 2501.49   999.3 2496.74
 1044.172496.275  1064.6 2492.99  1086.4 2492.67 1098.542495.984  1108.3 2499.82
  1188.8 2498.98  1257.9 2499.56  1277.3 2501.29  1433.8 2501.81  1442.6 2506.05
  1455.4  2515.8  1466.4 2521.38  1493.2 2539.41    1558 2565.39  1620.9 2600.78
#Mann= 15 ,-1 , 0
       0      .1       0  311.96     .06       0  343.62     .05       0
  469.43     .06       0  595.31     .05       0  626.91     .06       0
  941.86    .055       0  972.86     .06       0 1044.17    .045       0
 1098.54     .06       0 1098.71     .05       0 1099.33    .055       0
 1224.56      .1       0 1256.76     .06       0 1411.82      .1       0
Bank Sta=1044.17,1098.54
XS Rating Curve= 0 ,0
Exp/Cntr=0.5,0.3

Type RM Length L Ch R = 1 ,176905  ,421.3,435.8,445
XS GIS Cut Line= 2
2377421.48204944 576282.770993712378019.88898912574709.182933539
#Sta/Elev= 30
       0 2635.93    76.9 2612.08   258.2 2563.43   312.3 2552.95   363.7 2549.24
   397.9 2541.95   436.4 2527.17   474.9  2499.8   500.6 2488.31   532.5 2490.96
   654.6 2488.28     676 2491.19   795.9 2489.83   877.2 2492.66  1005.5 2490.37
    1074 2493.61  1099.72489.013  1116.8 2487.06 1175.672489.222  1188.4 2495.53
  1215.2 2492.68  1429.2 2496.39  1446.3 2504.15  1467.7 2504.94  1482.9 2518.86
  1514.8 2533.88  1531.9  2547.7  1570.4 2552.35  1617.5 2566.96  1683.5 2597.15
#Mann= 7 ,-1 , 0
       0      .1       0  799.95     .05       0  1099.7    .045       0
 1175.67      .1       0 1270.88      .1       0 1361.09     .06       0
 1473.31      .1       0
#XS Ineff= 2 , 0
          565.74 2496.28
Permanent Ineff=
       F       F
Bank Sta=1099.7,1175.67
XS Rating Curve= 0 ,0
Exp/Cntr=0.3,0.1

Type RM Length L Ch R = 1 ,176469  ,438.5,446.1,452.7
XS GIS Cut Line= 3
2377498.01765752576273.5951590392378216.85250595575410.271754459
2378560.87379953574964.471793041
#Sta/Elev= 30
       0 2608.07    86.8 2594.46   163.7 2598.68   198.4 2596.15   297.8 2574.05
     395 2537.72   422.8 2523.32     472 2487.94   482.4 2483.47   601.3 2488.21
   800.5 2488.09   820.7 2484.23     863 2488.34   939.7 2488.47   965.3 2480.47
   987.3 2484.36 1014.092484.059 1069.742483.988  1096.6  2489.8  1229.8 2490.28
  1309.7 2493.93  1355.3 2509.35  1395.5 2512.68  1420.7 2519.54  1443.7 2520.07
  1455.1 2527.67  1521.8 2556.07    1612 2608.55  1637.2 2614.57  1686.5 2613.41
#Mann= 7 ,-1 , 0
       0      .1       0 1014.09    .045       0 1069.74      .1       0
 1136.07      .1       0 1199.97      .1       0 1341.63     .06       0
  1483.3      .1       0
#XS Ineff= 2 , 0
                         1127.42         2491.61
Permanent Ineff=
       F       F
Bank Sta=1014.09,1069.74
XS Rating Curve= 0 ,0
Exp/Cntr=0.3,0.1

Type RM Length L Ch R = 1 ,176023  ,982.9,975.9,962.8
XS GIS Cut Line= 3
2377711.16814986576297.3621718732378371.23933628575846.268585876
 2379074.4833366575302.126957625
#Sta/Elev= 30
       0 2638.35   144.8    2616     210 2596.67   277.8 2587.23   309.6 2578.93
   338.2 2562.94   377.4 2535.61   406.5 2510.19   425.8 2487.75   438.9 2480.92
     513 2484.01   585.7 2477.47   605.1 2481.51   643.9 2479.45   674.9 2483.74
  683.562479.331   687.5 2476.27     702 2475.64  738.012478.119   775.7 2483.37
   867.3 2483.51   895.6 2491.02  1015.4 2498.32  1286.3 2506.95  1363.3 2533.85
  1440.2 2537.85  1454.5  2544.5  1468.8 2544.94  1608.5 2597.91  1688.7 2631.47
#Mann= 11 ,-1 , 0
       0      .1       0  683.56    .045       0  738.01      .1       0
  829.02      .1       0  840.07      .1       0  942.06      .1       0
  1055.1      .1       0 1168.13     .05       0 1243.72      .1       0
  1394.2     .06       0 1507.24      .1       0
Bank Sta=683.56,738.01
XS Rating Curve= 0 ,0
Exp/Cntr=0.3,0.1

Type RM Length L Ch R = 1 ,175047  ,610.3,613.2,616.1
XS GIS Cut Line= 2
2378339.01302278 576977.659367712379816.21971402575810.662029788
#Sta/Elev= 30
       0 2596.35      15 2592.13    55.7  2576.2    81.2    2564    91.4 2562.26
   120.6 2548.55   186.9 2509.74   209.7 2493.09  235.822471.057   244.3 2468.34
   258.1 2467.61   305.5  2467.8  327.752471.644   333.6 2473.91   352.1 2474.84
   417.6  2472.5   552.9 2475.05   653.9 2472.15   739.4 2474.91   907.8 2474.33
  1240.6 2477.84  1493.3 2477.34  1518.7 2475.05  1539.6 2479.83    1645  2479.9
  1656.3 2484.62  1682.2 2487.39  1701.5 2505.15  1714.4    2514  1882.6 2618.27
#Mann= 6 ,-1 , 0
       0      .1       0  235.82    .045       0  327.75      .1       0
   500.7     .05       0 1637.35     .06       0 1751.01      .1       0
#XS Ineff= 1 ,-1
  759.75 1882.56 2477.49
Permanent Ineff=
       F
Bank Sta=235.82,327.75
XS Rating Curve= 0 ,0
Exp/Cntr=0.3,0.1

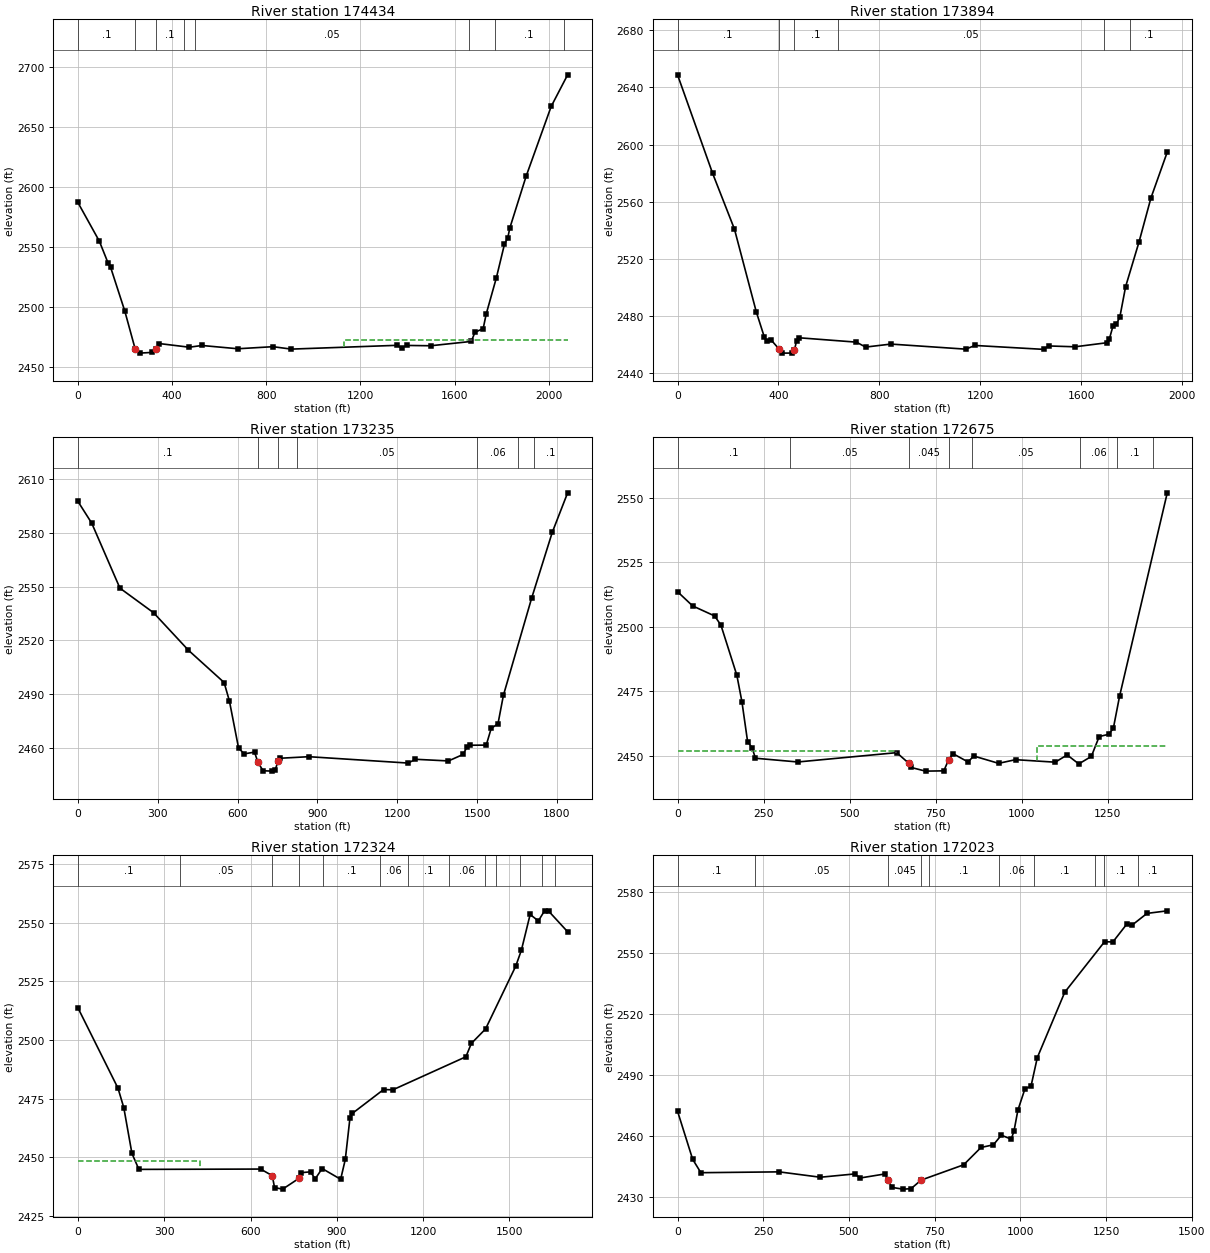
Type RM Length L Ch R = 1 ,174434  ,538.7,540.6,543.5
XS GIS Cut Line= 2
 2378653.7341781 577482.746940212380363.85050851576298.690581292
#Sta/Elev= 30
       0 2587.21    91.1 2554.91   127.7 2536.92   138.6 2533.34     199 2496.72
  243.532464.799   262.2 2461.53     314 2462.12  331.372465.322   344.1 2469.55
   473.2 2466.46   526.7 2467.91   679.1 2465.18   828.6  2466.9   906.2 2464.88
  1353.8 2468.03  1374.8    2466  1398.1 2467.94  1498.4 2467.68  1670.9 2471.29
  1686.2 2478.88  1721.3 2482.01  1734.1 2494.11  1777.2 2524.29  1811.7 2552.38
  1825.7 2557.75  1834.7 2566.06  1903.5 2608.99  2010.1 2667.35    2080 2693.73
#Mann= 8 ,-1 , 0
       0      .1       0  243.53    .045       0  331.37      .1       0
  450.14      .1       0  497.81     .05       0 1660.43     .06       0
 1770.46      .1       0 2062.83      .1       0
#XS Ineff= 2 , 0
                         1130.58          2472.3
Permanent Ineff=
       F       F
Bank Sta=243.53,331.37
XS Rating Curve= 0 ,0
Exp/Cntr=0.3,0.1

Type RM Length L Ch R = 1 ,173894  ,657.9,658.2,644.1
XS GIS Cut Line= 2
 2378836.9998877577957.9274202882380539.59523577577023.740640372
#Sta/Elev= 30
       0 2648.79     139 2579.94   225.6 2540.96   312.2 2483.12   344.2 2465.43
   353.3 2462.51   371.8 2463.26  401.872457.188   412.6  2454.2   454.3 2454.24
  463.532456.212   471.9 2462.82   480.8 2464.95   709.2 2461.88   745.9 2458.43
   846.2 2460.53  1142.6 2456.98  1179.5 2459.56  1453.2 2456.81  1471.1 2459.22
  1576.1 2458.63  1703.8 2461.49  1712.2 2463.97  1726.6 2473.04  1740.3 2474.54
    1754 2479.45  1776.8 2500.65  1830.1 2531.98  1877.2 2562.66    1942 2594.79
#Mann= 6 ,-1 , 0
       0      .1       0  401.87    .045       0  463.53      .1       0
  636.09     .05       0 1689.98     .06       0 1795.37      .1       0
Bank Sta=401.87,463.53
XS Rating Curve= 0 ,0
Exp/Cntr=0.3,0.1

Type RM Length L Ch R = 1 ,173235  ,537.8,560.1,581.5
XS GIS Cut Line= 4
2379230.11425895578339.2895184612379692.87251976578065.546299547
2379894.16378385577857.0083307922380777.18039054577360.915490955
#Sta/Elev= 30
       0 2597.75    51.9 2585.59   157.9 2549.23   284.2 2535.49   415.4 2514.49
   549.4 2496.45   569.2 2486.19   603.7 2459.83   624.7 2456.52   663.7 2457.52
  676.63 2451.75   695.9 2447.09   730.4 2446.88   741.5 2447.57  752.062452.412
   759.2 2454.08   867.7 2454.95  1240.8 2451.39  1268.6  2453.5  1392.5 2452.58
  1447.6 2456.22  1461.3 2460.22  1475.1 2461.36  1534.5 2461.44  1553.1  2470.8
  1578.6 2473.38    1599  2489.3  1704.9 2543.56  1782.5 2580.41  1840.3 2602.54
#Mann= 7 ,-1 , 0
       0      .1       0  676.63    .045       0  752.06      .1       0
  822.99     .05       0 1500.85     .06       0 1655.46      .1       0
 1712.39      .1       0
Bank Sta=676.63,752.06
XS Rating Curve= 0 ,0
Exp/Cntr=0.3,0.1

Type RM Length L Ch R = 1 ,172675  ,330.2,351.3,376.6
XS GIS Cut Line= 2
2379632.22106627578562.163744628 2380880.2356306577879.282236382
#Sta/Elev= 30
       0 2513.66    43.9 2508.14   107.7 2504.25     126  2500.7   172.3 2481.24
     187 2471.01   203.5 2455.52   216.5 2453.13   226.3 2449.05   349.4  2447.6
   636.7 2451.22  671.352447.137   677.7  2445.5   720.4 2444.05   773.5 2444.16
  787.242448.376     800 2450.84   844.2 2447.58   860.1 2449.93   932.6 2447.07
   981.8 2448.49  1097.2 2447.52  1131.8 2450.33  1165.6 2446.85  1202.1 2449.76
  1224.9 2457.47  1252.2 2458.32  1265.9 2460.62  1284.1 2473.14  1422.6 2552.01
#Mann= 8 ,-1 , 0
       0      .1       0  327.21     .05       0  671.35    .045       0
  787.24      .1       0  853.94     .05       0 1169.97     .06       0
 1275.32      .1       0 1380.67      .1       0
#XS Ineff= 2 , 0
          635.84 2451.76 1042.85         2453.87
Permanent Ineff=
       F       F
Bank Sta=671.35,787.24
XS Rating Curve= 0 ,0
Exp/Cntr=0.3,0.1

Type RM Length L Ch R = 1 ,172324  ,293.7,300.9,309.2
XS GIS Cut Line= 3
 2379600.4412742578648.4519578812380772.93335178578501.442081288
 2381022.5188106578044.561105296
#Sta/Elev= 30
       0 2513.68   139.4 2479.41   159.5 2471.14   187.8 2451.64     212 2444.83
   635.2 2444.97   675.6 2442.15   683.6 2437.06   711.8 2436.42   768.3    2441
   776.3 2443.43   808.6 2443.79   824.7 2440.76     849 2445.19   913.3 2440.62
   929.5 2449.08   945.7 2466.77   953.7 2468.66  1062.6 2478.85  1094.8 2478.73
  1348.7 2492.81  1367.6 2498.49    1417 2504.66  1521.9 2531.41  1541.6 2538.23
    1572 2553.43  1600.5  2550.7  1622.1 2554.99    1636  2554.9  1702.3 2546.07
#Mann= 13 ,-1 , 0
       0      .1       0   353.9     .05       0   675.6    .045       0
   768.3     .05       0  850.81      .1       0 1049.58     .06       0
 1148.96      .1       0 1290.48     .06       0 1413.39      .1       0
 1452.08     .06       0 1536.29      .1       0 1613.91     .06       0
 1659.19      .1       0
#XS Ineff= 2 , 0
          425.33 2448.49
Permanent Ineff=
       F       F
Bank Sta=675.6,768.3
XS Rating Curve= 0 ,0
Exp/Cntr=0.3,0.1

Type RM Length L Ch R = 1 ,172023  ,693,666.5,651.2
XS GIS Cut Line= 2
2379662.71378744578823.0680784582381089.34085545578902.609914124
#Sta/Elev= 30
       0 2472.35    44.1 2448.74    68.1 2442.16   296.5 2442.57   416.7 2439.93
   516.8 2441.55   532.9 2439.56     605 2441.54  614.642438.588     625 2434.96
   657.1 2434.09   681.1 2434.28  710.432438.508   834.7 2446.03   885.4 2454.55
   921.5 2455.85   944.7 2460.58   973.5 2458.63   981.6 2462.59     993 2472.86
  1013.6 2483.36  1031.2 2484.59  1049.7 2498.69  1129.8  2530.8    1246  2555.6
    1270 2555.44  1310.1 2564.09  1326.1 2563.72  1369.7 2569.49  1428.8 2570.75
#Mann= 10 ,-1 , 0
       0      .1       0  226.11     .05       0  614.64    .045       0
  710.43     .05       0  734.57      .1       0  937.95     .06       0
 1039.64      .1       0 1219.03      .1       0 1243.03      .1       0
 1344.72      .1       0
Bank Sta=614.64,710.43
XS Rating Curve= 0 ,0
Exp/Cntr=0.3,0.1

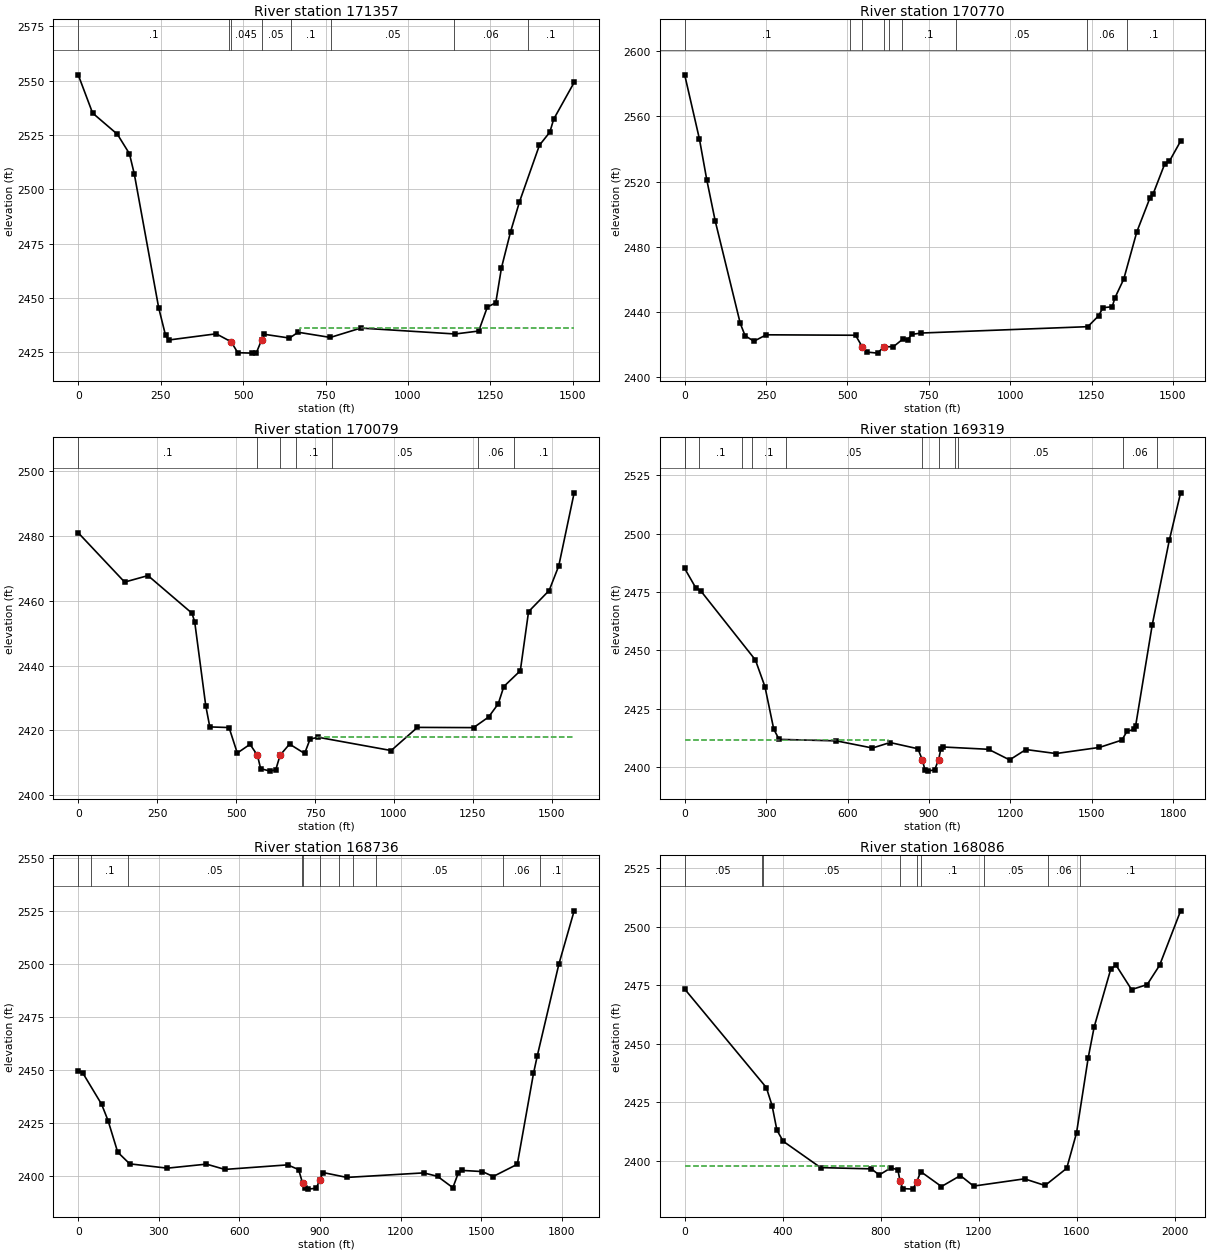
Type RM Length L Ch R = 1 ,171357  ,619.3,586.6,560.7
XS GIS Cut Line= 3
2379782.73749754 579719.08859612 2380468.9588941579422.057694122
2381092.20338252578993.800020456
#Sta/Elev= 30
       0  2552.7    43.6 2535.11   118.8 2525.34   155.3  2516.4     170 2507.12
   244.1 2445.42   264.8  2432.8   274.6 2430.65   418.4  2433.5  463.842429.832
   483.8 2424.81   527.4 2424.61   540.5 2424.86  555.812430.573   564.4 2433.27
   640.7 2431.55   666.9 2434.22   764.5 2431.83   856.7 2436.14    1143 2433.42
  1214.5 2434.78  1240.7 2445.85  1266.2 2447.77  1283.5 2463.89  1311.3 2480.58
  1338.1 2494.23  1398.6  2520.3  1430.2 2526.32  1441.7 2532.25  1503.9 2549.21
#Mann= 8 ,-1 , 0
       0      .1       0  458.42     .05       0  463.84    .045       0
  555.81     .05       0  644.71      .1       0  767.06     .05       0
 1138.34     .06       0 1363.57      .1       0
#XS Ineff= 2 , 0
                          671.15          2436.2
Permanent Ineff=
       F       F
Bank Sta=463.84,555.81
XS Rating Curve= 0 ,0
Exp/Cntr=0.3,0.1

Type RM Length L Ch R = 1 ,170770  ,694.1,690.9,687.3
XS GIS Cut Line= 2
 2380432.0751096580358.9373820422381143.99035245579011.999787211
#Sta/Elev= 30
       0 2585.52    45.3 2546.15    67.9  2521.1    93.8 2495.86   170.7 2433.06
   185.6 2425.44   212.7 2422.09   250.6 2426.02   524.9 2425.75  544.952418.812
   561.1  2415.4   592.7 2414.78   611.82418.633   641.4 2418.76   669.7 2423.31
   685.7 2423.02   696.8 2426.25   727.2 2427.11  1238.4 2431.01  1271.4 2437.64
    1285 2442.68  1313.2  2443.2  1322.1 2448.86  1348.8 2460.21    1389 2489.21
  1428.7  2509.7  1438.8 2512.33    1475 2531.03  1488.6 2532.35  1523.5 2544.85
#Mann= 9 ,-1 , 0
       0      .1       0  507.01     .05       0  544.95    .045       0
   611.8     .05       0  628.64     .06       0  667.69      .1       0
  832.46     .05       0 1236.78     .06       0 1358.41      .1       0
Bank Sta=544.95,611.8
XS Rating Curve= 0 ,0
Exp/Cntr=0.3,0.1

Type RM Length L Ch R = 1 ,170079  ,757.7,760.2,763.8
XS GIS Cut Line= 2
2381059.59813276580738.0222537962381677.60083377579294.077635124
#Sta/Elev= 30
       0 2480.96     147 2465.75     221 2467.75   360.2 2456.15   368.9  2453.5
   403.9 2427.62   416.7 2421.08   477.7 2420.88   503.8 2413.02   544.1 2415.71
  567.512412.339   577.7  2408.2   607.8 2407.44   625.6 2407.86  639.452412.363
   669.3 2415.78     717 2412.88   734.4 2417.35   760.6 2417.87   991.1 2413.79
  1074.2 2420.93  1252.1 2420.86  1299.7 2424.13  1330.2  2428.2  1347.9 2433.54
  1400.1  2438.4  1426.2 2456.63  1491.4 2463.15  1521.9 2470.77  1570.6 2493.28
#Mann= 7 ,-1 , 0
       0      .1       0  567.51    .045       0  639.45     .06       0
  689.78      .1       0  804.79     .05       0 1264.83     .06       0
 1379.84      .1       0
#XS Ineff= 2 , 0
                          755.23         2417.84
Permanent Ineff=
       F       F
Bank Sta=567.51,639.45
XS Rating Curve= 0 ,0
Exp/Cntr=0.3,0.1

Type RM Length L Ch R = 1 ,169319  ,578.9,582.5,586.1
XS GIS Cut Line= 2
2381554.70016095581253.8463533822382452.86142236579662.534247294
#Sta/Elev= 30
       0 2485.05    40.8 2476.76    58.5 2475.55   260.6 2445.81   295.8 2434.34
   328.1 2416.16   347.9 2411.77   559.2 2411.12   691.8 2408.06   756.7 2410.41
   859.5 2407.74  876.152402.748   885.3 2398.65   895.3 2398.15   921.2 2398.72
  935.632403.111   944.1 2407.81   950.5 2408.51  1119.5 2407.51  1197.2 2402.97
  1257.3 2407.41    1368 2405.69  1528.3 2408.32    1611 2411.46  1629.4 2415.17
  1656.9  2416.1  1661.5 2417.53  1722.7 2460.85  1785.5 2497.09  1827.3 2517.48
#Mann= 12 ,-1 , 0
       0     .05       0     .44      .1       0   53.62      .1       0
  212.63      .1       0   248.9      .1       0  371.65     .05       0
  876.15    .045       0  935.63     .05       0   994.3     .06       0
  1007.7     .05       0 1615.47     .06       0  1739.7      .1       0
#XS Ineff= 2 , 0
          749.58 2411.66
Permanent Ineff=
       F       F
Bank Sta=876.15,935.63
XS Rating Curve= 0 ,0
Exp/Cntr=0.3,0.1

Type RM Length L Ch R = 1 ,168736  ,648.2,650.7,653.4
XS GIS Cut Line= 2
2381932.24697801581524.7152342052383036.92390251 580045.25297004
#Sta/Elev= 30
       0  2449.5    17.5 2448.31    87.1 2433.66   111.1 2425.97     147 2411.08
   191.7 2405.56   331.8 2403.53   477.5 2405.43   546.1 2402.93   779.7 2405.08
   820.5 2402.86  835.272396.525   843.3    2394   855.9 2393.64   886.7 2394.07
  899.21  2398.1   911.9 2401.45  1000.3 2399.16  1286.3  2401.3  1337.8 2399.67
  1394.9 2394.31    1415 2401.26  1428.2 2402.47  1504.9 2401.92  1544.8 2399.58
  1634.7 2405.36    1695 2448.19  1709.3  2456.6  1789.4 2499.69  1846.4 2524.89
#Mann= 11 ,-1 , 0
       0    .055       0   47.73      .1       0  187.08     .05       0
  831.95      .1       0  835.27    .045       0  899.21      .1       0
  970.11      .1       0 1023.17      .1       0 1108.28     .05       0
 1580.57     .06       0 1719.92      .1       0
Bank Sta=835.27,899.21
XS Rating Curve= 0 ,0
Exp/Cntr=0.3,0.1

Type RM Length L Ch R = 1 ,168086  ,769.8,775.6,774.8
XS GIS Cut Line= 3
2382355.41443878581926.5293912142383439.00938445580676.753019378
2383647.93547577580371.985584289
#Sta/Elev= 30
       0 2473.43   333.1 2431.34   356.6 2423.63   376.4 2413.09   401.9 2408.37
   554.6 2397.11   761.9 2396.57   793.6 2393.96   841.3    2397   869.8 2396.19
     8792391.253   889.6 2388.15   931.3 2387.91  946.922391.042   963.1  2395.4
  1047.8 2389.02    1125 2393.71  1178.9 2389.21  1386.6 2392.31  1470.5 2389.47
  1558.8 2396.81  1598.8  2411.9  1646.7 2444.15  1670.9 2457.25  1738.5 2481.93
  1759.8 2483.69  1823.4 2473.21  1887.1 2475.34  1937.7 2483.56  2023.6 2506.87
#Mann= 9 ,-1 , 0
       0     .05       0  314.04      .1       0  318.73     .05       0
     879    .045       0  946.92     .05       0  965.68      .1       0
 1219.91     .05       0 1483.25     .06       0 1612.64      .1       0
#XS Ineff= 2 , 0
          829.56 2397.76
Permanent Ineff=
       F       F
Bank Sta=879,946.92
XS Rating Curve= 0 ,0
Exp/Cntr=0.3,0.1

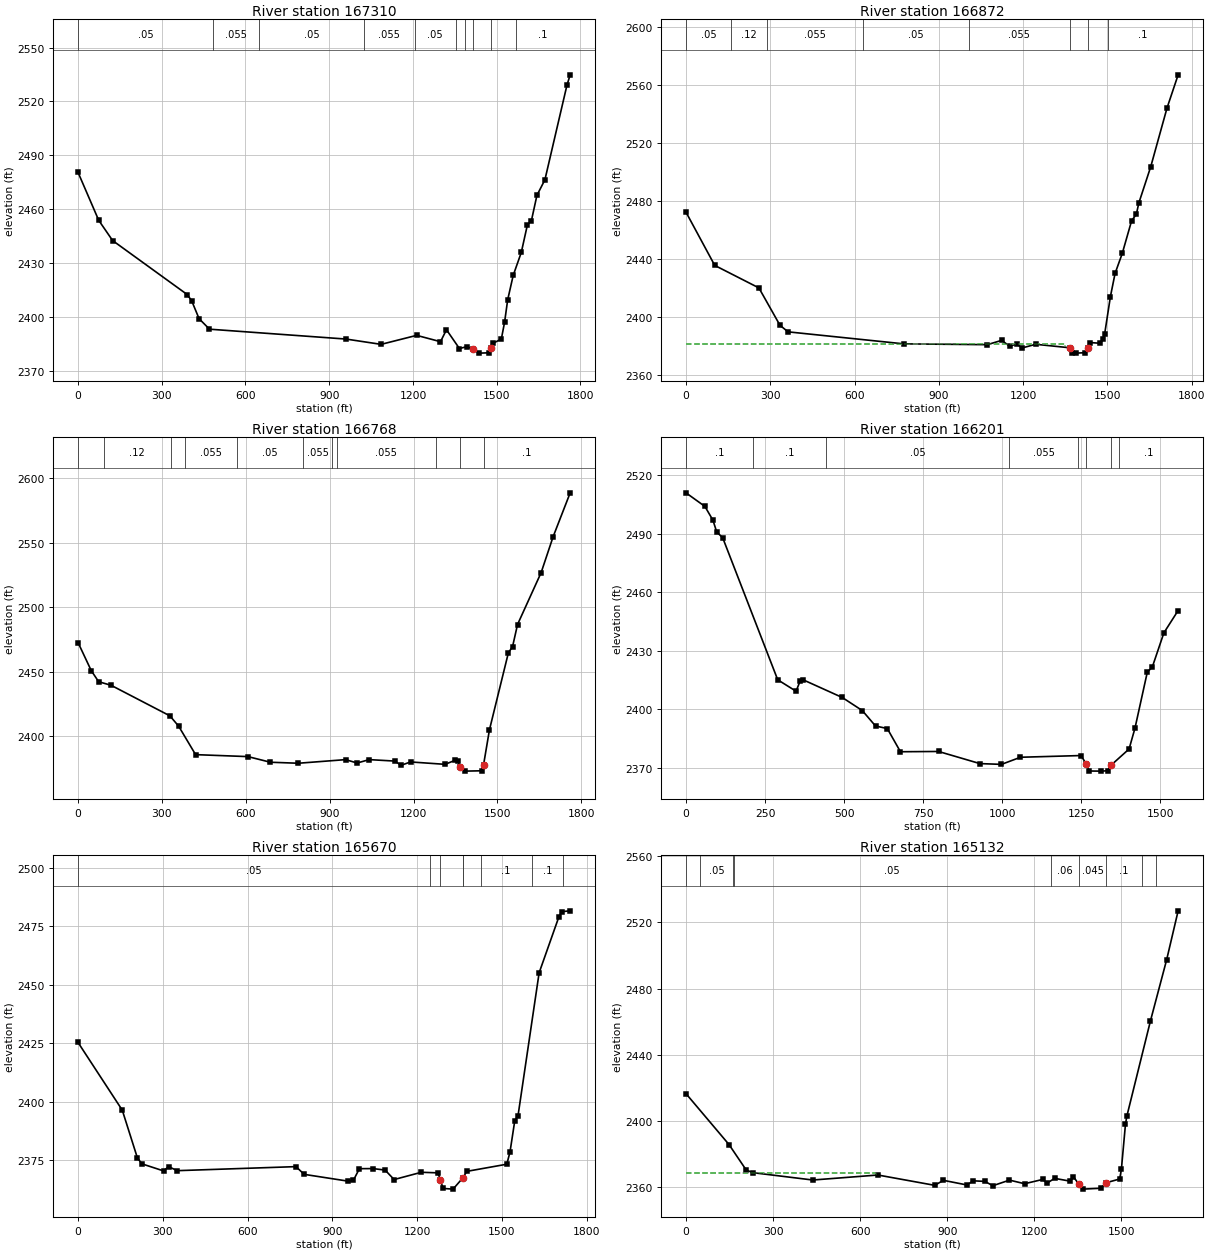
Type RM Length L Ch R = 1 ,167310  ,444.7,437.7,429.4
XS GIS Cut Line= 2
2382617.82631552582338.7588817182383938.80333236581170.951177955
#Sta/Elev= 30
       0 2480.45    74.2  2453.7     124 2442.43     391 2412.38     407 2408.95
   433.7 2398.91     471 2393.06     960 2387.56  1085.9 2384.61  1213.2 2389.62
  1298.6 2386.09    1320 2392.75  1366.4 2382.29  1394.7 2383.38 1415.332381.845
  1437.3 2379.72  1473.4  2379.9  1479.32382.397  1485.5  2385.1  1516.6 2387.58
  1528.2 2396.92  1539.3 2409.42  1559.1 2423.03  1588.1 2435.84  1610.1  2451.3
  1624.4 2453.57  1644.1 2467.63  1672.7 2476.32  1751.8 2529.09  1763.2 2534.78
#Mann= 10 ,-1 , 0
       0     .05       0  482.74    .055       0  648.32     .05       0
 1025.16    .055       0 1205.97     .05       0 1353.07      .1       0
 1386.77     .06       0 1415.33    .045       0  1479.3     .06       0
 1567.58      .1       0
Bank Sta=1415.33,1479.3
XS Rating Curve= 0 ,0
Exp/Cntr=0.5,0.3

Type RM Length L Ch R = 1 ,166872  ,104.9,104.3,112.1
XS GIS Cut Line= 4
 2382994.2494472582679.0524924552383954.88368076581752.893911704
2384013.55121437581667.908845454 2384258.9178496581471.367899954
#Sta/Elev= 30
       0 2472.11   102.3 2435.39   259.6 2419.86   334.5  2394.1   363.3 2389.56
   775.6 2381.27  1072.6 2380.71    1124  2383.7  1151.8 2379.65  1178.6 2381.23
  1195.3  2378.4  1245.1 2380.97 1366.162378.578  1375.7 2374.91  1387.5 2374.88
    1422 2375.18 1429.712378.535  1439.2 2382.16  1475.1 2381.68  1485.3 2384.41
  1490.5 2388.22  1510.9 2413.89  1527.4 2429.81  1553.1 2443.67  1586.4 2466.23
  1603.2 2470.66    1612  2478.4  1654.4 2503.45  1712.4 2543.95    1752 2566.84
#Mann= 8 ,-1 , 0
       0     .05       0  160.38     .12       0     290    .055       0
  629.07     .05       0 1006.44    .055       0 1366.16    .045       0
 1429.71     .06       0  1502.3      .1       0
#XS Ineff= 2 , 0
            1349  2381.2    1446          2381.2
Permanent Ineff=
       F       F
Bank Sta=1366.16,1429.71
XS Rating Curve= 0 ,0
Exp/Cntr=0.5,0.3

Type RM Length L Ch R = 1 ,166768  ,560.7,566.7,577.7
XS GIS Cut Line= 4
2383054.43371001582714.7489433742384045.30836868581808.003709629
2384088.05992362 581740.989736052384350.18210277581528.227038205
#Sta/Elev= 30
       0 2472.72    47.2 2450.99    73.7 2442.38   118.3  2439.6   328.5 2415.97
   359.7 2408.02   420.5 2385.93   607.7 2384.41   688.1 2380.05   787.8 2379.27
   957.1 2382.07   998.1 2379.45  1041.5 2382.08  1133.6 2380.94  1155.3 2377.66
  1189.2 2380.28  1312.6 2378.43  1347.9 2381.47  1359.5 2380.82 1366.54 2376.39
  1382.4 2373.17  1443.1 2373.43 1450.432378.035  1471.5 2405.14  1539.4 2464.93
    1554 2469.39  1571.9 2486.62  1656.4 2526.85  1699.1 2554.51  1760.2 2588.56
#Mann= 11 ,-1 , 0
       0     .05       0   93.38     .12       0   330.9      .1       0
  381.64    .055       0  568.43     .05       0  805.95    .055       0
  909.98     .05       0  924.71    .055       0    1281     .06       0
 1366.54    .045       0 1450.43      .1       0
Bank Sta=1366.54,1450.43
XS Rating Curve= 0 ,0
Exp/Cntr=0.5,0.3

Type RM Length L Ch R = 1 ,166201  ,531.1,531.4,529.4
XS GIS Cut Line= 2
2383317.05720052583113.9617276342384505.19163528582108.926664218
#Sta/Elev= 30
       0 2511.03    59.8 2504.05    85.3 2496.95      97 2490.99   116.2 2487.91
     290 2415.08     348  2409.2     361 2414.46     369 2415.16   494.1 2405.99
   557.6 2399.26   599.3 2391.35   636.5 2390.05   678.1 2378.14   798.6 2378.28
   929.5 2372.05   997.6 2371.66  1057.7 2375.31  1249.1 2376.19 1264.91 2372.03
  1275.3 2368.25  1311.6 2368.19    1333 2368.37 1344.712371.324  1401.1 2379.55
  1419.7 2390.24  1458.7    2419  1474.4 2421.56  1511.1 2439.16  1556.2 2450.63
#Mann= 8 ,-1 , 0
       0      .1       0  210.86      .1       0  442.64     .05       0
 1022.08    .055       0 1240.45     .06       0 1264.91    .045       0
 1344.71     .06       0 1369.74      .1       0
Bank Sta=1264.91,1344.71
XS Rating Curve= 0 ,0
Exp/Cntr=0.3,0.1

Type RM Length L Ch R = 1 ,165670  ,538,538.2,538.6
XS GIS Cut Line= 2
2383617.53757069583587.5710166252384920.94769353582432.495898962
#Sta/Elev= 30
       0 2425.37   156.6 2396.38   210.1 2375.95   226.1 2373.41   302.6 2370.39
   320.7 2372.22   350.8 2370.49   771.2 2372.22   800.4 2368.91   956.3 2365.99
   974.3 2366.32   995.7 2371.34  1043.8 2371.38  1086.6 2370.75  1118.6 2366.69
  1214.9  2369.8  1273.6 2369.56 1282.212366.597  1291.7 2362.89  1327.1 2362.59
  1362.12367.437  1375.6 2370.19  1517.3 2373.25  1528.6 2378.44  1545.6  2391.9
    1557 2393.96  1631.7 2455.16  1701.5 2479.07  1712.8 2481.36  1741.6  2481.7
#Mann= 8 ,-1 , 0
       0     .05       0  1244.7     .06       0 1282.21    .045       0
  1362.1     .06       0 1363.13      .1       0 1425.16      .1       0
 1605.63      .1       0 1715.78      .1       0
Bank Sta=1282.21,1362.1
XS Rating Curve= 0 ,0
Exp/Cntr=0.3,0.1

Type RM Length L Ch R = 1 ,165132  ,645.3,648.7,651.9
XS GIS Cut Line= 2
2383909.76172379584035.0051611212385186.50523329582918.559231296
#Sta/Elev= 30
       0 2416.41   148.2 2385.64   207.7 2370.18   231.1 2368.61     437 2364.18
   661.3 2367.21   856.9 2360.97   887.3 2363.98   968.4 2361.18   989.6  2363.7
  1029.8 2363.35  1057.5 2360.74  1114.8 2364.12  1166.9 2361.94  1228.8 2364.51
  1244.7 2362.32  1270.2 2365.19  1324.4 2363.47    1335 2366.24 1352.842361.858
  1366.9 2358.67  1429.5  2359.2 1448.612362.566  1494.4 2364.79  1500.4 2370.63
  1514.5 2397.97  1519.3 2402.85  1600.7 2460.51  1656.3 2497.34    1696    2527
#Mann= 9 ,-1 , 0
       0      .1       0   48.37     .05       0   162.4      .1       0
  165.43     .05       0  1256.5     .06       0 1352.84    .045       0
 1448.61      .1       0 1570.15     .12       0  1621.2      .1       0
#XS Ineff= 2 , 0
           656.3 2368.39
Permanent Ineff=
       F       F
Bank Sta=1352.84,1448.61
XS Rating Curve= 0 ,0
Exp/Cntr=0.3,0.1