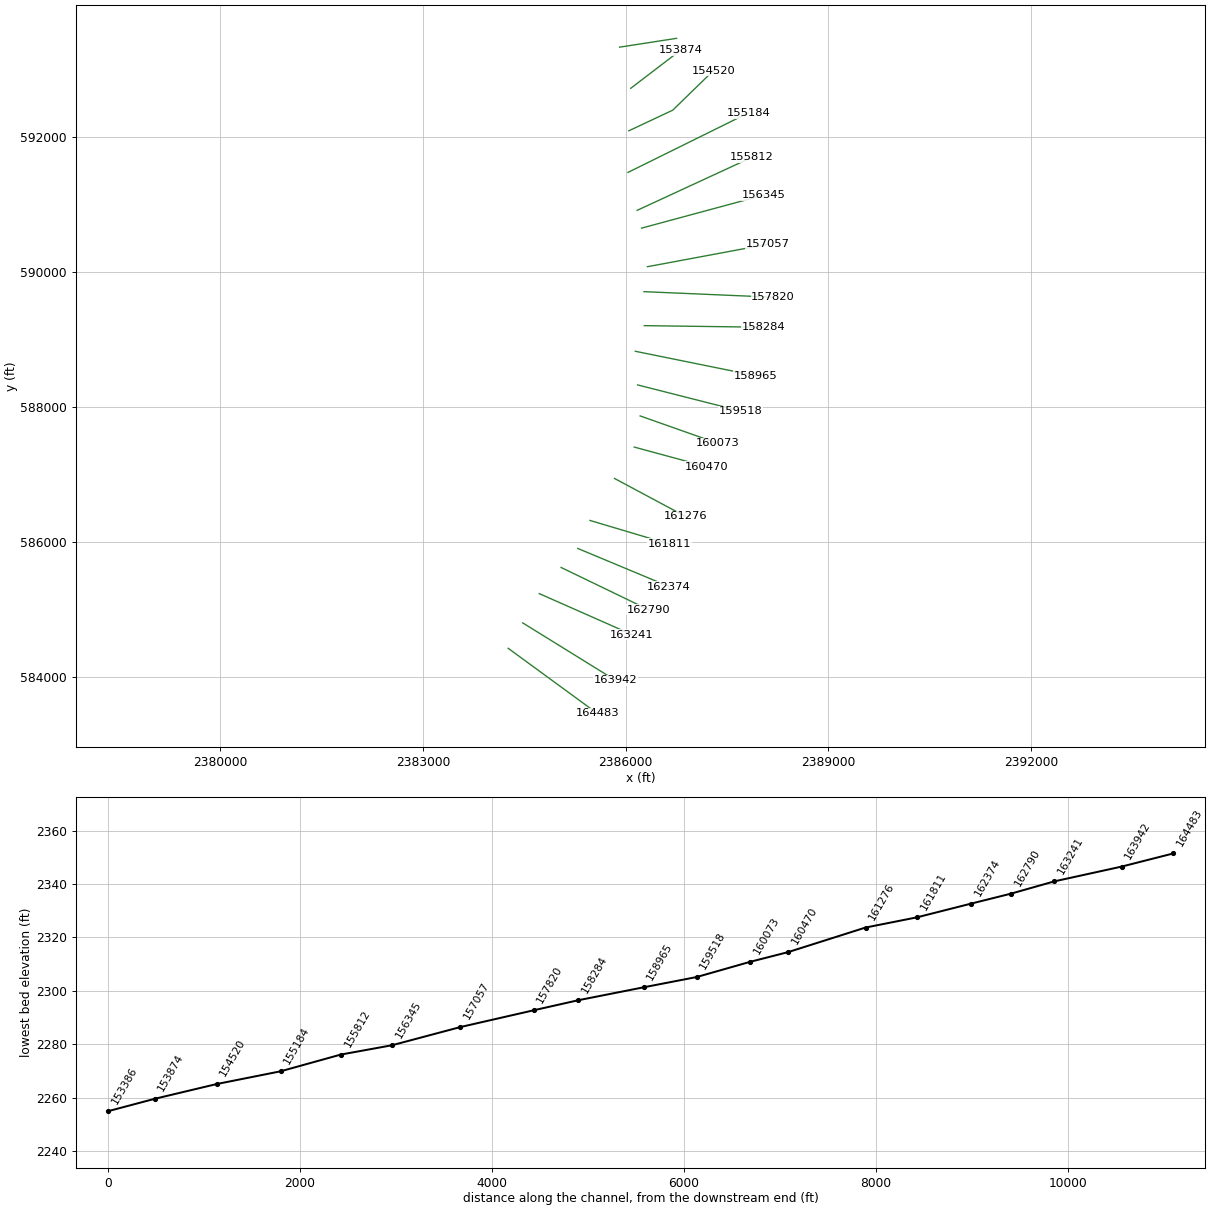
HEC-RAS study NFSBPOTOMC.prj: NFSBPOTOMC

--- NFSBPOTOMC.g01 (geometry) --- (continued)

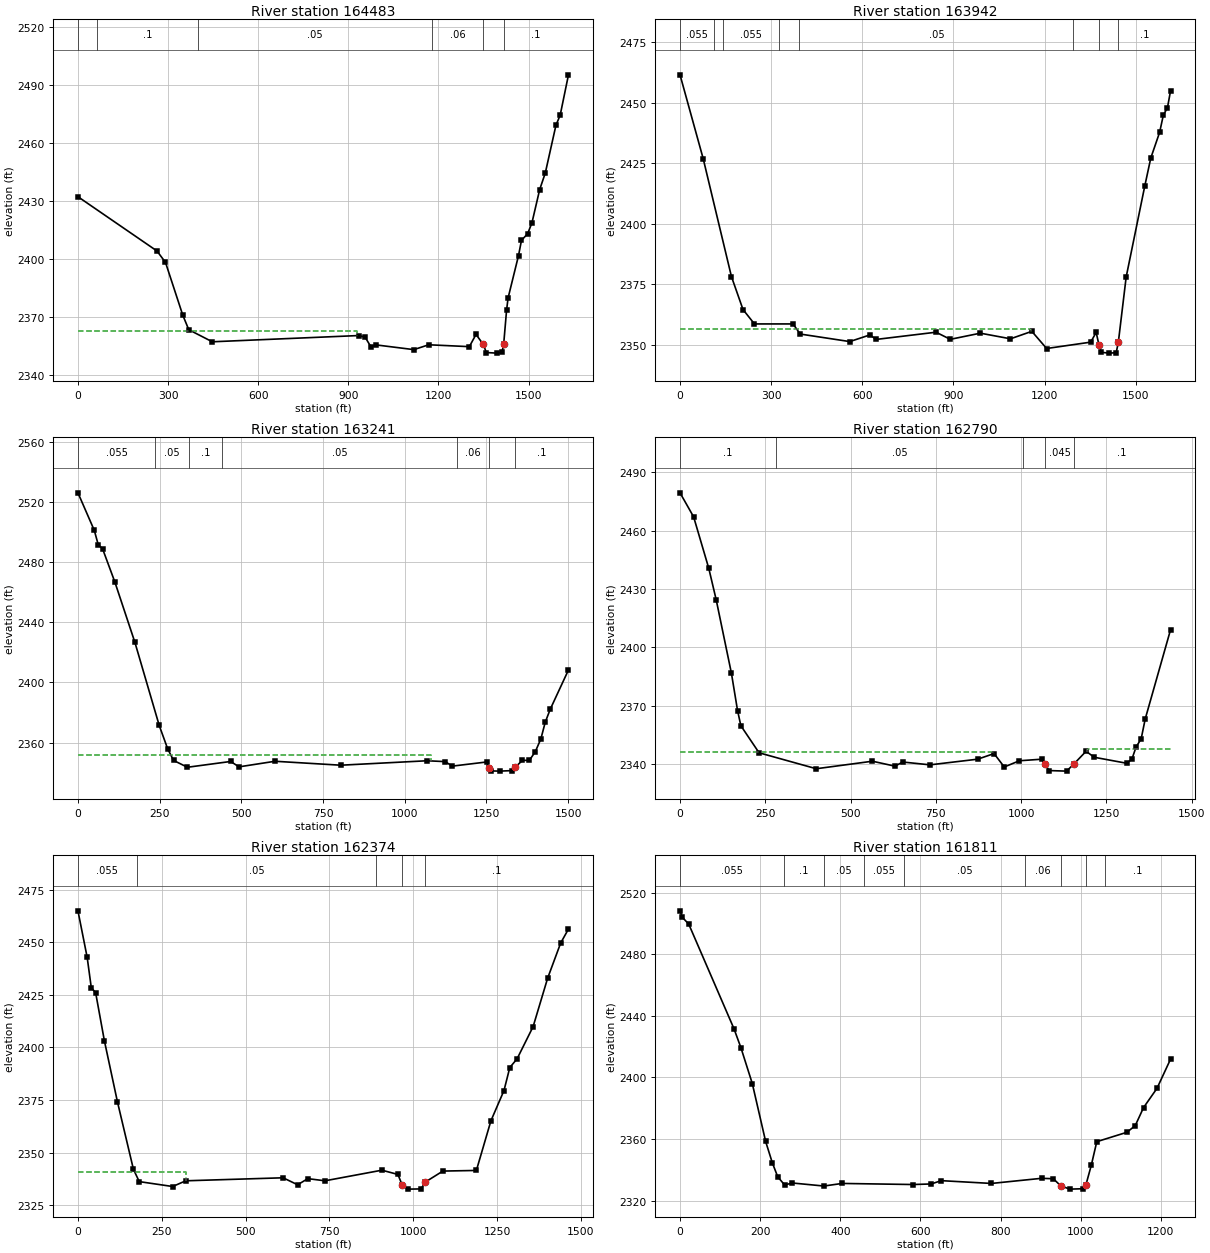
Type RM Length L Ch R = 1 ,164483  ,537.7,540.5,542.9
XS GIS Cut Line= 2
2384259.30794069584426.946306378 2385576.9821426583463.068640962
#Sta/Elev= 30
       0 2432.43     263 2404.35   291.4 2398.44   348.8 2371.19   368.9 2363.61
   447.2 2357.37   935.1  2360.6   955.8 2359.75   975.6 2354.63   990.5 2355.79
    1118 2353.31  1167.4 2355.82  1302.7 2354.85  1324.9 2361.18 1349.182355.996
  1359.2 2351.81  1393.5  2351.5  1411.7 2352.07 1417.042356.266  1426.6 2373.71
  1431.6 2380.02  1466.3 2401.94  1476.2 2409.85  1496.6 2413.26  1510.9 2418.83
  1536.7 2436.09  1555.5 2444.72    1591 2469.45    1605 2474.61  1632.6 2495.49
#Mann= 6 ,-1 , 0
       0     .05       0   63.62      .1       0  397.95     .05       0
 1178.04     .06       0 1349.18    .045       0 1417.04      .1       0
#XS Ineff= 2 , 0
             929 2362.71
Permanent Ineff=
       F       F
Bank Sta=1349.18,1417.04
XS Rating Curve= 0 ,0
Exp/Cntr=0.3,0.1

Type RM Length L Ch R = 1 ,163942  ,696.3,701.2,703.3
XS GIS Cut Line= 2
2384474.55455744584803.6903035492385846.80903077583953.541085213
#Sta/Elev= 30
       0 2461.51    76.3 2426.86   169.2 2378.19   207.3 2364.55   244.9 2358.61
     372 2358.61   395.5 2354.43   558.6 2351.32   625.4 2354.09   644.9  2352.2
   842.5 2355.19   889.5 2352.25   988.4 2354.79  1087.6 2352.47  1157.8 2355.55
  1206.5 2348.46  1351.7 2351.09  1369.5 2355.13 1378.522350.066  1386.6 2346.89
  1411.9 2346.55  1435.4 2346.72 1442.452350.992  1468.3 2378.01  1529.5 2415.58
  1549.3 2427.14  1578.4 2437.77  1590.7 2444.91  1604.1 2447.91  1614.3 2454.88
#Mann= 8 ,-1 , 0
       0    .055       0  111.72      .1       0  142.16    .055       0
  326.84      .1       0  392.33     .05       0 1294.83     .06       0
 1378.52    .045       0 1442.45      .1       0
#XS Ineff= 2 , 0
         1154.89 2356.53
Permanent Ineff=
       F       F
Bank Sta=1378.52,1442.45
XS Rating Curve= 0 ,0
Exp/Cntr=0.3,0.1

Type RM Length L Ch R = 1 ,163241  ,452.7,451.7,449.6
XS GIS Cut Line= 2
2384719.26076093 585237.334777462386091.91877678584630.242487714
#Sta/Elev= 30
       0 2526.18      50 2501.21    62.1 2491.66    75.3 2488.99   113.2 2466.68
   174.4  2426.6   248.7 2371.39   274.4 2355.93   292.5 2348.15     335 2343.58
   467.4 2347.44   492.7 2343.85     603 2347.57   804.2 2344.95  1068.6 2347.91
  1123.5 2347.34  1145.4 2344.34  1250.3 2347.09 1257.422343.379  1263.5 2341.16
  1290.3 2341.01  1329.1 2341.37 1337.252343.455    1360 2348.17  1381.3 2348.19
  1399.5 2353.98  1416.5 2362.49  1429.8 2373.52  1444.9 2382.08  1500.9 2408.34
#Mann= 7 ,-1 , 0
       0    .055       0  236.68     .05       0  339.34      .1       0
  441.99     .05       0 1160.57     .06       0 1257.42    .045       0
 1337.25      .1       0
#XS Ineff= 2 , 0
         1079.93 2351.82
Permanent Ineff=
       F       F
Bank Sta=1257.42,1337.25
XS Rating Curve= 0 ,0
Exp/Cntr=0.3,0.1

Type RM Length L Ch R = 1 ,162790  ,414.3,416,418.5
XS GIS Cut Line= 2
2385042.84377518585624.5147773772386337.68009627584998.800477624
#Sta/Elev= 30
       0 2479.41    39.9 2467.06    84.3 2440.62     106 2424.51   150.8 2386.61
   168.7 2367.51   178.4 2359.72   231.8 2345.82   399.5 2337.63   564.1 2341.49
   630.1 2338.95   652.9 2341.08   732.9 2339.63   872.7 2342.54   920.7 2345.42
   950.6 2338.53     995 2341.73  1061.4 2342.54 1070.582339.808  1082.4 2336.69
  1133.3  2336.4 1154.472340.022  1190.5 2346.61  1214.2 2343.53    1310 2340.43
    1325 2342.66  1337.1 2348.79    1352 2353.03  1363.9 2363.24  1438.1 2409.05
#Mann= 5 ,-1 , 0
       0      .1       0   281.2     .05       0 1006.59     .06       0
 1070.58    .045       0 1154.47      .1       0
#XS Ineff= 2 ,-1
       0  920.75 2346.13 1192.99 1438.09 2347.74
Permanent Ineff=
       F       F
Bank Sta=1070.58,1154.47
XS Rating Curve= 0 ,0
Exp/Cntr=0.3,0.1

Type RM Length L Ch R = 1 ,162374  ,559.3,562.4,565.9
XS GIS Cut Line= 2
2385290.01093176585906.2924290452386640.27102652585342.237782881
#Sta/Elev= 30
       0 2464.94    27.6 2442.77    39.8 2428.41    52.8 2426.02    78.8 2403.24
   117.8 2374.17   165.5 2342.09   182.9 2336.23   282.6  2333.9   321.6 2336.62
     612 2338.05   655.4 2334.73   685.7 2337.64     737 2336.62   906.8 2341.66
   954.5 2339.64  967.572334.511   984.7 2332.66  1023.9 2332.76 1035.532335.954
  1088.6 2341.24  1188.6 2341.54  1231.9 2365.11  1270.9 2379.51  1288.3 2390.47
    1310 2394.59  1357.9 2409.93    1401 2432.85    1440 2449.62  1463.3 2456.29
#Mann= 5 ,-1 , 0
       0    .055       0  174.75     .05       0  889.62     .06       0
  967.57    .045       0 1035.53      .1       0
#XS Ineff= 2 , 0
          321.99  2340.9
Permanent Ineff=
       F       F
Bank Sta=967.57,1035.53
XS Rating Curve= 0 ,0
Exp/Cntr=0.3,0.1

Type RM Length L Ch R = 1 ,161811  ,539.1,534.8,528.3
XS GIS Cut Line= 2
2385469.91313103586321.5261786282386643.09713635585971.613164544
#Sta/Elev= 30
       0 2508.13       6 2503.85    21.7 2499.55   134.6 2431.67     152 2419.32
   180.4 2396.05   213.7 2358.46   230.4 2344.62   243.9 2335.52   261.1 2330.24
   280.5 2331.51   359.1 2329.54   404.7 2331.22   581.1 2330.52     627 2330.88
     652 2333.03   777.3 2331.22   902.5 2334.55   931.7 2334.27  950.15  2329.7
   972.8 2327.53  1006.8 2327.79  1012.9 2330.12  1026.4 2342.92  1040.2 2358.32
  1115.4 2364.42  1136.2 2368.74    1157 2380.48  1190.5 2392.94  1224.3 2411.87
#Mann= 9 ,-1 , 0
       0    .055       0  259.64      .1       0  359.79     .05       0
  459.94    .055       0  560.09     .05       0  860.55     .06       0
  950.15    .045       0  1012.9     .06       0 1060.85      .1       0
Bank Sta=950.15,1012.9
XS Rating Curve= 0 ,0
Exp/Cntr=0.3,0.1

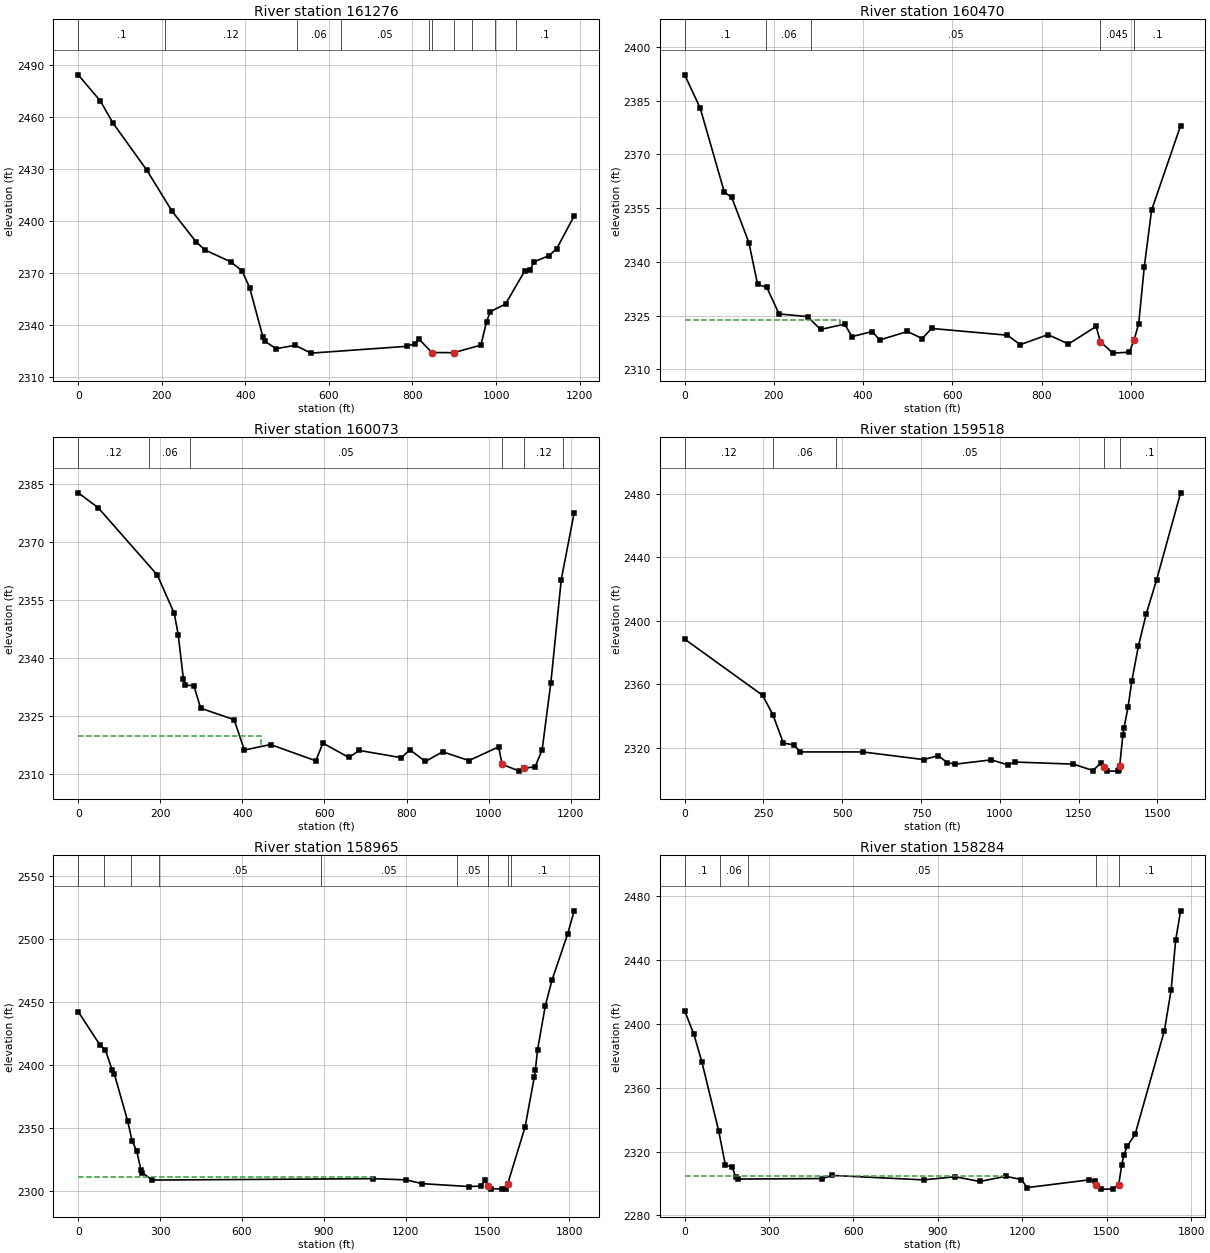
Type RM Length L Ch R = 1 ,161276  ,796.4,806.4,817.9
XS GIS Cut Line= 2
2385833.09186661 586943.719488042386879.47822526586383.421724126
#Sta/Elev= 30
       0 2484.25    52.6 2469.29    83.5 2456.33   164.4 2429.18   224.2 2405.73
   281.4  2388.1   303.2 2383.23   364.9  2376.4   392.1 2371.18   410.2 2361.55
     442 2333.11   446.5 2330.54   473.8 2326.27   519.1 2328.22   557.4 2323.71
   786.8 2327.64   805.6 2329.17   815.2 2331.92  846.412324.059  898.262323.965
   963.8 2328.31   977.4 2341.92   986.5 2347.66  1022.8 2352.06  1068.2  2370.9
  1081.8 2371.76  1090.8 2376.36  1127.1 2379.98  1145.3    2384    1187 2402.79
#Mann= 10 ,-1 , 0
       0      .1       0  208.52     .12       0  523.56     .06       0
  628.57     .05       0   838.6      .1       0  846.41    .045       0
  898.26      .1       0  943.62      .1       0  998.71      .1       0
 1048.63      .1       0
Bank Sta=846.41,898.26
XS Rating Curve= 0 ,0
Exp/Cntr=0.3,0.1

Type RM Length L Ch R = 1 ,160470  ,399.1,396.8,392.6
XS GIS Cut Line= 2
2386125.03747693587408.5112093842387197.44018778 587117.72701405
#Sta/Elev= 30
       0  2392.2    34.9 2382.86    88.8 2359.45   105.4 2357.97   143.8 2345.38
   163.4 2333.68   184.1 2332.84   211.4 2325.44   275.3  2324.7   304.3 2321.11
   358.2 2322.59   374.8 2319.13   420.4 2320.52   436.9 2318.17   499.1 2320.54
   532.3 2318.55     553 2321.39   722.9  2319.5   751.9 2316.87   814.1 2319.67
   859.7 2317.04   921.8 2321.94  931.272317.719   959.1  2314.5   996.4 2314.76
 1007.212318.297  1017.2 2322.77  1029.7 2338.58    1046 2354.39  1111.1 2378.03
#Mann= 5 ,-1 , 0
       0      .1       0  183.06     .06       0  282.92     .05       0
  931.27    .045       0 1007.21      .1       0
#XS Ineff= 2 , 0
          348.32 2323.87
Permanent Ineff=
       F       F
Bank Sta=931.27,1007.21
XS Rating Curve= 0 ,0
Exp/Cntr=0.3,0.1

Type RM Length L Ch R = 1 ,160073  ,553.5,555.4,557.2
XS GIS Cut Line= 2
2386213.04648727587869.9994596242387352.36310628 587467.45367679
#Sta/Elev= 30
       0 2382.74    48.5 2378.91   192.7 2361.51   233.9 2351.62   243.6 2346.14
   256.3 2334.61   260.6  2333.1   281.8 2332.89   298.4  2327.1   379.9 2324.14
   404.8 2316.29   468.5 2317.72   578.8 2313.52   596.2 2318.08   659.4 2314.38
   684.8 2316.19   787.5 2314.32   807.8 2316.38     846 2313.35   887.8 2315.84
   952.1 2313.58  1024.2 2317.12 1032.872312.604  1075.1 2310.85 1087.312311.575
  1113.3 2311.99  1130.3 2316.34  1151.5 2333.65  1176.9 2360.34  1208.3 2377.57
#Mann= 6 ,-1 , 0
       0     .12       0  171.81     .06       0  272.73     .05       0
 1032.87    .045       0 1087.31     .12       0 1181.09      .1       0
#XS Ineff= 2 , 0
          446.02 2319.84
Permanent Ineff=
       F       F
Bank Sta=1032.87,1087.31
XS Rating Curve= 0 ,0
Exp/Cntr=0.3,0.1

Type RM Length L Ch R = 1 ,159518  ,550.2,552.4,554.3
XS GIS Cut Line= 2
2386175.22241595588329.4499842972387700.57730487587941.836914375
#Sta/Elev= 30
       0 2388.44   247.1 2353.04   280.2 2340.64   313.2 2322.85   346.2 2321.74
   366.8 2317.27   564.9 2317.27   758.6 2312.44   804.7 2314.93   833.2 2310.54
   857.9 2309.54   973.5 2312.28    1025 2309.12  1047.8 2310.91  1233.5 2309.57
  1295.4 2305.54  1320.2 2310.16  1329.92307.967  1340.8 2305.16    1374  2305.2
    1378 2305.93 1380.482308.505  1390.3 2327.65  1393.8 2332.17  1406.9 2345.44
  1419.2  2362.3  1439.8 2384.07  1464.6 2404.26  1497.7 2425.97  1573.8 2480.77
#Mann= 5 ,-1 , 0
       0     .12       0  281.04     .06       0  480.45     .05       0
  1329.9    .045       0 1380.48      .1       0
Bank Sta=1329.9,1380.48
XS Rating Curve= 0 ,0
Exp/Cntr=0.3,0.1

Type RM Length L Ch R = 1 ,158965  ,673.9,681.3,688.8
XS GIS Cut Line= 2
2386141.10503012588828.0224779552387922.11491951588466.251219884
#Sta/Elev= 30
       0 2442.28    79.2 2415.92    99.6 2411.77   124.1 2396.08   132.3 2392.83
   181.3  2355.3   197.6 2339.58   213.9 2331.91   230.2 2316.39   234.3  2314.4
   271.1 2308.51  1079.2 2309.62  1201.7 2308.66    1261 2305.63  1430.3 2303.39
  1475.2 2303.69  1491.5  2308.3 1501.842304.151  1511.9 2301.75  1552.7 2301.31
  1566.3 2301.67 1573.732305.387  1637.6 2350.67  1671.5 2390.43  1675.2 2395.84
  1683.3 2411.96  1711.9  2447.1  1736.4 2467.43  1794.1 2504.15  1817.4 2522.29
#Mann= 9 ,-1 , 0
       0      .1       0   95.55     .12       0  194.95     .06       0
  294.34     .05       0  890.72     .05       0 1387.71     .05       0
 1501.84    .045       0 1573.73     .05       0  1586.5      .1       0
#XS Ineff= 2 , 0
         1081.97 2311.31
Permanent Ineff=
       F       F
Bank Sta=1501.84,1573.73
XS Rating Curve= 0 ,0
Exp/Cntr=0.3,0.1

Type RM Length L Ch R = 1 ,158284  ,464.9,464.5,466.1
XS GIS Cut Line= 2
2386273.84032893589207.7720465512388036.35189578 589184.23797287
#Sta/Elev= 30
       0 2408.01    32.5 2393.55    60.9 2376.27   120.9 2332.93   144.9 2311.34
   168.9 2310.38   180.9 2304.07   188.9 2302.78   488.9 2303.09     525 2305.05
     849 2302.25     961 2304.22    1049 2301.27    1141 2304.48    1197 2302.48
    1217 2297.41    1437 2302.25    1457 2301.67  1462.92298.941    1481 2296.46
    1521 2296.49 1542.832299.332    1553 2311.42    1561 2317.81    1573  2323.4
    1601  2330.8  1705.1 2395.73  1729.1 2421.34  1745.1 2452.37  1762.7 2470.75
#Mann= 5 ,-1 , 0
       0      .1       0  125.92     .06       0  226.33     .05       0
  1462.9    .045       0 1542.83      .1       0
#XS Ineff= 2 , 0
          1135.1 2304.87
Permanent Ineff=
       F       F
Bank Sta=1462.9,1542.83
XS Rating Curve= 0 ,0
Exp/Cntr=0.3,0.1

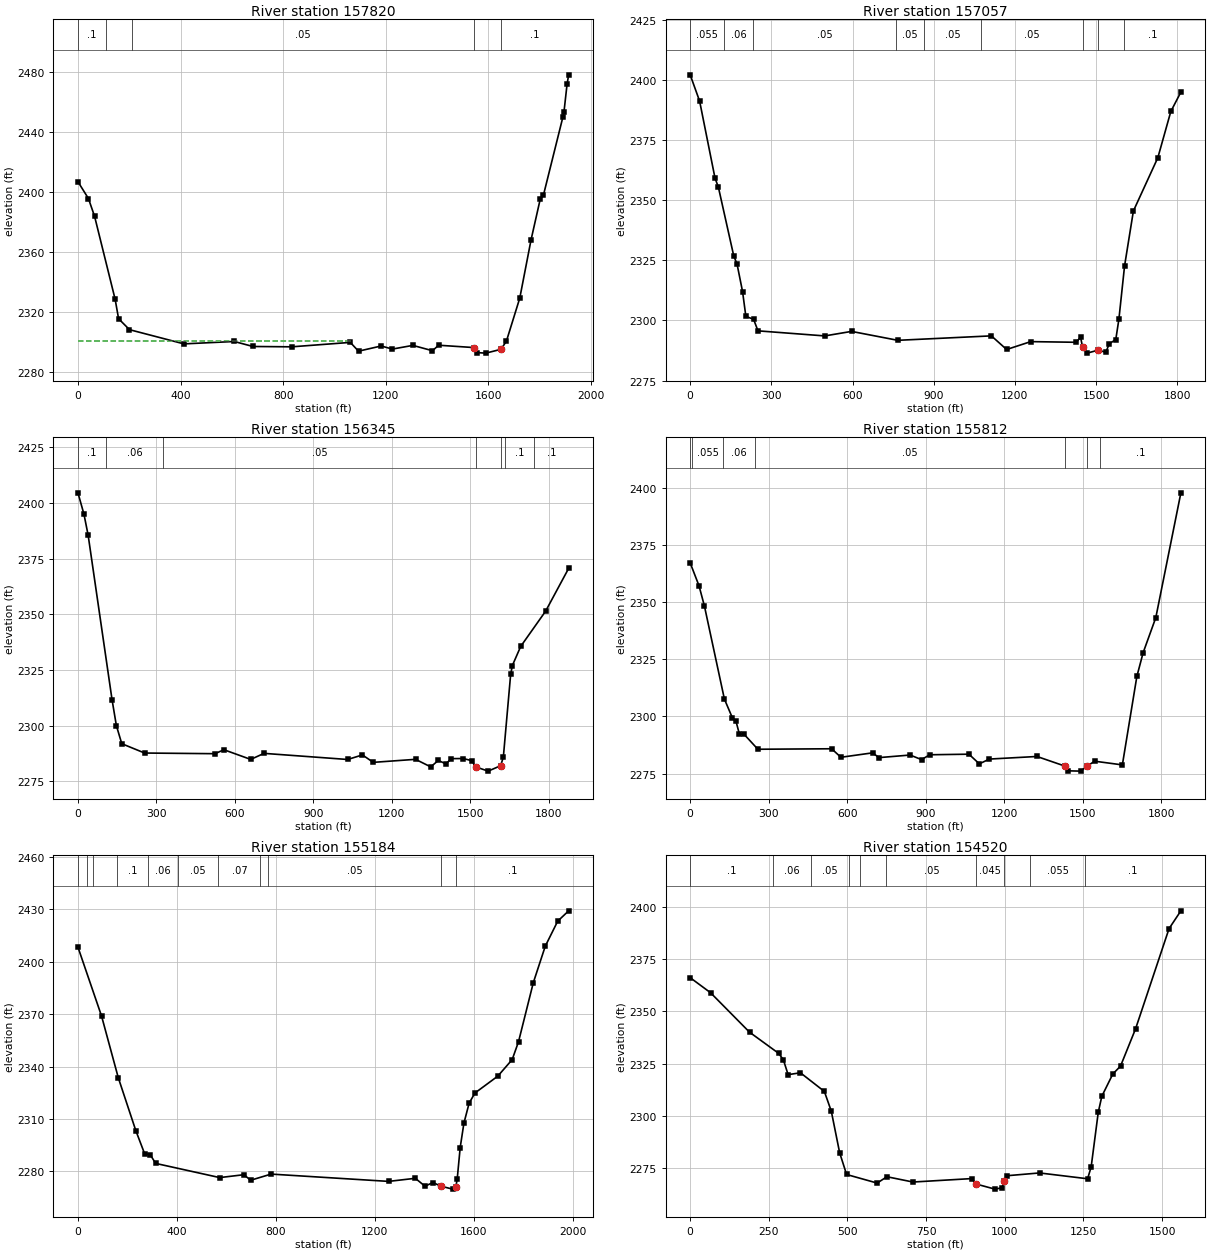
Type RM Length L Ch R = 1 ,157820  ,750,762.6,772.1
XS GIS Cut Line= 2
2386270.02603212589711.1762234572388181.05173761589629.284326881
#Sta/Elev= 30
       0 2407.05    40.8 2395.85    64.8 2383.97   144.9 2328.65   158.4 2315.65
   200.9 2308.34   413.1 2298.86   609.3 2300.45   682.3 2297.12   833.5  2296.9
  1061.7 2299.85  1093.7 2293.99  1181.8 2297.45  1225.8  2295.4  1305.5 2297.85
    1382 2294.29  1405.9 2297.96  1545.42296.381  1554.1 2293.04    1590 2292.69
 1649.232295.248  1670.3 2300.74  1722.3 2329.44  1766.3 2368.34  1802.4 2395.74
  1814.4 2398.01  1890.5 2450.32  1894.5 2453.48  1906.5 2471.96  1912.8 2478.37
#Mann= 5 ,-1 , 0
       0      .1       0  110.35     .06       0  210.36     .05       0
  1545.4    .045       0 1649.23      .1       0
#XS Ineff= 2 , 0
         1062.75 2300.57
Permanent Ineff=
       F       F
Bank Sta=1545.4,1649.23
XS Rating Curve= 0 ,0
Exp/Cntr=0.3,0.1

Type RM Length L Ch R = 1 ,157057  ,706,711.8,720.3
XS GIS Cut Line= 2
2386320.45998636590080.9126887172388103.24513468590413.605264798
#Sta/Elev= 30
       0 2402.21    34.9 2391.27    91.8 2359.22   104.1 2355.53     161 2326.87
   173.2 2323.48   193.6    2312   205.8  2301.7   234.3 2300.49   250.6 2295.68
   497.4 2293.57   596.4 2295.45   767.3 2291.74  1113.2 2293.59  1169.6 2287.92
  1258.7  2291.2  1426.7 2290.92  1442.8 2293.01 1450.052289.125  1467.2 2286.41
 1507.692287.642  1536.4 2286.78  1548.6 2290.27    1573 2292.07  1584.5 2300.52
  1605.5 2322.73  1638.1 2345.56  1728.5 2367.75  1776.4 2386.96  1813.6 2395.04
#Mann= 9 ,-1 , 0
       0    .055       0  126.45     .06       0  231.99     .05       0
  759.73     .05       0  865.27     .05       0 1076.37     .05       0
 1450.05    .045       0 1507.69     .05       0  1604.1      .1       0
Bank Sta=1450.05,1507.69
XS Rating Curve= 0 ,0
Exp/Cntr=0.3,0.1

Type RM Length L Ch R = 1 ,156345  ,524.8,533,541.2
XS GIS Cut Line= 2
2386233.07827136590652.4072806242388043.70850834591141.800002635
#Sta/Elev= 30
       0 2404.61      23 2394.98      39 2385.54   130.2 2311.76   146.9 2300.02
   167.5 2291.91   254.8 2287.72   523.8 2287.42   557.9  2289.2   660.5 2284.85
   711.2 2287.57  1030.9 2284.82  1087.3 2286.87  1128.8 2283.53  1290.4 2284.89
  1348.4  2281.5  1377.4 2284.39  1406.4 2282.84  1427.1  2285.2  1472.7 2285.25
  1505.8 2284.27 1519.682281.512    1568 2279.59 1615.662282.024    1626 2285.91
  1653.9 2323.03  1660.4 2327.01  1692.3 2335.61  1787.6 2351.46  1875.6 2370.68
#Mann= 7 ,-1 , 0
       0      .1       0  107.65     .06       0  325.65     .05       0
 1519.68    .045       0 1615.66     .05       0  1633.7      .1       0
  1742.7      .1       0
Bank Sta=1519.68,1615.66
XS Rating Curve= 0 ,0
Exp/Cntr=0.3,0.1

Type RM Length L Ch R = 1 ,155812  ,628.7,628.1,623.9
XS GIS Cut Line= 2
2386168.04329643590916.1078687162387869.68654668591703.211609468
#Sta/Elev= 30
       0 2367.09    33.8 2357.07    54.3  2348.3   130.7  2307.6   161.6 2299.29
   174.9 2297.96   187.9 2292.33   205.7 2292.23   258.6 2285.66   540.5 2285.87
   575.9 2282.15   697.2 2284.09   721.2    2282   840.3 2283.13     884 2281.13
   915.3 2283.25  1065.1  2283.5  1104.8 2279.28  1143.2 2281.37  1325.1  2282.5
 1431.132278.325  1444.1 2276.23  1492.6  2276.1 1515.082278.166  1545.5 2280.44
  1651.3 2278.82  1706.7 2317.47  1730.6 2327.82  1779.1 2343.18  1874.9  2397.7
#Mann= 7 ,-1 , 0
       0      .1       0    7.06    .055       0  126.91     .06       0
  246.76     .05       0 1431.13    .045       0 1515.08     .05       0
 1565.08      .1       0
Bank Sta=1431.13,1515.08
XS Rating Curve= 0 ,0
Exp/Cntr=0.3,0.1

Type RM Length L Ch R = 1 ,155184  ,658.2,663.9,673.6
XS GIS Cut Line= 2
2386033.07243776591478.1520202162387811.34447178 592357.64271529
#Sta/Elev= 30
       0  2408.4    95.6 2368.87     163 2333.66   233.9 2303.35   269.6 2290.06
   291.9 2289.61   314.2 2284.55   573.1 2276.43   671.2 2278.08     698  2274.9
   781.1 2278.43  1255.8 2274.25  1364.1 2276.02  1403.1 2271.48    1435 2273.61
 1466.782271.552  1514.6 2269.82  1527.92271.076  1533.5 2275.87  1545.4 2293.66
  1560.4 2307.58  1581.6 2319.11  1605.2 2324.89  1697.6 2334.55  1755.6 2344.01
  1781.3 2354.28    1841 2388.06  1889.5    2409  1939.6 2423.28  1983.9 2429.21
#Mann= 11 ,-1 , 0
       0    .055       0   37.37      .1       0   59.83    .055       0
   159.4      .1       0  281.44     .06       0  403.48     .05       0
  568.03     .07       0  737.43    .055       0  769.59     .05       0
 1466.78    .045       0  1527.9      .1       0
Bank Sta=1466.78,1527.9
XS Rating Curve= 0 ,0
Exp/Cntr=0.3,0.1

Type RM Length L Ch R = 1 ,154520  ,645.9,645.9,644.8
XS GIS Cut Line= 3
2386044.78665319592094.6553803832386695.21120536592400.327669293
2387297.67686394592987.337978214
#Sta/Elev= 30
       0 2366.07    64.8 2358.87   188.6 2340.04   281.3 2329.91   296.3 2326.81
   311.3 2319.74   350.4 2320.64   426.5 2311.73   448.6 2302.28   475.1 2282.44
   497.2 2272.05   594.4 2267.95   625.3 2270.98   708.2 2268.45   894.3 2270.09
  910.022267.448   968.8 2265.06   991.7 2265.71  997.732268.837  1008.4 2271.48
  1110.5 2272.79  1263.3 2270.01  1274.6 2275.68  1297.2 2301.79  1308.5 2309.41
  1343.5 2320.07  1367.9 2323.81  1415.9 2341.69  1522.2  2389.5  1559.8    2398
#Mann= 10 ,-1 , 0
       0      .1       0  262.76     .06       0   383.1     .05       0
  503.45      .1       0  538.57      .1       0  623.79     .05       0
  910.02    .045       0  997.73      .1       0 1080.59    .055       0
 1254.49      .1       0
Bank Sta=910.02,997.73
XS Rating Curve= 0 ,0
Exp/Cntr=0.3,0.1

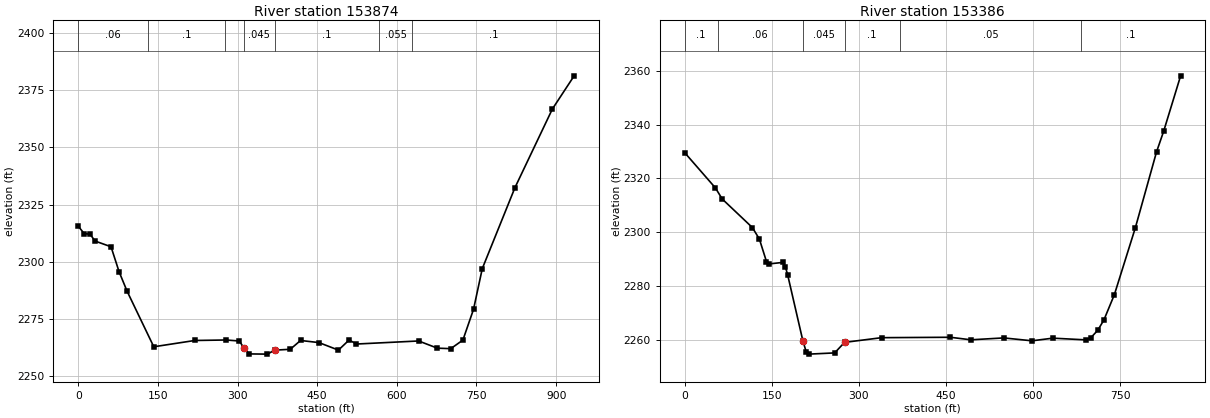
Type RM Length L Ch R = 1 ,153874  ,503.2,487.9,470.2
XS GIS Cut Line= 2
2386073.64683169592724.4575984632386815.31529585593292.022408217
#Sta/Elev= 30
       0 2315.55    11.1 2312.31    22.5    2312    31.6 2309.03    61.8 2306.52
    76.9 2295.63      92 2287.08   142.3 2262.74   219.4 2265.49   278.4 2265.71
   303.6 2265.26  311.312262.411   322.1 2259.61   356.3 2259.52  369.732261.256
   399.3 2261.64   418.7  2265.5   453.3 2264.57     490 2261.28   510.1  2265.7
     524 2263.94   641.1 2265.28   676.3 2262.13   701.5 2261.91   724.4 2265.67
   744.4 2279.13   760.9 2296.96   822.4 2332.39   892.9 2366.83   933.9 2381.35
#Mann= 7 ,-1 , 0
       0     .06       0  131.86      .1       0  276.51     .05       0
  311.31    .045       0  369.73      .1       0   565.8    .055       0
  629.33      .1       0
Bank Sta=311.31,369.73
XS Rating Curve= 0 ,0
Exp/Cntr=0.3,0.1

Type RM Length L Ch R = 1 ,153386  ,406.7,406.2,405.2
XS GIS Cut Line= 2
2385907.52839753593333.7408287082386751.75603977593464.602771714
#Sta/Elev= 30
       0 2329.57    52.9  2316.5    64.7 2312.37   116.6  2301.8   128.7 2297.52
   140.9 2289.18   144.9  2288.3   169.2 2288.87   173.3 2287.33   177.3 2284.33
   203.6 2259.79   209.7 2255.47   213.7 2254.86   258.3 2255.31  275.45 2259.22
   339.2 2260.96   457.6 2261.11     493 2260.17   549.7 2260.87   598.3  2259.8
   634.2 2260.78   690.7 2260.15   699.5 2260.91   711.6 2263.71   722.3  2267.6
   740.2 2276.92   776.4 2301.77   812.8 2329.84     825 2337.45   854.3 2358.05
#Mann= 6 ,-1 , 0
       0      .1       0   56.88     .06       0   203.6    .045       0
  275.45      .1       0  370.21     .05       0  683.53      .1       0
Bank Sta=203.6,275.45
XS Rating Curve= 0 ,0
Exp/Cntr=0.3,0.1