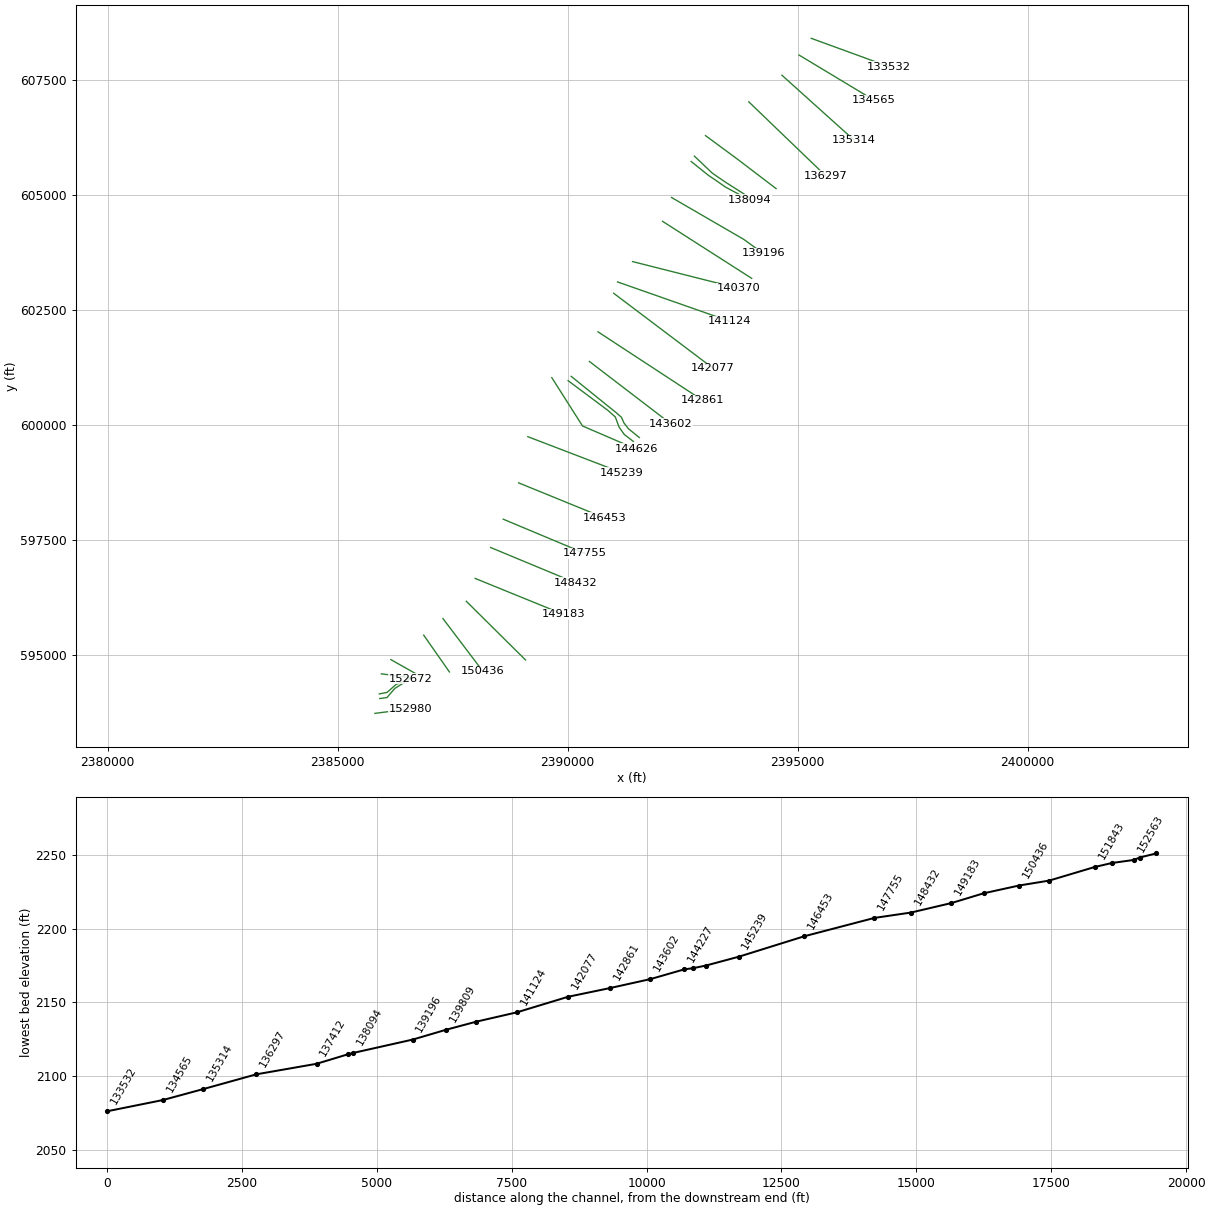
HEC-RAS study NFSBPOTOMC.prj: NFSBPOTOMC

--- NFSBPOTOMC.g01 (geometry) --- (continued)

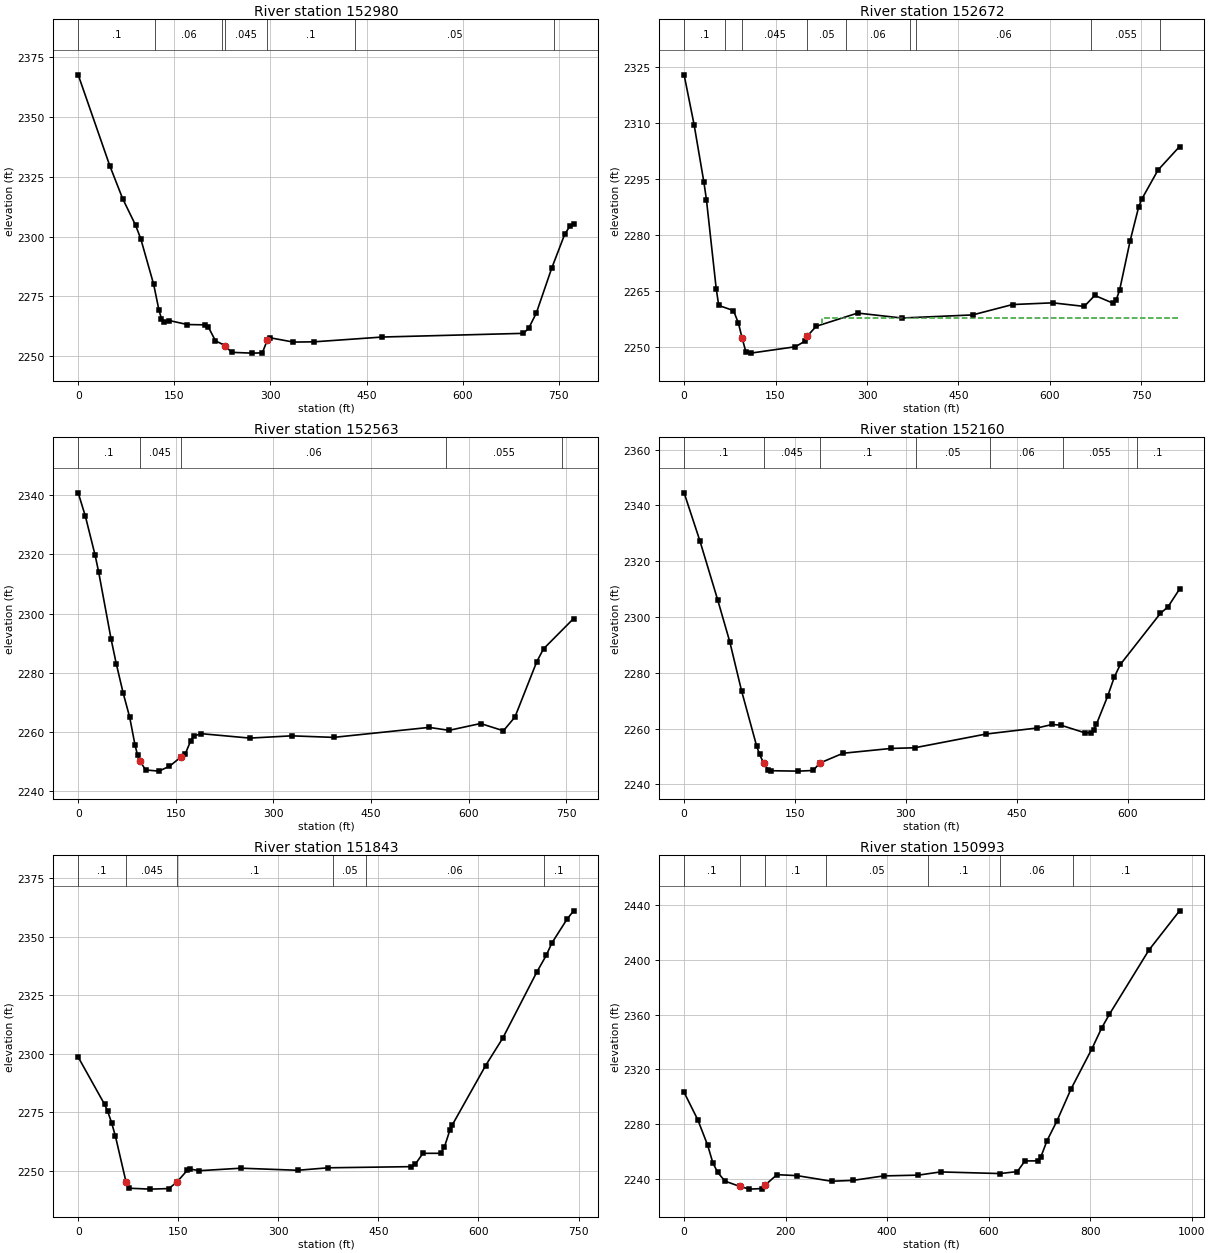
Type RM Length L Ch R = 1 ,152980  ,308.1,308.2,340.3
XS GIS Cut Line= 2
2385809.87012827593735.8017043772386576.48670527593835.024931133
#Sta/Elev= 30
       0 2367.58    49.3 2329.57    69.4 2315.81    89.6 2304.69    97.7 2298.97
   117.8 2279.96   125.9 2269.35   129.9 2265.66     134 2264.38     142 2264.88
   170.3  2263.2   198.5 2263.07   202.6 2262.37   214.2  2256.4   229.22254.408
   239.2 2251.58   271.1 2251.25   287.3 2251.36  294.862256.541   299.4 2257.67
   335.7 2255.87   367.9 2255.97   474.6 2257.98   694.6 2259.52   702.7 2261.57
   714.8 2268.01   738.7 2286.69   759.2 2301.02   767.2 2304.31     773 2305.22
#Mann= 7 ,-1 , 0
       0      .1       0  120.54     .06       0  224.17      .1       0
   229.2    .045       0  294.86      .1       0  431.43     .05       0
  742.32      .1       0
Bank Sta=229.2,294.86
XS Rating Curve= 0 ,0
Exp/Cntr=0.5,0.3

Type RM Length L Ch R = 1 ,152672  ,106.7,108.5,86.1
XS GIS Cut Line= 4
2385914.53133628594058.1947603822386071.72491953594080.272144049
2386241.69242737594278.3367085462386575.57299319 594485.56660904
#Sta/Elev= 30
       0 2322.99    16.4 2309.63    32.5 2294.19    36.6 2289.58    52.7 2265.66
    56.8 2261.23      81 2259.85    89.1 2256.48   95.242252.443   101.2 2248.86
   109.3 2248.46   182.6 2250.17   199.1 2251.76  202.242253.055   216.6 2255.64
   284.7 2259.19   357.2 2257.86   473.2 2258.69   538.7 2261.47   604.6 2261.93
   656.4 2260.97   673.6 2263.91   703.4 2261.85   708.5 2262.64   714.3 2265.28
   731.7 2278.58   745.8 2287.72   750.5 2289.64   777.3 2297.47   812.7 2303.78
#Mann= 9 ,-1 , 0
       0      .1       0   66.81     .06       0   95.24    .045       0
  202.24     .05       0  265.26     .06       0  371.31     .05       0
  380.02     .06       0  667.29    .055       0  781.28      .1       0
#XS Ineff= 2 ,-1
       0      69    2258     226  812.69    2258
Permanent Ineff=
       F       F
Bank Sta=95.24,202.24
XS Rating Curve= 0 ,0
Exp/Cntr=0.5,0.3

Type RM Length L Ch R = 1 ,152563  ,409.8,403.4,390.7
XS GIS Cut Line= 4
2385905.07630268594159.6033502072386075.11828545594192.305384547
2386263.79507345594360.7256513832386568.83219302594499.780491382
#Sta/Elev= 30
       0 2340.75    11.1  2332.8    26.1 2319.61    31.6 2313.86    50.6 2291.33
    58.5 2283.07    69.1 2273.17    79.1 2265.04    87.2 2255.74    91.3 2252.14
   94.712250.315   103.5 2247.21   123.9 2246.81   140.2 2248.44  157.422251.486
   164.6 2252.66   172.8 2257.01     178 2258.68   189.1 2259.45   263.8 2257.96
   328.1 2258.72   392.5  2258.2   539.2 2261.57     570 2260.58   618.3 2262.88
   653.4 2260.43   671.1 2265.06   704.7 2283.77   715.1  2288.1   761.3 2298.32
#Mann= 5 ,-1 , 0
       0      .1       0   94.71    .045       0  157.42     .06       0
  565.25    .055       0  743.55      .1       0
Bank Sta=94.71,157.42
XS Rating Curve= 0 ,0
Exp/Cntr=0.5,0.3

Type RM Length L Ch R = 1 ,152160  ,333.1,316.7,304.4
XS GIS Cut Line= 2
2385949.58540002594595.6979504672386614.17626244 594509.24175854
#Sta/Elev= 30
       0 2344.54    21.3 2327.36    45.5 2306.08    61.7  2291.2    77.8 2273.46
    98.1 2253.77     102 2250.81  107.712247.545   114.1 2245.22   118.1 2244.89
   154.5 2244.75   174.6 2244.98   183.5 2247.64     215 2251.16   280.2 2252.89
   311.8 2253.12   408.7 2258.06   477.1  2260.2   497.9 2261.47   509.4 2261.24
   541.7 2258.53   549.8 2258.51   553.8 2259.41   557.8  2261.6   572.9 2271.59
     582 2278.52   590.1 2282.99   644.2 2301.29   654.6 2303.67   670.2 2310.03
#Mann= 7 ,-1 , 0
       0      .1       0  107.71    .045       0   183.5      .1       0
  314.05     .05       0  413.42     .06       0  512.78    .055       0
  612.15      .1       0
Bank Sta=107.71,183.5
XS Rating Curve= 0 ,0
Exp/Cntr=0.3,0.1

Type RM Length L Ch R = 1 ,151843  ,866.9,850,832.2
XS GIS Cut Line= 2
2386156.38583943 594904.601860212386803.26643544594539.619322464
#Sta/Elev= 30
       0 2298.51    39.5 2278.34    44.1 2275.41      50 2270.54    55.8  2264.7
   71.882244.952    76.7 2242.44   108.3 2242.06   135.9  2242.3  147.75 2245.03
   163.5  2250.1     168 2250.62   181.8 2249.94   243.8 2251.01   328.9 2250.12
   374.7 2251.18   498.7 2251.67   505.1 2252.63   516.8 2257.37   543.2 2257.38
   548.9 2259.99     557 2267.13   560.9 2269.56   610.8 2294.92   636.5 2306.65
   687.2 2334.71   701.8  2342.1     710 2347.27     733 2357.57   742.7 2361.06
#Mann= 6 ,-1 , 0
       0      .1       0   71.88    .045       0  147.75      .1       0
  381.35     .05       0  431.61     .06       0  698.87      .1       0
Bank Sta=71.88,147.75
XS Rating Curve= 0 ,0
Exp/Cntr=0.3,0.1

Type RM Length L Ch R = 1 ,150993  ,555.5,556.9,559.7
XS GIS Cut Line= 2
2386869.98021278595436.9912153782387429.29143012594636.854036123
#Sta/Elev= 30
       0 2303.31      27 2283.29    46.5 2264.66    56.6 2251.97      66 2245.05
    80.6 2238.58  109.352234.807   128.4 2232.77   153.9 2233.18  159.35 2235.63
     183 2243.31   222.2 2242.62   290.5 2238.52   332.4 2239.13     393  2242.4
   461.7 2242.98   505.2 2245.31   622.5 2244.12   656.5 2245.56   671.6 2253.32
   697.2 2253.37   702.7 2256.01   715.1 2268.14   734.6 2282.45   762.3 2305.73
   803.5 2335.08   822.5 2350.05   837.9 2360.21   915.9 2407.08   976.2 2435.65
#Mann= 7 ,-1 , 0
       0      .1       0  109.35    .045       0  159.35      .1       0
  280.29     .05       0  480.21      .1       0  622.76     .06       0
  765.31      .1       0
Bank Sta=109.35,159.35
XS Rating Curve= 0 ,0
Exp/Cntr=0.3,0.1

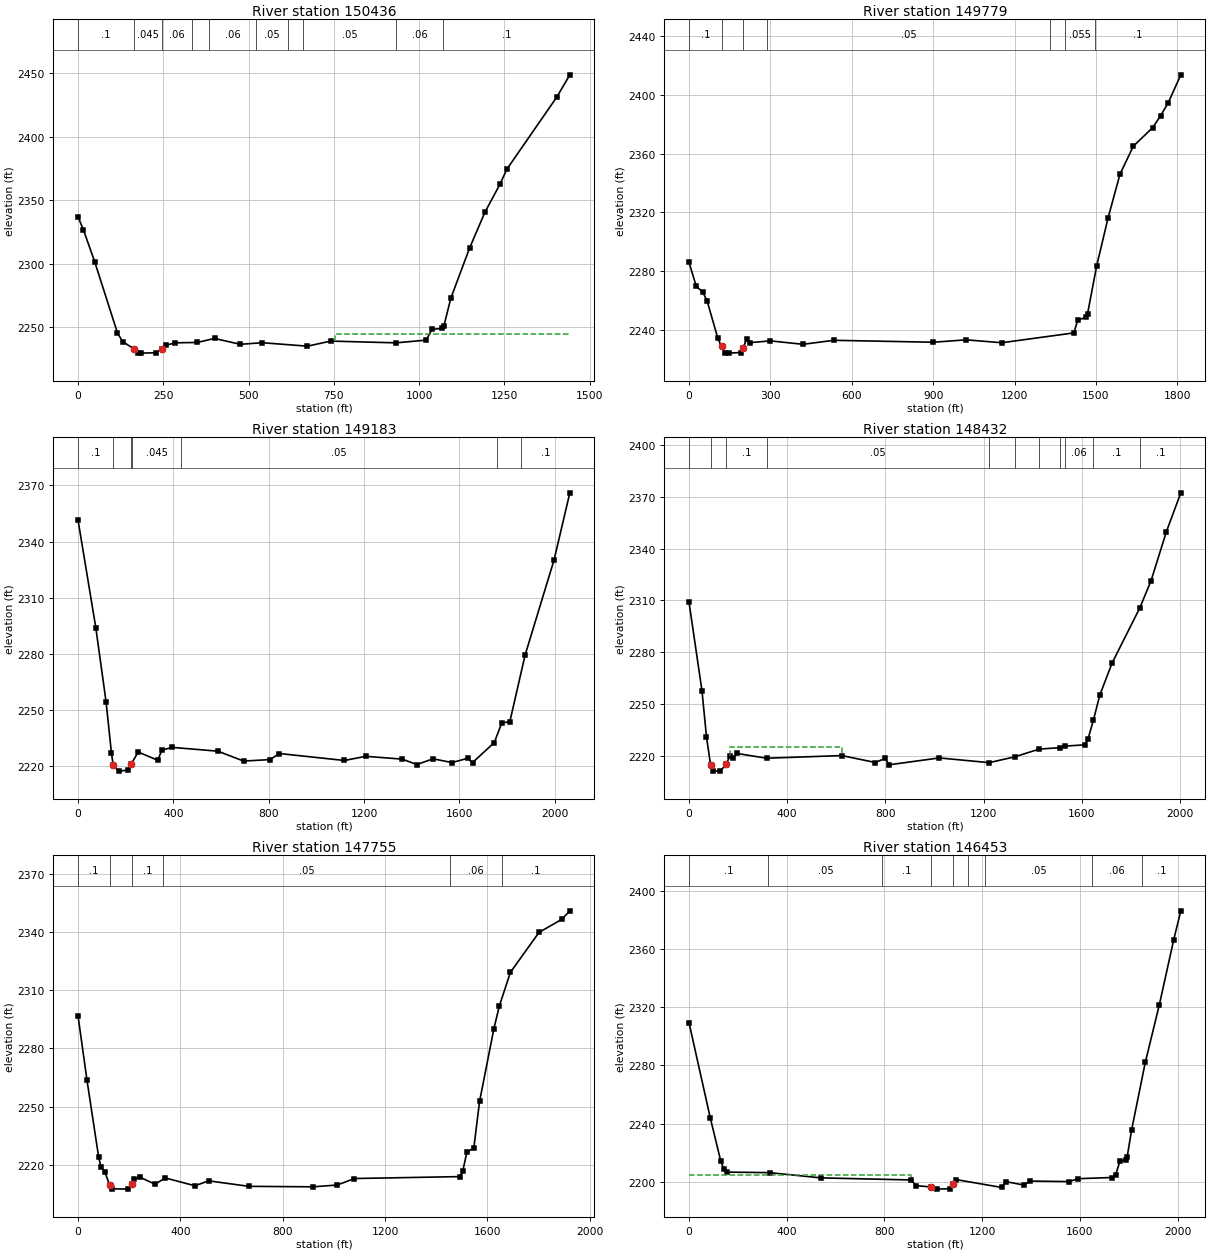
Type RM Length L Ch R = 1 ,150436  ,652.3,657.7,663.7
XS GIS Cut Line= 2
2387287.74315676595797.9229082172388158.26274118594648.660771042
#Sta/Elev= 30
       0 2336.91    15.7 2326.85      49 2301.46   115.7 2245.32   130.8 2238.53
  163.742232.831   174.4 2229.84   184.2 2229.43   229.6 2229.72  246.842232.931
   258.4 2235.65   284.8 2237.56   349.5 2237.85   400.2 2241.01   475.5  2236.4
   540.7 2237.63   672.4 2234.92     741 2238.93   932.1 2237.54  1020.8 2239.68
  1037.5 2248.17  1067.6 2248.95  1072.6 2250.95  1092.7 2272.59  1147.9 2312.37
  1193.1 2340.76  1237.2 2362.79    1257 2374.46  1403.4 2431.36  1441.7 2448.94
#Mann= 10 ,-1 , 0
       0      .1       0  163.74    .045       0  246.84     .06       0
  335.33    .055       0  384.09     .06       0  521.35     .05       0
  616.01     .06       0   658.6     .05       0  933.11     .06       0
 1070.36      .1       0
#XS Ineff= 2 , 0
                          753.27          2244.3
Permanent Ineff=
       F       F
Bank Sta=163.74,246.84
XS Rating Curve= 0 ,0
Exp/Cntr=0.3,0.1

Type RM Length L Ch R = 1 ,149779  ,580.8,596,611.9
XS GIS Cut Line= 2
2387795.53512019596174.2013551292389083.03779453594898.011978373
#Sta/Elev= 30
       0 2285.97      27 2269.59    49.9 2265.94    66.5 2259.84   106.4 2234.22
  119.792228.664   131.9 2224.48   146.8 2224.14   190.4 2224.56  199.652227.809
   212.9 2234.03   226.3 2231.32   300.2 2232.47   420.4 2230.16   533.9 2232.88
     900 2231.56  1021.8  2233.2    1153 2231.22  1418.2 2237.92    1433 2246.55
    1465 2248.71  1468.9 2250.84  1502.6 2283.59  1544.5 2316.19  1588.5 2346.06
  1637.8 2365.14  1709.3 2377.85  1738.5 2385.96  1766.1 2394.65  1812.8 2413.78
#Mann= 7 ,-1 , 0
       0      .1       0  119.79    .045       0  199.65      .1       0
  287.79     .05       0 1330.44     .06       0 1386.24    .055       0
 1496.71      .1       0
Bank Sta=119.79,199.65
XS Rating Curve= 0 ,0
Exp/Cntr=0.3,0.1

Type RM Length L Ch R = 1 ,149183  ,750.7,750.7,750.4
XS GIS Cut Line= 2
 2387988.8867676596670.3867144582389900.26713118595892.144176468
#Sta/Elev= 30
       0 2351.58    74.7 2294.07   117.7 2254.57   140.2 2227.34  147.982220.612
   170.4 2217.52   209.3 2218.04  223.972221.549   252.7 2227.71   334.6 2223.32
   351.8 2228.72     395  2230.2   587.3 2228.16   694.7 2222.89   805.7 2223.67
   845.1 2226.91  1118.2  2223.2  1207.2 2225.43  1360.7 2223.92  1422.1 2221.02
  1489.6 2224.11  1569.4 2222.08  1634.5 2224.36  1655.3 2222.06  1746.8 2232.78
  1778.1 2243.29  1811.9 2243.88  1876.1 2279.52  1997.3 2330.16  2063.7 2366.08
#Mann= 7 ,-1 , 0
       0      .1       0  147.98    .045       0  223.97      .1       0
  227.86    .045       0  431.68     .05       0 1756.48     .06       0
 1858.39      .1       0
Bank Sta=147.98,223.97
XS Rating Curve= 0 ,0
Exp/Cntr=0.3,0.1

Type RM Length L Ch R = 1 ,148432  ,676.2,676.8,678
XS GIS Cut Line= 2
2388325.22172487597342.498559207 2390175.6875121596573.684808135
#Sta/Elev= 30
       0 2309.04    52.9 2257.61    71.2 2231.02   87.992214.608    96.9 2211.23
   127.3 2211.06  151.992215.122   166.2 2219.94   178.4 2218.43   196.6 2221.28
   316.1 2218.54   622.1 2220.08   759.7 2216.06   798.6 2218.45     816 2214.75
  1019.9 2218.71  1223.1 2215.97  1327.1 2219.36  1426.7 2223.82  1509.5 2224.65
  1530.9 2225.55    1613 2226.31    1626 2229.82  1647.6 2240.61  1673.6 2255.08
  1723.7  2273.7  1836.9 2305.74  1882.8 2321.55    1945 2349.91  2003.8  2372.4
#Mann= 11 ,-1 , 0
       0      .1       0   87.99    .045       0  151.99      .1       0
   316.1     .05       0  1223.1    .055       0  1327.1     .05       0
  1426.7     .06       0  1509.5    .055       0  1530.9     .06       0
  1647.6      .1       0  1836.9      .1       0
#XS Ineff= 1 ,-1
     169     622    2225
Permanent Ineff=
       F
Bank Sta=87.99,151.99
XS Rating Curve= 0 ,0
Exp/Cntr=0.3,0.1

Type RM Length L Ch R = 1 ,147755  ,1289.9,1301.8,1291
XS GIS Cut Line= 2
2388599.97380003597958.057695538 2390372.8957791597215.406293705
#Sta/Elev= 30
       0 2296.86    35.1  2263.6    80.9 2223.74    89.7    2219   105.4 2216.07
  123.882209.482   132.9  2207.6   197.1 2207.42   211.82209.826   219.8 2212.43
   241.5 2213.57     301 2209.98   341.3 2213.18   456.9 2209.15   510.4 2211.69
   667.8 2208.86   918.4 2208.61  1013.2 2209.53  1080.4 2212.89    1493 2213.88
  1503.5 2216.57  1519.7 2226.45  1546.9 2228.62  1569.4 2252.63    1625 2289.92
  1646.6 2301.83    1690 2319.26  1801.7 2339.81  1890.4 2346.56  1922.2 2350.96
#Mann= 6 ,-1 , 0
       0      .1       0  123.88    .045       0   211.8      .1       0
  330.74     .05       0 1454.36     .06       0 1658.66      .1       0
Bank Sta=123.88,211.8
XS Rating Curve= 0 ,0
Exp/Cntr=0.3,0.1

Type RM Length L Ch R = 1 ,146453  ,1219.6,1214.5,1201.2
XS GIS Cut Line= 2
2388934.39898419598748.1948947912390797.88475853597987.910982296
#Sta/Elev= 30
       0 2309.33    87.2  2243.8   130.1 2214.14   142.9 2208.47   155.9 2206.63
   329.6 2206.26   540.4 2202.67   909.5 2201.24   929.2  2197.3  990.332196.448
  1015.6 2194.94  1067.4 2195.23 1082.182198.148  1093.4 2201.48  1279.1 2196.09
  1296.4 2200.07  1369.8 2197.79  1395.8 2200.48  1555.6 2200.12  1591.8 2202.11
  1729.4 2202.93  1745.7 2204.62    1763 2213.99  1788.9 2215.07  1793.2 2217.29
  1811.5 2235.85  1867.1 2281.98  1924.8  2321.7  1983.5 2366.32  2012.6 2386.19
#Mann= 9 ,-1 , 0
       0      .1       0  324.88     .05       0  790.85      .1       0
  990.33    .045       0 1082.18     .06       0 1140.27      .1       0
 1212.92     .05       0  1649.9     .06       0 1853.74      .1       0
#XS Ineff= 2 , 0
          908.31 2204.52
Permanent Ineff=
       F       F
Bank Sta=990.33,1082.18
XS Rating Curve= 0 ,0
Exp/Cntr=0.3,0.1

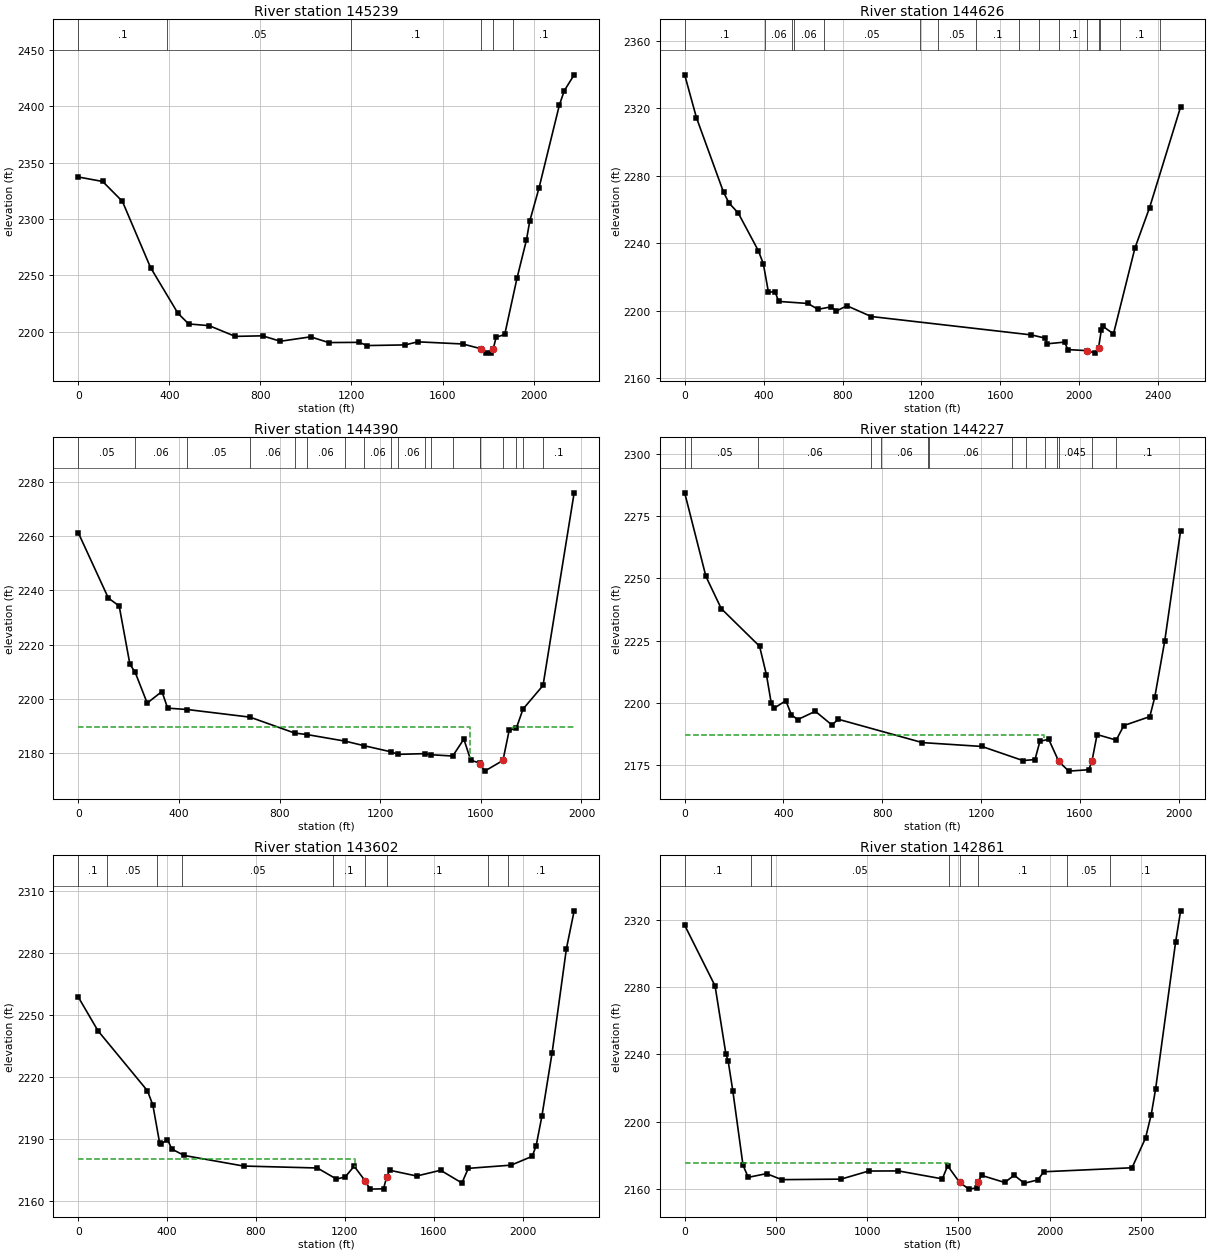
Type RM Length L Ch R = 1 ,145239  ,613.6,612.6,611.5
XS GIS Cut Line= 2
2389133.89202353599752.6285814642391167.34858653598973.058618292
#Sta/Elev= 30
       0 2337.18   107.3 2333.21     194 2315.57   317.7 2256.87   437.9 2216.37
     485 2206.91   575.1 2205.39   689.5 2195.88   809.4 2196.38   887.6 2191.56
  1020.5 2195.48  1099.9  2190.4    1234 2190.59  1268.9 2187.75    1436 2188.32
    1491 2191.06  1688.8 2189.15    17692184.885  1791.6 2181.04  1813.6  2181.4
 1822.132184.567  1835.2 2195.09    1873 2197.61  1926.8 2247.46  1968.4 2281.38
  1982.7    2298  2022.9 2326.99  2112.9 2400.91  2134.3 2413.62  2177.8 2427.74
#Mann= 6 ,-1 , 0
       0      .1       0   387.9     .05       0 1199.49      .1       0
    1769    .045       0 1822.13     .06       0 1909.63      .1       0
Bank Sta=1769,1822.13
XS Rating Curve= 0 ,0
Exp/Cntr=0.3,0.1

Type RM Length L Ch R = 1 ,144626  ,256.5,236.3,210.6
XS GIS Cut Line= 3
2389654.75745159601037.1066555382390322.83059052599985.424375713
2391487.20883918599483.445720881
#Sta/Elev= 30
       0  2339.9    59.6 2314.52   196.9 2270.36   224.7 2263.93   271.1 2258.08
     373 2235.77   398.6 2227.99   424.7 2211.03   457.6 2211.51   476.5 2205.64
   624.7 2204.42   675.5 2200.96   740.6 2202.38   769.5 2199.99   822.4 2203.05
   945.7 2196.69  1757.5 2185.79  1826.1 2183.93  1838.3 2180.53  1925.4 2181.53
  1942.8 2177.08 2041.422176.474  2078.7    2175 2097.922178.224  2112.2 2188.82
  2121.3 2190.78  2173.6 2186.41  2282.5 2237.32  2356.6 2261.23  2513.9  2320.9
#Mann= 16 ,-1 , 0
       0      .1       0  406.14     .06       0  544.74     .05       0
  555.63     .06       0  705.11     .05       0 1193.44      .1       0
 1285.07     .05       0 1478.05      .1       0  1694.7     .05       0
 1797.11     .12       0 1899.52      .1       0 2041.42    .045       0
 2097.92      .1       0 2104.33    .055       0 2206.74      .1       0
 2411.56      .1       0
Bank Sta=2041.42,2097.92
XS Rating Curve= 0 ,0
Exp/Cntr=0.5,0.3

Type RM Length L Ch R = 1 ,144390  ,181.8,163.1,158.2
XS GIS Cut Line= 6
2390010.01231852600969.9430759552390874.18709937600324.555259123
2391035.36033344600181.3314642162391120.48844403599956.581585631
2391231.10469261599799.5182514642391424.90614226599651.614675879
#Sta/Elev= 30
       0 2261.37   119.9 2237.16   162.8 2234.27   205.6 2212.65   225.6 2209.92
   274.2 2198.39   332.7 2202.66   355.4 2196.52   434.3    2196   682.9 2193.19
   860.1 2187.32   907.6 2186.78  1061.3 2184.32  1135.3 2182.66  1244.5 2180.35
    1270 2179.44  1379.6 2179.72    1403  2179.3  1488.4 2178.83  1532.7 2185.08
  1559.9 2177.26  1595.4 2176.27 1597.882175.852  1615.5 2173.25 1688.05  2177.2
  1712.7  2188.3  1741.5 2189.19  1767.8 2196.18  1847.3 2204.89    1971 2276.06
#Mann= 19 ,-1 , 0
       0     .05       0   225.6     .06       0   434.3     .05       0
   682.9     .06       0   860.1     .05       0   907.6     .06       0
  1061.3     .05       0  1135.3     .06       0  1244.5     .12       0
    1270     .06       0  1379.6     .12       0    1403     .06       0
  1488.4     .12       0  1595.4    .055       0 1597.88    .045       0
 1688.05     .06       0  1741.5    .055       0  1767.8     .06       0
  1847.3      .1       0
#XS Ineff= 2 , 0
       0    1557  2189.4 1728.05       0  2189.4
Permanent Ineff=
       F       F
Bank Sta=1597.88,1688.05
XS Rating Curve= 0 ,0
Exp/Cntr=0.5,0.3

Type RM Length L Ch R = 1 ,144227  ,598.5,625.3,644.4
XS GIS Cut Line= 6
2390076.18508643601064.7644086332391068.65127736600263.034056708
 2391169.0382157600174.8154011222391220.48266661600057.184402794
2391318.88043568599927.2417493022391557.67851451599734.493775204
#Sta/Elev= 30
       0 2284.45      86  2250.8   148.1 2237.84   303.2  2222.7   331.2 2211.12
   350.1 2200.04   362.8 2197.81   409.6  2200.8   432.2 2195.06   457.9 2193.19
     529 2196.52   596.3    2191   621.6 2193.32   962.4 2183.92  1203.3 2182.37
  1369.3  2176.7  1418.3 2177.09  1438.2 2184.43  1473.8 2185.26 1514.652176.323
    1555 2172.44  1636.2 2173.01 1649.312176.653  1669.7 2187.16  1747.1 2184.93
  1777.9 2190.78  1883.2 2194.38  1903.1 2202.15  1943.6 2224.85  2007.9 2269.25
#Mann= 14 ,-1 , 0
       0      .1       0   27.39     .05       0  295.41     .06       0
  754.65     .05       0  796.34     .06       0  984.27     .05       0
  988.58     .06       0 1324.84     .05       0 1381.77     .06       0
 1460.35     .05       0 1507.48     .06       0 1514.65    .045       0
 1649.31     .05       0 1745.44      .1       0
#XS Ineff= 2 , 0
         1455.75 2186.84
Permanent Ineff=
       F       F
Bank Sta=1514.65,1649.31
XS Rating Curve= 0 ,0
Exp/Cntr=0.5,0.3

Type RM Length L Ch R = 1 ,143602  ,736.9,740.9,744.2
XS GIS Cut Line= 2
2390471.97891426601388.8828548792392243.94912362600032.157221884
#Sta/Elev= 30
       0 2258.81      89 2242.43   311.5 2213.43     336 2206.47   366.2 2188.26
   371.2 2187.56   401.5 2189.84   421.6 2185.19     477 2182.12     744 2177.01
  1076.2 2176.06  1162.2  2170.7  1201.8 2171.77  1241.7 2176.94 1291.842169.748
  1313.3 2165.84  1373.8 2165.99 1387.832171.605  1401.5 2174.97  1523.2 2172.19
  1630.7 2174.96  1726.7 2168.81  1755.3 2175.89  1948.1 2177.44    2043 2181.72
  2060.6 2186.81  2086.3 2200.98  2132.5 2231.83  2196.9 2282.17  2231.7 2300.47
#Mann= 9 ,-1 , 0
       0      .1       0  130.95     .05       0   356.4     .06       0
  469.12     .05       0 1145.48      .1       0 1291.84    .045       0
 1387.83      .1       0 1843.47     .05       0 1934.56      .1       0
#XS Ineff= 2 , 0
         1243.36 2180.54
Permanent Ineff=
       F       F
Bank Sta=1291.84,1387.83
XS Rating Curve= 0 ,0
Exp/Cntr=0.3,0.1

Type RM Length L Ch R = 1 ,142861  ,785.5,783.8,779.9
XS GIS Cut Line= 2
2390659.47296184602032.5452814552392933.58980468600543.323522374
#Sta/Elev= 30
       0 2316.79   166.5 2280.72     226 2240.11   238.2 2236.07   263.6 2218.44
   319.5 2174.15   348.2 2166.82   448.5 2169.03     532 2165.45   857.3 2165.76
    1008 2170.56  1170.6 2170.65  1412.2 2165.92  1441.4 2173.67 1507.082163.789
    1558 2159.81  1600.9 2160.59 1607.022163.992  1627.3 2167.98  1753.9 2163.77
  1806.5 2168.09  1861.4  2163.3  1935.6  2165.3  1968.3 2170.14    2452 2172.52
  2525.9 2190.18  2557.2 2204.15  2581.1 2219.31    2691  2306.9  2718.3 2325.36
#Mann= 8 ,-1 , 0
       0      .1       0  362.65     .06       0  471.38     .05       0
 1449.89      .1       0 1507.08    .045       0 1607.02      .1       0
 2094.46     .05       0 2330.69      .1       0
#XS Ineff= 2 , 0
         1444.88 2175.43
Permanent Ineff=
       F       F
Bank Sta=1507.08,1607.02
XS Rating Curve= 0 ,0
Exp/Cntr=0.3,0.1

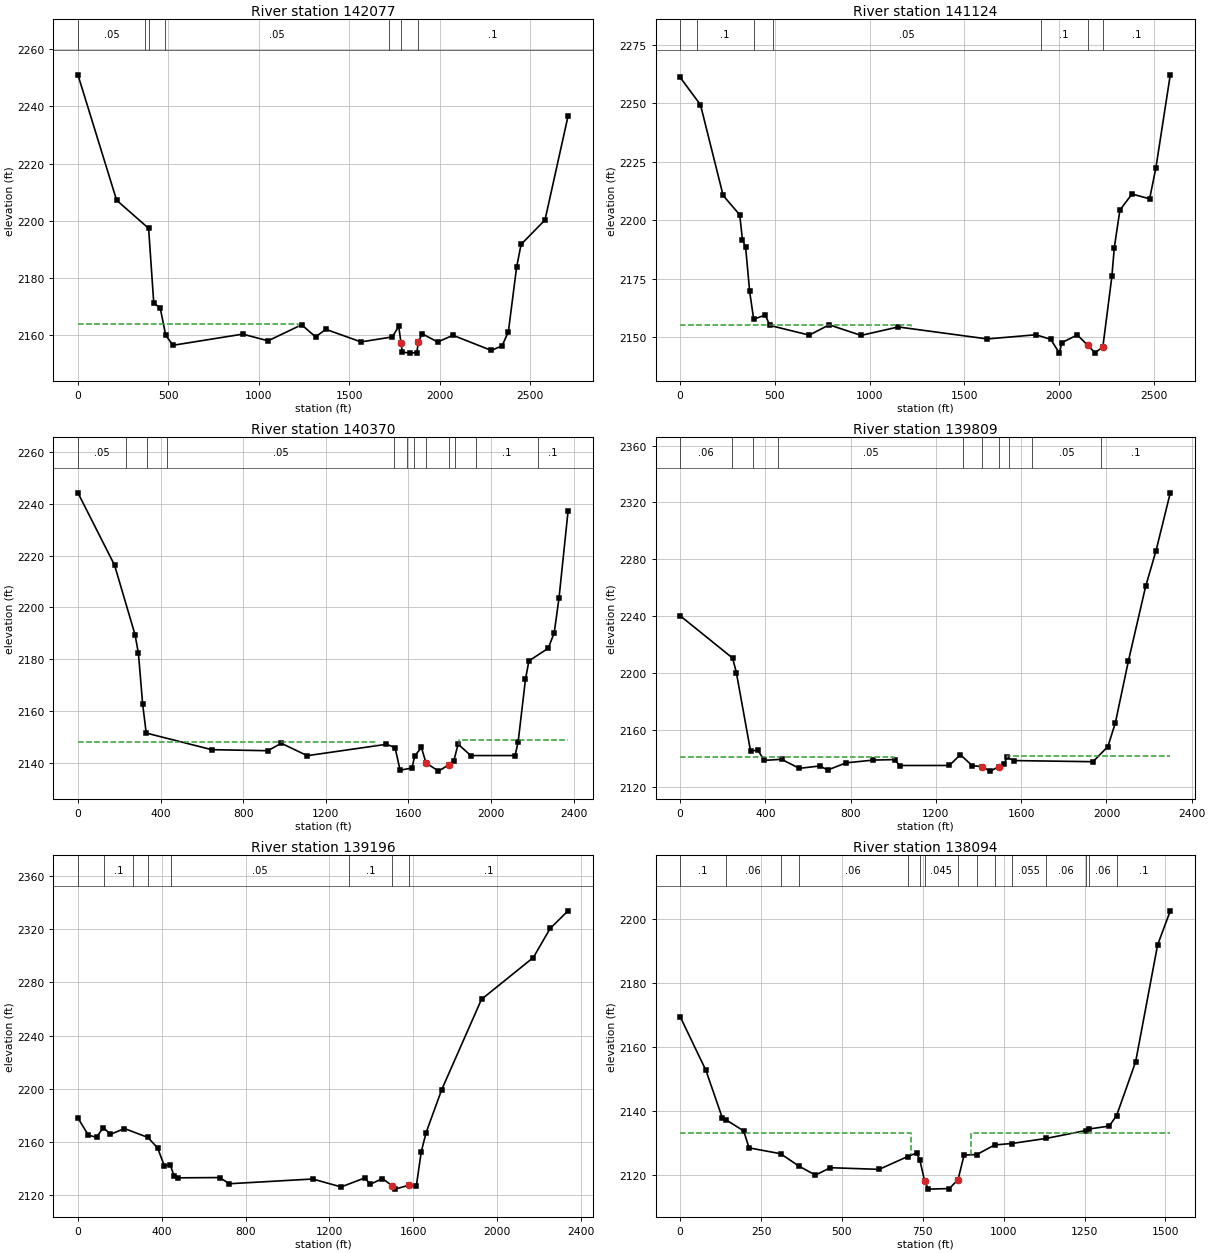
Type RM Length L Ch R = 1 ,142077  ,942.6,952.5,963.5
XS GIS Cut Line= 2
2391000.05692637602871.396294042 2393161.8984032601239.728953704
#Sta/Elev= 30
       0 2250.94   213.8 2207.19   390.7 2197.38   419.2 2171.16   454.4 2169.73
   484.9 2160.11   525.4 2156.58   910.4 2160.47  1050.8 2158.14  1236.2 2163.73
  1313.1 2159.52  1370.3 2162.14  1564.2 2157.75  1737.3 2159.49  1772.9 2163.17
 1785.682157.257  1792.5 2154.25  1832.5 2153.84  1872.9 2154.03 1881.562157.836
  1902.7 2160.58  1987.9 2157.73  2072.5 2160.06  2284.9 2154.78  2344.1  2156.4
  2378.8 2161.33  2424.1 2183.76    2449 2191.78  2581.2  2200.3  2708.5 2236.55
#Mann= 7 ,-1 , 0
       0     .05       0  370.91    .055       0  392.33     .06       0
  483.22     .05       0 1718.65      .1       0 1785.68    .045       0
 1881.56      .1       0
#XS Ineff= 2 , 0
         1214.25 2163.97
Permanent Ineff=
       F       F
Bank Sta=1785.68,1881.56
XS Rating Curve= 0 ,0
Exp/Cntr=0.3,0.1

Type RM Length L Ch R = 1 ,141124  ,749.2,754,745
XS GIS Cut Line= 2
 2391084.6131877603117.5582032952393525.56893569602261.243642956
#Sta/Elev= 30
       0 2261.05   107.3 2249.33   226.9 2210.59   314.4 2202.33   328.7 2191.71
   345.6 2188.41   366.8 2169.61     388 2157.71   449.4 2159.54   472.8 2155.09
   681.6 2150.93   786.5 2155.34   954.6 2150.81    1151 2154.42  1621.6  2149.3
  1877.2 2151.09  1955.7 2149.14  2001.8 2143.24  2013.9 2147.71  2096.3 2151.01
 2151.012146.584  2189.6 2143.36 2230.972145.914  2278.6 2176.02  2291.4 2188.34
    2321 2204.34  2384.6 2211.22  2477.8 2209.17  2511.1  2222.5  2586.8 2262.14
#Mann= 7 ,-1 , 0
       0      .1       0   86.64      .1       0  389.31     .06       0
   490.2     .05       0 1902.63      .1       0 2151.01    .045       0
 2230.97      .1       0
#XS Ineff= 2 , 0
         1217.64  2155.3
Permanent Ineff=
       F       F
Bank Sta=2151.01,2230.97
XS Rating Curve= 0 ,0
Exp/Cntr=0.3,0.1

Type RM Length L Ch R = 1 ,140370  ,572.5,561.6,543.5
XS GIS Cut Line= 3
2391410.77821776603560.3411103792393152.29310745603119.786545292
2393711.80150285602983.010900214
#Sta/Elev= 30
       0 2244.22   177.4 2216.31   276.4 2189.52   292.9 2182.29   313.5 2162.63
   330.5 2151.56   647.7 2145.16   919.3 2144.75   984.5 2147.62  1109.9 2142.84
  1493.6 2147.23  1534.8 2145.99  1559.6 2137.23  1617.4 2138.11  1629.7 2142.66
  1662.7 2146.03  1684.62140.077  1745.3 2136.88 1796.372139.379  1819.5 2140.84
  1840.1 2147.28  1901.8 2142.88    2116 2142.89    2131 2148.24  2166.4 2172.36
    2183 2179.39  2276.6 2184.28  2305.4 2190.21  2328.6 2203.58  2372.4 2237.11
#Mann= 12 ,-1 , 0
       0     .05       0  232.36      .1       0  332.06     .06       0
  431.75     .05       0  1528.4    .045       0 1595.16     .05       0
  1628.1    .045       0  1684.6    .045       0 1796.37     .07       0
 1827.47      .1       0  1927.1      .1       0 2225.98      .1       0
#XS Ineff= 2 ,-1
       0 1440.08 2147.96 1842.85 2372.36 2148.84
Permanent Ineff=
       F       F
Bank Sta=1684.6,1796.37
XS Rating Curve= 0 ,0
Exp/Cntr=0.3,0.1

Type RM Length L Ch R = 1 ,139809  ,611,612.8,614
XS GIS Cut Line= 2
2392063.27756894604435.4938876332394000.02041462603196.011458457
#Sta/Elev= 30
       0 2240.47   246.2 2210.72   263.6  2200.6   330.2 2145.45   364.9 2146.15
   393.9 2138.92     476 2139.66   558.9 2133.33   654.7 2134.98   692.7 2132.19
   778.2 2137.18   906.4 2139.12  1006.2 2139.48  1029.9 2135.32  1262.6 2135.34
  1314.7 2142.93  1369.8 2135.23 1415.64 2134.55  1453.7 2131.37 1495.622134.473
  1520.3  2136.6  1533.3    2141  1566.5 2138.78    1937 2137.98  2006.8 2148.66
  2041.8 2165.34  2103.2 2208.87  2183.9 2261.11  2232.7 2286.24  2299.4 2326.79
#Mann= 10 ,-1 , 0
       0     .06       0  244.16      .1       0  344.04     .06       0
  460.61     .05       0 1326.41      .1       0 1415.64    .045       0
 1495.62     .07       0 1542.86      .1       0 1651.09     .05       0
 1975.76      .1       0
#XS Ineff= 2 , 0
         1003.39 2141.14 1534.77         2142.09
Permanent Ineff=
       F       F
Bank Sta=1415.64,1495.62
XS Rating Curve= 0 ,0
Exp/Cntr=0.3,0.1

Type RM Length L Ch R = 1 ,139196  ,1130.5,1102.5,1112.3
XS GIS Cut Line= 3
2392258.00388554604954.2750023012393830.07029518604042.222036377
 2394251.6875622 603736.54613854
#Sta/Elev= 30
       0 2178.14    49.8 2165.26    88.7 2163.68   121.1 2170.96   155.2 2165.85
     222 2170.22   333.7 2163.55   380.1 2155.67   412.4 2142.13   440.2 2143.11
   458.7 2134.58   477.1 2133.22   676.3 2133.43   722.3 2128.79    1120 2132.35
  1255.6  2126.4  1369.7 2133.21  1393.7 2128.32  1452.9 2132.67  1500.52127.114
    1513 2124.75 1581.812127.821  1614.8 2127.47  1637.9 2152.75    1661 2167.12
  1735.5 2199.41  1925.4  2267.2  2172.6 2298.55  2252.8 2320.34  2338.2  2333.6
#Mann= 8 ,-1 , 0
       0      .1       0  122.99      .1       0  264.72      .1       0
  335.63     .06       0  441.95     .05       0 1292.52      .1       0
  1500.5    .045       0 1581.81      .1       0
Bank Sta=1500.5,1581.81
XS Rating Curve= 0 ,0
Exp/Cntr=0.5,0.3

Type RM Length L Ch R = 1 ,138094  ,95.3,103.5,95.7
XS GIS Cut Line= 6
2392684.83275628605737.1392502042393061.26769894605434.203832462
2393257.85457611605301.9695168732393426.44544628605183.170213789
2393902.81785309604926.9919203822393946.36763477 604907.21079196
#Sta/Elev= 30
       0 2169.45    79.5 2152.74   130.8 2137.75   141.1 2137.33   196.4 2133.82
     213 2128.54   310.5 2126.72   367.3 2122.84   418.3 2120.06   464.5 2122.36
   615.1 2121.84   702.8 2125.82     731 2126.94   740.8 2124.82  755.812118.144
   767.1 2115.68     832 2115.85  858.932118.626   877.8 2126.32   916.9 2126.45
   972.1 2129.45  1024.7  2129.9  1131.1 2131.48  1253.7 2133.94  1262.8  2134.4
  1326.4 2135.34  1349.2 2138.62  1408.1 2155.41  1475.9  2191.8  1515.1 2202.44
#Mann= 15 ,-1 , 0
       0      .1       0   141.1     .06       0   310.5     .05       0
   367.3     .06       0   702.8     .05       0   740.8     .06       0
  755.81    .045       0  858.93     .06       0   916.9    .055       0
   972.1     .05       0  1024.7    .055       0  1131.1     .06       0
  1253.7     .05       0  1262.8     .06       0  1349.2      .1       0
#XS Ineff= 2 ,-1
       0     714  2133.1     899 1515.07  2133.1
Permanent Ineff=
       F       F
Bank Sta=755.81,858.93
XS Rating Curve= 0 ,0
Exp/Cntr=0.5,0.3

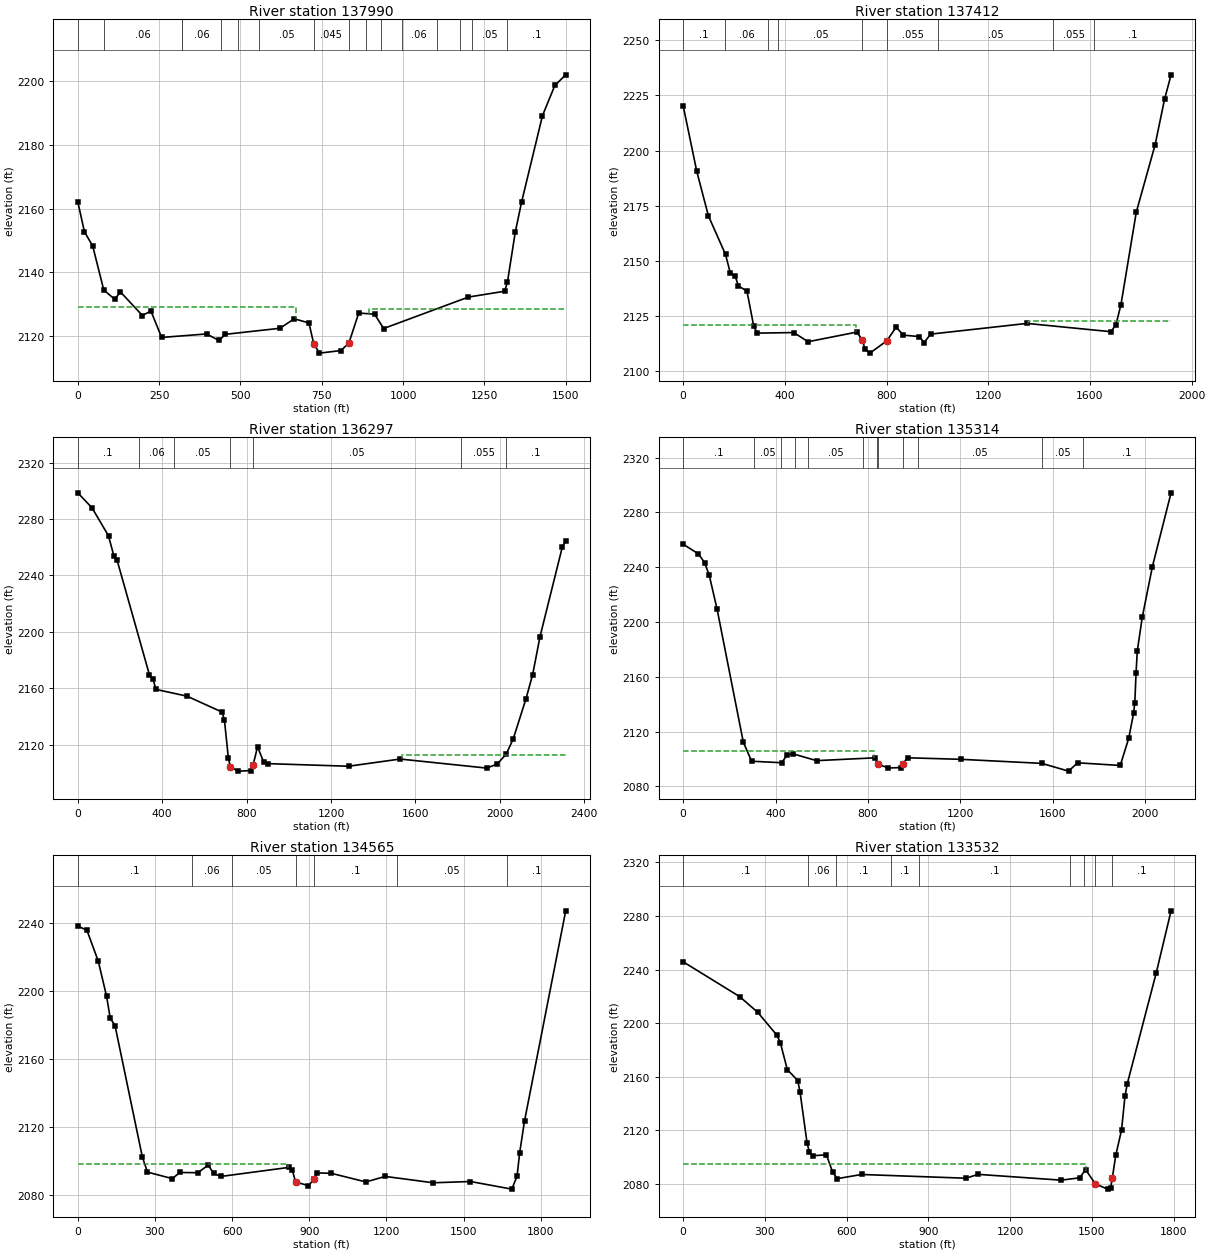
Type RM Length L Ch R = 1 ,137990  ,575.7,577.9,575
XS GIS Cut Line= 5
2392755.87624934605852.8735987992393143.79279634605484.151567206
2393270.22233352 605395.920116382393445.75610319 605277.23367396
2393950.96703503604955.549277961
#Sta/Elev= 30
       0 2162.12    20.3 2152.76    45.9 2148.23    79.8  2134.5   113.8 2131.55
   130.8 2133.91   198.7 2126.49   224.7 2127.91   257.8 2119.62   395.8 2120.71
   434.4 2118.66   453.3 2120.59   621.3 2122.49   665.6 2125.46   710.7 2124.16
  725.352117.655   743.1  2114.7   808.6  2115.5   833.32117.793   863.8 2127.27
   912.4 2126.91   940.4 2122.42  1201.2 2132.28  1312.2  2134.1  1320.9 2136.85
    1345 2152.58  1364.3 2161.97  1428.8 2189.16  1466.7 2198.61  1500.2 2201.95
#Mann= 16 ,-1 , 0
       0      .1       0   78.99     .06       0  319.55     .05       0
  320.89     .06       0  439.83     .05       0  492.16     .06       0
  558.02     .05       0  725.35    .045       0   833.3     .05       0
   887.3    .035       0  932.32    .055       0  995.59     .06       0
  1103.7     .05       0 1175.43     .06       0 1211.82     .05       0
 1319.94      .1       0
#XS Ineff= 2 , 0
          671.15 2129.08  894.87         2128.64
Permanent Ineff=
       F       F
Bank Sta=725.35,833.3
XS Rating Curve= 0 ,0
Exp/Cntr=0.5,0.3

Type RM Length L Ch R = 1 ,137412  ,1112,1114.8,1101.6
XS GIS Cut Line= 3
2392996.64446861 606299.576445552393708.27329469605774.635238215
2394530.93405095 605147.32415688
#Sta/Elev= 30
       0 2220.24    53.5 2190.56    99.2 2170.43   166.6 2152.94   185.1 2144.68
   205.1 2143.03   216.8 2138.74   250.9 2136.33   277.4  2120.5   290.9 2117.34
     435 2117.59   491.1 2113.44   683.6 2117.82  705.052114.026   715.4 2109.98
   734.3 2108.28  800.652113.825   837.7 2120.04   865.9 2116.42   928.7 2115.77
   947.8 2113.05   972.9 2116.88  1352.2 2121.73  1682.2 2117.98  1701.9 2121.11
  1721.7 2130.23    1782 2172.11  1856.2 2202.71  1893.3 2223.33  1918.8 2234.29
#Mann= 9 ,-1 , 0
       0      .1       0     164     .06       0   333.2      .1       0
  374.65     .05       0  705.05    .045       0  800.65    .055       0
    1003     .05       0 1454.64    .055       0 1616.34      .1       0
#XS Ineff= 2 , 0
          678.35 2120.93 1357.83         2123.04
Permanent Ineff=
       F       F
Bank Sta=705.05,800.65
XS Rating Curve= 0 ,0
Exp/Cntr=0.3,0.1

Type RM Length L Ch R = 1 ,136297  ,980.3,983.7,984.2
XS GIS Cut Line= 2
2393937.89357036607033.5707124622395604.48439726 605430.32916829
#Sta/Elev= 30
       0 2298.62    67.6 2287.93   145.5 2268.09   171.2  2253.7   186.4 2250.72
   339.1 2169.68   355.8 2166.77   370.3 2159.12   517.3 2154.35   683.9 2143.03
     695  2137.3   713.5 2110.56  722.922104.125   759.7 2101.14   823.2 2101.53
  830.762105.418     852 2118.48   880.9 2107.52   900.3 2106.46  1283.3 2104.61
  1527.5 2109.72  1938.3 2103.29  1988.6 2106.25  2030.9 2113.33  2063.6  2123.9
  2124.2 2152.44    2156 2169.69  2190.6 2196.46  2296.8 2260.35  2312.6 2264.39
#Mann= 7 ,-1 , 0
       0      .1       0   288.2     .06       0     458     .05       0
  722.92    .045       0  830.76     .05       0 1816.42    .055       0
 2030.42      .1       0
#XS Ineff= 1 ,-1
 1536.18 2312.56 2112.56
Permanent Ineff=
       F
Bank Sta=722.92,830.76
XS Rating Curve= 0 ,0
Exp/Cntr=0.3,0.1

Type RM Length L Ch R = 1 ,135314  ,739.1,749.1,756.3
XS GIS Cut Line= 2
2394657.68773445607612.9366797062396227.43328261606200.834845126
#Sta/Elev= 30
       0 2256.74      66 2249.71    92.8 2243.25   112.7 2234.12   146.6 2209.45
   260.2 2112.32   296.1 2098.35   426.5 2097.26   449.7 2102.94   475.6 2103.74
   577.2 2098.78     830 2100.84  843.772096.188   888.2  2093.4   942.5 2093.74
  951.74 2096.67   970.9 2100.87  1201.2 2099.75  1552.1 2096.79  1667.6 2091.13
    1707 2097.21  1891.4 2095.26  1928.2 2115.12  1949.1 2133.32  1954.5 2141.19
  1959.9 2162.92  1965.2 2178.89  1986.8 2203.49  2030.6 2240.44  2111.4 2294.25
#Mann= 12 ,-1 , 0
       0      .1       0  306.08     .05       0  424.18     .06       0
  481.79    .055       0  542.29     .05       0   778.5    .025       0
   838.6     .05       0  843.77    .045       0  951.74     .05       0
    1017     .05       0 1552.21     .05       0 1730.62      .1       0
#XS Ineff= 2 , 0
          826.74 2105.59
Permanent Ineff=
       F       F
Bank Sta=843.77,951.74
XS Rating Curve= 0 ,0
Exp/Cntr=0.3,0.1

Type RM Length L Ch R = 1 ,134565  ,1039,1033,1042
XS GIS Cut Line= 2
2395030.80345804608051.272089124 2396656.0387246607072.362301543
#Sta/Elev= 30
       0 2238.16    35.2 2235.85    79.3 2217.74     112  2196.9     126 2184.12
   144.7 2179.76   250.9  2102.6   270.8 2093.67   367.4 2089.83   396.8 2093.44
   466.5  2093.3   507.3 2097.78   527.7 2092.97   555.6 2091.09   822.1 2096.45
   833.7 2095.11  846.782087.869   896.5 2085.71  919.142089.428   929.2 2093.18
   985.3 2092.97  1120.6 2087.87  1195.1 2091.13  1382.1 2087.39  1526.9 2088.14
  1687.6 2083.66    1708 2091.16  1718.3 2105.07  1737.1  2123.7  1897.3 2247.19
#Mann= 7 ,-1 , 0
       0      .1       0  445.82     .06       0  598.12     .05       0
  846.78    .045       0  919.14      .1       0 1240.16     .05       0
 1668.18      .1       0
#XS Ineff= 2 , 0
           817.7 2098.23
Permanent Ineff=
       F       F
Bank Sta=846.78,919.14
XS Rating Curve= 0 ,0
Exp/Cntr=0.3,0.1

Type RM Length L Ch R = 1 ,133532  ,534.3,535.4,533.6
XS GIS Cut Line= 2
2395295.75273126608414.9396688792396977.57285845607801.531118795
#Sta/Elev= 30
       0 2245.74   207.6 2219.72   273.8 2207.98   343.8 2190.99   356.6 2185.34
   382.1 2165.25   420.5  2157.1     429 2148.23   454.5 2110.61     463 2103.69
   475.8 2100.98   525.5 2101.66   548.3 2088.81   565.2 2083.87   654.6 2086.97
  1038.2 2084.18  1081.8 2087.07    1387 2082.73  1455.1 2084.51  1476.4 2090.63
 1512.582079.926  1557.3 2076.04  1568.5 2077.12 1574.412084.103  1587.1 2101.16
  1608.4 2120.13  1621.1 2145.51  1629.6 2154.79  1736.1 2237.75  1790.2 2283.81
#Mann= 9 ,-1 , 0
       0      .1       0  459.32     .06       0  560.44      .1       0
  762.68      .1       0   863.8      .1       0 1420.92    .025       0
 1470.51      .1       0 1512.58    .045       0 1574.41      .1       0
#XS Ineff= 2 , 0
         1479.65 2094.76
Permanent Ineff=
       F       F
Bank Sta=1512.58,1574.41
XS Rating Curve= 0 ,0
Exp/Cntr=0.3,0.1