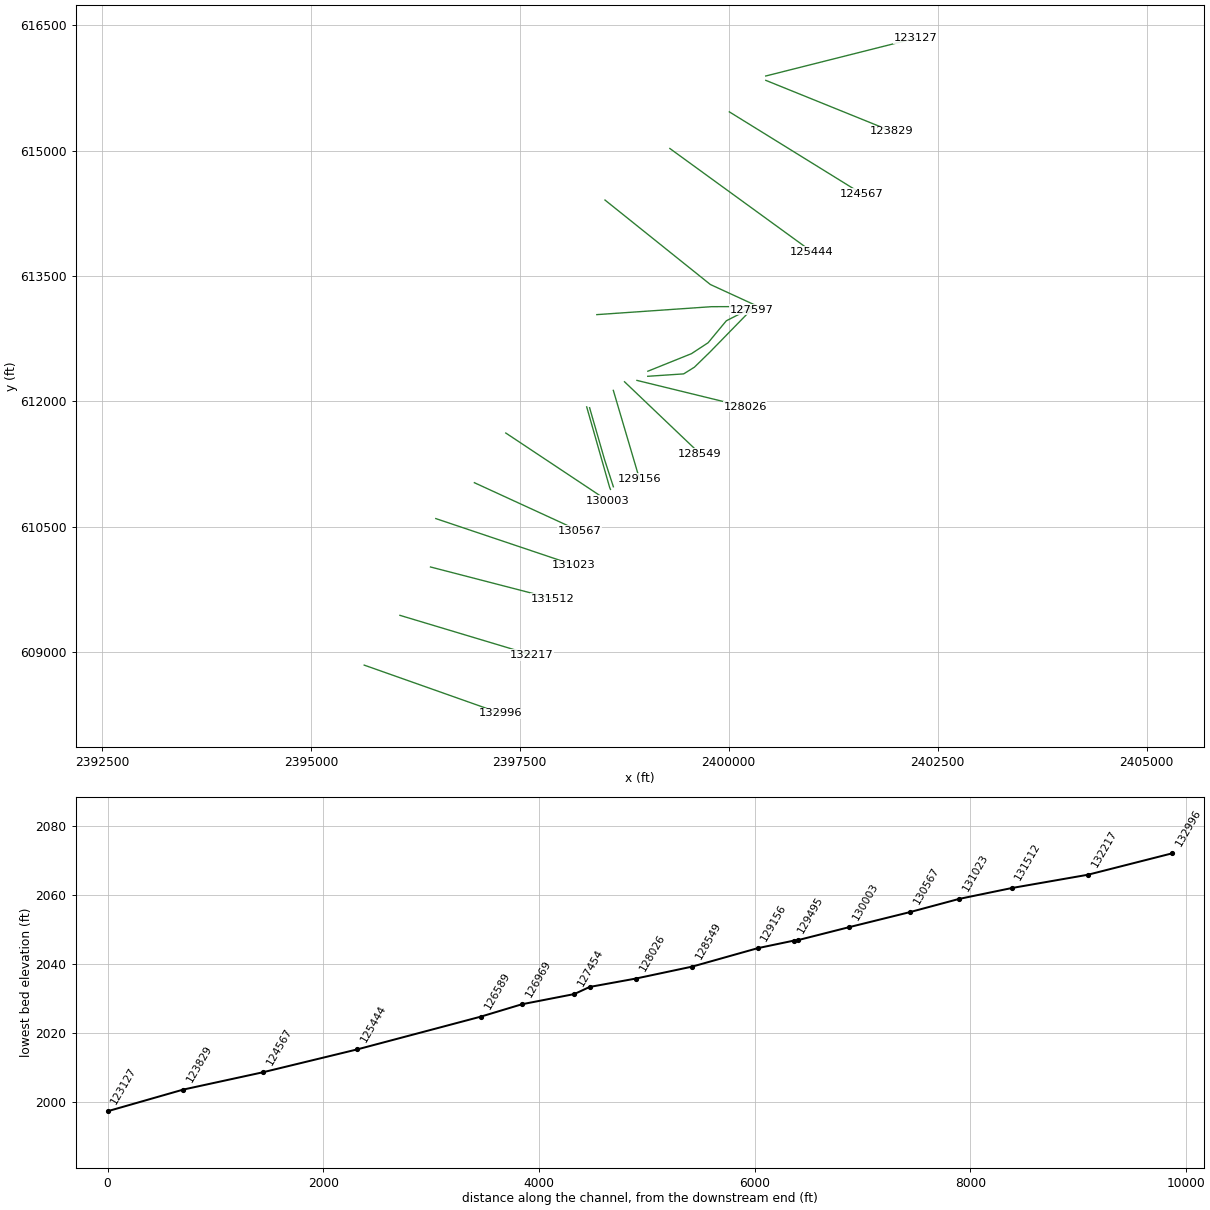
HEC-RAS study NFSBPOTOMC.prj: NFSBPOTOMC

--- NFSBPOTOMC.g01 (geometry) --- (continued)

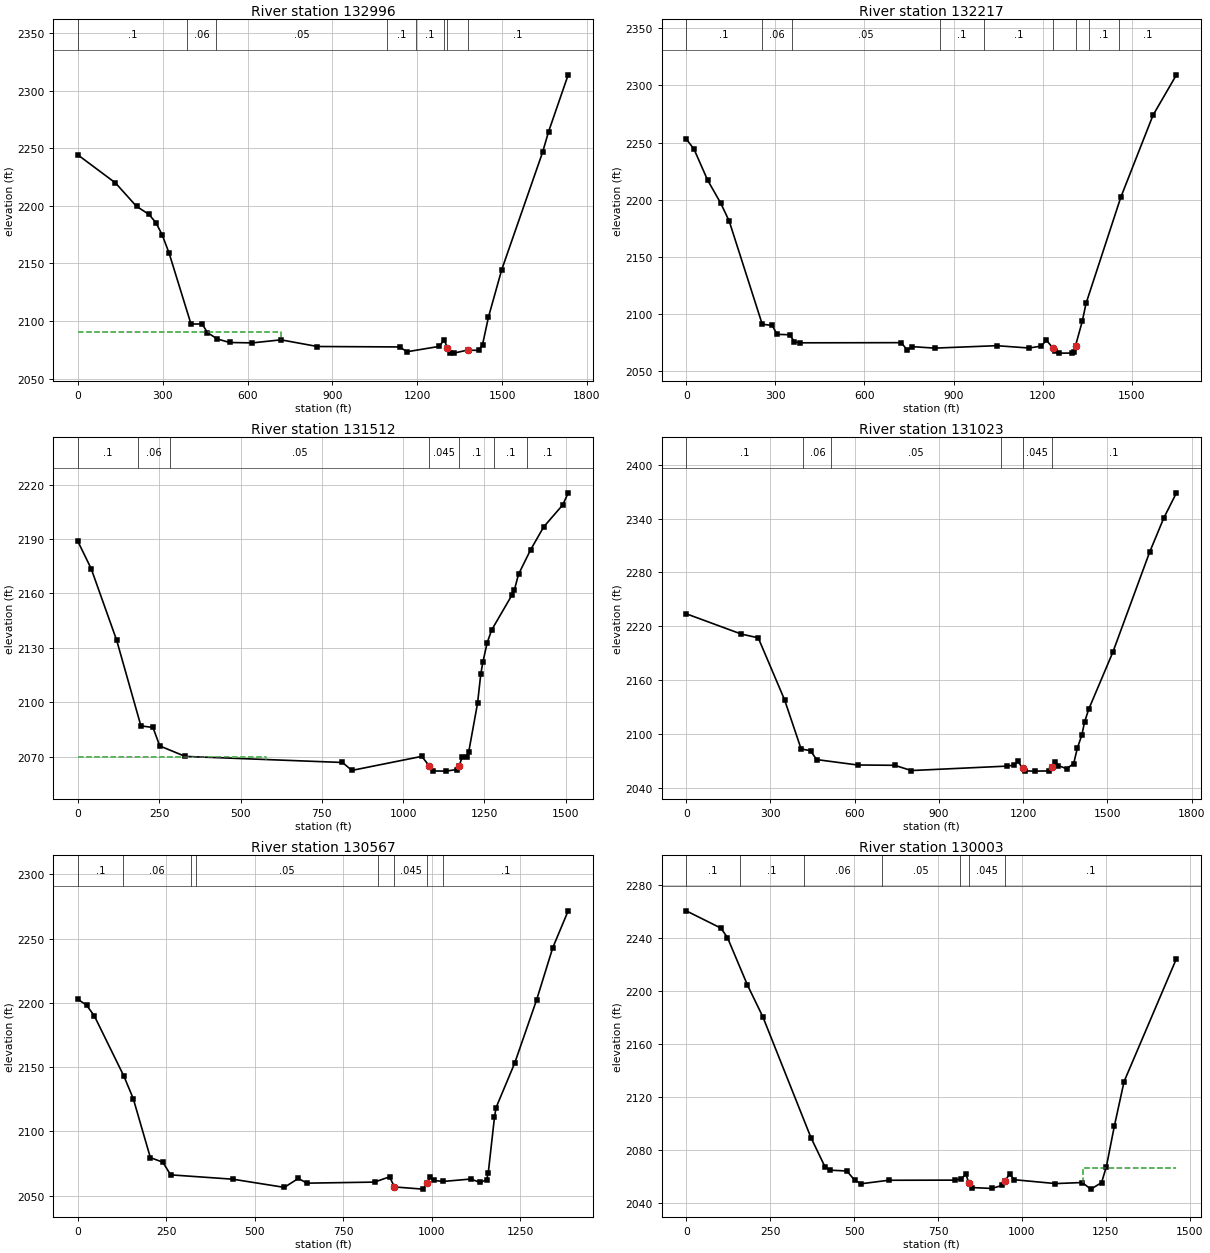
Type RM Length L Ch R = 1 ,132996  ,775.8,778.9,780.1
XS GIS Cut Line= 2
2395637.79601043608842.3558087952397272.16347662608264.636819884
#Sta/Elev= 30
       0 2244.12   132.5 2219.88   207.2 2199.49   251.1 2192.57   276.2 2185.17
     298 2174.72   322.5  2158.8   399.8 2097.36   439.2 2097.45     458 2089.91
   493.1 2084.38   536.3 2081.36   616.2    2081   718.1 2083.65   846.7 2077.87
    1138 2077.49  1163.2  2073.3    1278 2077.97    1295 2083.78 1306.09 2076.81
  1316.2 2072.35  1328.9 2072.12 1377.992074.755  1417.1 2074.47  1430.7 2079.54
  1451.6 2103.36  1498.6  2144.6  1642.9 2246.37  1664.1 2264.25  1733.5 2313.65
#Mann= 8 ,-1 , 0
       0      .1       0  386.74     .06       0  487.67     .05       0
 1093.26      .1       0 1194.19      .1       0 1295.12      .1       0
 1306.09    .045       0 1377.99      .1       0
#XS Ineff= 2 , 0
          716.81 2090.14
Permanent Ineff=
       F       F
Bank Sta=1306.09,1377.99
XS Rating Curve= 0 ,0
Exp/Cntr=0.3,0.1

Type RM Length L Ch R = 1 ,132217  ,702.2,705.6,706.3
XS GIS Cut Line= 2
2396065.66195261609437.8296834682397646.27427694608963.407403961
#Sta/Elev= 30
       0 2253.16    26.2 2244.35    72.1 2217.16   115.7 2197.28   144.6 2181.48
   255.9  2091.2   289.3 2090.13     306 2082.35   347.8 2081.98   364.5 2075.92
   382.3 2074.93   723.6 2075.07   744.5 2068.59   761.2 2071.59   836.4  2070.3
  1045.2 2072.43  1153.8 2070.39  1195.6 2072.07  1212.3 2077.38 1234.712070.244
  1241.5 2067.38    1256 2065.92    1300 2065.96  1304.1 2066.55 1310.632072.412
  1333.4  2093.9  1345.9 2109.32  1462.8 2202.07  1571.4 2273.93  1650.3 2309.26
#Mann= 9 ,-1 , 0
       0      .1       0  254.34     .06       0  354.51     .05       0
  855.38      .1       0 1001.57      .1       0 1234.71    .045       0
 1310.63      .1       0 1356.25      .1       0 1456.43      .1       0
Bank Sta=1234.71,1310.63
XS Rating Curve= 0 ,0
Exp/Cntr=0.3,0.1

Type RM Length L Ch R = 1 ,131512  ,492.3,488.4,485.8
XS GIS Cut Line= 2
2396431.29672003610016.6710454672397890.54741043609639.243322626
#Sta/Elev= 30
       0 2188.68    40.7  2173.7   119.2 2134.16   193.6 2087.01   230.8 2086.12
   251.5 2075.95     330 2070.17   813.4 2066.83   842.3 2062.46  1057.1 2070.19
 1079.482065.111  1090.2 2062.17  1131.5 2062.06  1164.5 2062.92 1171.432064.718
  1181.1 2069.59  1195.9 2070.01  1201.7 2072.85  1228.7 2099.52  1238.5 2115.48
  1245.1 2122.21  1258.2  2132.8    1272 2139.88  1334.3  2159.1  1342.2 2162.17
  1354.6 2170.57  1391.8 2184.09  1432.2 2196.76  1490.9 2208.91  1507.3  2215.5
#Mann= 7 ,-1 , 0
       0      .1       0  183.31     .06       0  283.05     .05       0
 1079.48    .045       0 1171.43      .1       0 1280.48      .1       0
 1380.23      .1       0
#XS Ineff= 2 , 0
          577.95 2070.05
Permanent Ineff=
       F       F
Bank Sta=1079.48,1171.43
XS Rating Curve= 0 ,0
Exp/Cntr=0.3,0.1

Type RM Length L Ch R = 1 ,131023  ,460,456.7,450.7
XS GIS Cut Line= 2
2396494.83990002610595.8319606332398149.70109162610039.275330961
#Sta/Elev= 30
       0 2234.04   196.5 2211.42   256.5 2207.27   350.2 2138.37   409.3 2083.51
   442.8 2081.66   464.1 2071.76   610.2 2065.74   742.6 2065.38   801.7 2059.54
  1143.9 2064.51  1168.9 2065.64  1181.5 2069.66 1198.59 2061.88    1207 2059.12
  1240.6  2058.9  1291.3 2059.11 1302.472063.522  1312.4 2069.51    1325 2065.15
  1354.6 2061.58  1379.9 2067.25  1392.6 2084.11  1409.2 2099.35  1418.6 2113.53
  1433.4 2127.75  1519.2 2191.11    1650 2302.31  1700.6 2340.47  1745.9 2368.64
#Mann= 6 ,-1 , 0
       0      .1       0  416.72     .06       0  517.38     .05       0
 1121.36      .1       0 1198.59    .045       0 1302.47      .1       0
Bank Sta=1198.59,1302.47
XS Rating Curve= 0 ,0
Exp/Cntr=0.3,0.1

Type RM Length L Ch R = 1 ,130567  ,570.4,563.4,554.6
XS GIS Cut Line= 2
2396956.64639109611025.1867449582398216.02674636610446.603584543
#Sta/Elev= 30
       0 2202.71    24.4 2198.15    46.3 2189.86   130.1 2142.86   156.4 2125.44
   204.8 2079.53     240 2076.04     262 2066.16   438.1 2062.78   583.4 2056.42
     623 2063.37   647.5 2059.71   838.7 2060.53     881 2064.65  894.662056.762
   975.1 2055.06  986.532059.458   995.7 2064.67    1006 2061.79  1032.4 2061.04
  1110.3  2062.9  1137.4 2060.25  1155.6 2062.47    1160 2067.85  1177.6 2111.07
    1182 2118.44  1234.9 2153.23  1296.5 2202.15  1342.5 2242.99  1385.9 2271.55
#Mann= 8 ,-1 , 0
       0      .1       0  127.97     .06       0  318.74      .1       0
  334.07     .05       0  849.31    .025       0  894.66    .045       0
  986.53    .025       0 1033.33      .1       0
Bank Sta=894.66,986.53
XS Rating Curve= 0 ,0
Exp/Cntr=0.3,0.1

Type RM Length L Ch R = 1 ,130003  ,504.5,476,439.3
XS GIS Cut Line= 2
2397332.44386786611619.8187577872398548.66945377610811.366634548
#Sta/Elev= 30
       0 2260.59   103.3 2247.56   122.8 2240.45   182.3  2204.7   228.5 2180.54
   371.6 2089.56   413.5 2067.49   429.3 2064.98   478.6 2064.36   502.3 2057.26
   521.7 2054.76   603.1 2057.38   801.5 2057.48   819.3  2058.4   833.3 2061.99
  841.932055.268   850.6 2051.87   910.5 2051.21     941 2053.51  949.672056.602
   963.1 2062.14   977.8 2057.77    1100 2054.88  1179.5 2055.66  1205.5 2050.69
  1237.3  2055.6  1251.6 2067.61  1275.6 2098.45  1304.4 2131.83  1460.4 2224.54
#Mann= 7 ,-1 , 0
       0      .1       0  159.79      .1       0     351     .06       0
  583.71     .05       0  816.41      .1       0  841.93    .045       0
  949.67      .1       0
#XS Ineff= 2 , 0
                         1181.23         2066.65
Permanent Ineff=
       F       F
Bank Sta=841.93,949.67
XS Rating Curve= 0 ,0
Exp/Cntr=0.5,0.3

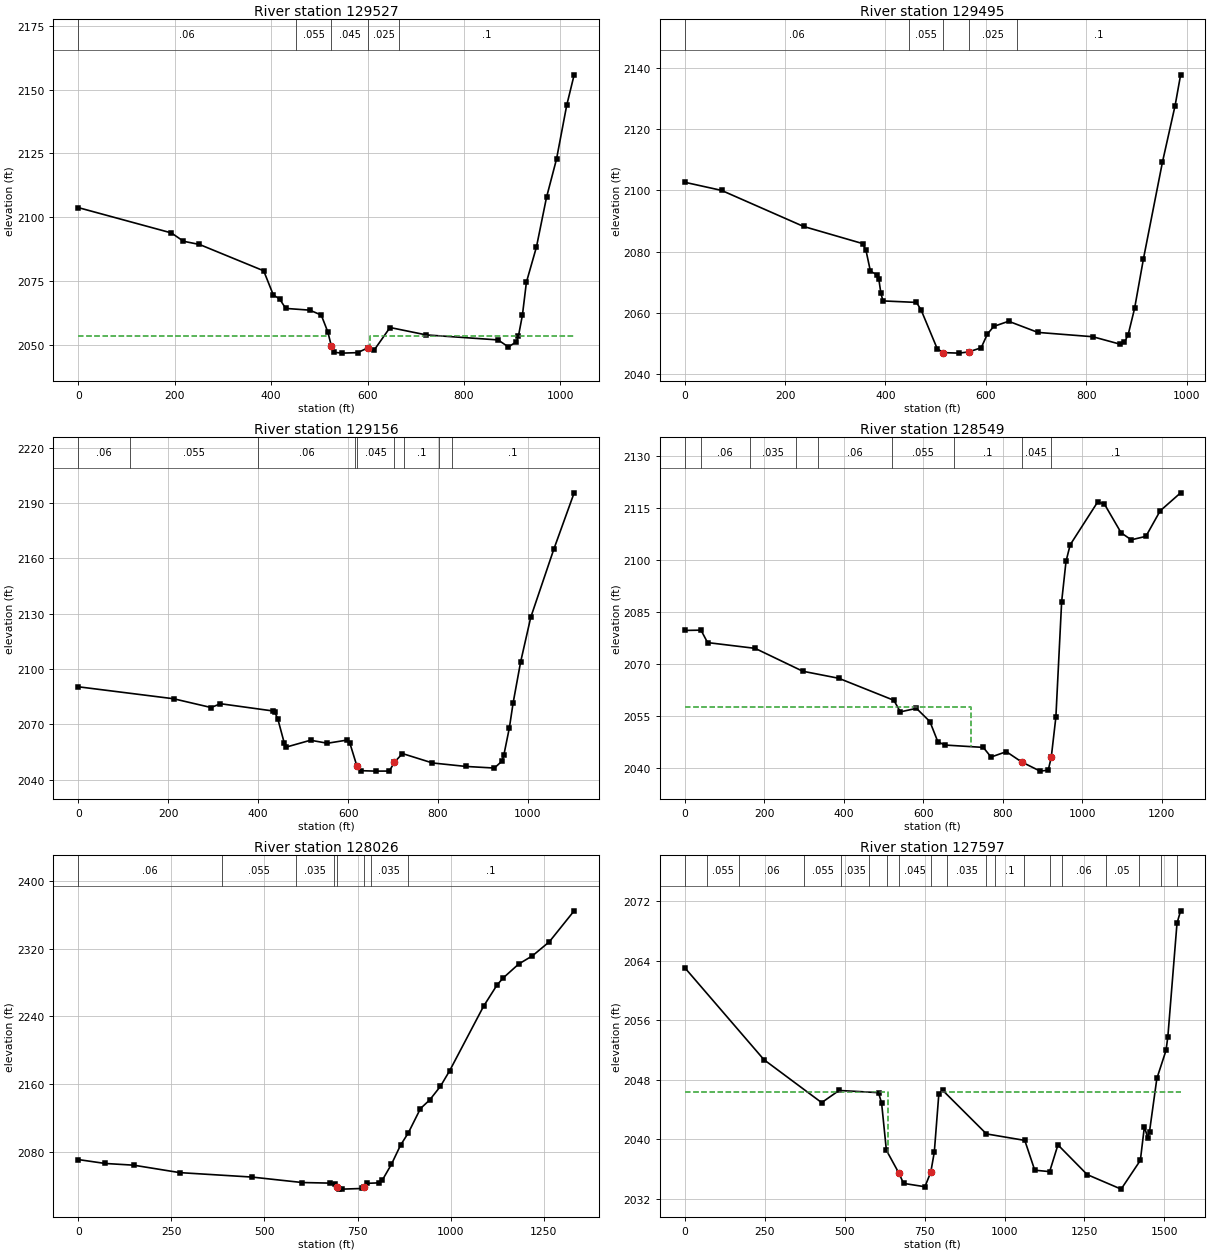
Type RM Length L Ch R = 1 ,129527  ,33.8,32.4,36.3
XS GIS Cut Line= 4
2398300.55052745611932.7072396282398404.08148837611569.794579625
2398574.35772261610971.4138866222398585.20711035610944.679360047
#Sta/Elev= 30
       0 2103.84   193.2 2093.93   218.2 2090.67   251.5 2089.41   384.6 2079.11
   404.6 2069.65   417.5 2068.12   430.3  2064.4   480.2 2063.72     504  2061.8
   517.7 2055.15  524.952049.633   530.1 2047.25     547 2046.91   579.4  2047.1
  600.722048.983   613.3    2048   646.6 2056.93   721.8 2054.03   870.8 2052.07
   891.9 2049.33   908.6 2051.32   912.9 2053.61   921.1 2061.75   929.4 2074.65
   950.2 2088.41   971.1 2107.85   991.8 2122.78    1013 2143.87  1028.4 2155.77
#Mann= 5 ,-1 , 0
       0     .06       0  451.36    .055       0  524.95    .045       0
  600.72    .025       0   666.1      .1       0
#XS Ineff= 2 ,-1
       0  519.95 2053.45  605.72 1028.38 2053.45
Permanent Ineff=
       F       F
Bank Sta=524.95,600.72
XS Rating Curve= 0 ,0
Exp/Cntr=0.5,0.3

Type RM Length L Ch R = 1 ,129495  ,336,338.5,337
XS GIS Cut Line= 3
2398335.43956527611922.4211709652398514.78074202 611300.31480363
2398619.84877336610976.490320042
#Sta/Elev= 30
       0 2102.64    73.4 2099.98   236.8  2088.2   354.5  2082.6     361 2080.49
     370 2073.57   382.5 2072.46   386.7 2071.02   390.8 2066.43     395 2063.87
   461.6 2063.38   470.8 2060.98   503.2  2048.2  515.392046.974   546.2 2046.81
  565.422047.194   590.6 2048.56   603.1 2053.05   615.6 2055.54   645.3 2057.22
   703.6 2053.58   812.9 2052.17   867.6 2049.72     876 2050.32   883.5 2052.89
   896.2 2061.41   913.9 2077.66   951.7 2109.22   976.9 2127.69   987.9 2137.74
#Mann= 5 ,-1 , 0
       0     .06       0  446.66    .055       0  515.39    .045       0
  565.42    .025       0  661.97      .1       0
Bank Sta=515.39,565.42
XS Rating Curve= 0 ,0
Exp/Cntr=0.5,0.3

Type RM Length L Ch R = 1 ,129156  ,582.6,606.9,618.5
XS GIS Cut Line= 2
2398619.34057227612130.2367002072398931.59650943611072.775232464
#Sta/Elev= 30
       0 2090.33     212 2083.84   295.4 2079.08   316.3 2081.14   433.1 2077.21
   437.2 2076.46   443.8 2072.86   458.1 2059.82   462.3 2057.61   516.5 2061.35
     554 2059.71   597.9 2061.43   604.1 2059.65  619.212047.639   629.1 2044.82
   662.3 2044.59   691.7 2044.63  703.112049.441   720.9 2054.11   787.6 2049.02
   861.9 2047.13   925.2 2046.26   941.9 2049.96   946.1 2053.08   958.6  2068.1
   966.9 2081.58   983.6  2103.8    1006  2127.9  1057.2 2164.79  1102.6  2195.5
#Mann= 9 ,-1 , 0
       0     .06       0  114.08    .055       0  399.75     .06       0
  615.48    .035       0  619.21    .045       0  703.11    .035       0
  723.34      .1       0   802.1    .025       0  831.21      .1       0
Bank Sta=619.21,703.11
XS Rating Curve= 0 ,0
Exp/Cntr=0.3,0.1

Type RM Length L Ch R = 1 ,128549  ,498.9,523.6,537.5
XS GIS Cut Line= 3
2398753.09456986612233.0970587882399454.90615836 611563.88907963
2399655.91920778611372.695236295
#Sta/Elev= 30
       0  2079.8      41 2079.89    57.6  2076.3   177.1 2074.64     297 2068.04
   387.5 2066.01   526.1 2059.66   542.3 2056.32   582.8 2057.34   616.7 2053.52
   636.5 2047.76   653.5 2046.77   750.9 2046.08   770.5  2043.3   808.9 2044.85
  847.332041.892   893.9 2039.24   914.2 2039.52  921.842043.184   933.5 2054.82
     948 2088.09     959 2099.73   969.5  2104.5  1038.2 2116.77  1055.2 2116.31
  1097.6 2107.95  1123.1 2105.93  1159.9 2106.93  1195.8 2114.29  1247.2 2119.48
#Mann= 9 ,-1 , 0
       0    .055       0    40.2     .06       0  163.83    .035       0
  281.01    .055       0  334.71     .06       0  521.83    .055       0
  676.46      .1       0  847.33    .045       0  921.84      .1       0
#XS Ineff= 2 , 0
          720.97 2057.81
Permanent Ineff=
       F       F
Bank Sta=847.33,921.84
XS Rating Curve= 0 ,0
Exp/Cntr=0.3,0.1

Type RM Length L Ch R = 1 ,128026  ,395.1,428.5,481.4
XS GIS Cut Line= 2
 2398902.1385631612249.3978792132400195.46274811611933.516621217
#Sta/Elev= 30
       0 2070.71    72.1 2066.11   148.9 2064.07   272.4 2055.28   465.8 2050.04
   601.6 2043.55   675.9 2042.88   688.3 2041.64  695.652038.102   700.8 2036.03
   708.8 2035.76   762.4 2036.53  767.622038.469   774.7  2042.6   807.7 2043.19
   816.7 2046.68   840.6 2064.94   865.3 2087.71   886.2 2102.32   918.8 2131.06
   943.5 2141.16   972.4 2157.35   997.1 2175.73    1088 2251.86  1124.7 2277.39
  1141.2 2285.58  1182.4 2301.89  1219.4 2311.61  1264.7 2328.22  1331.3 2364.79
#Mann= 8 ,-1 , 0
       0     .06       0  386.43    .055       0  585.69    .035       0
  685.31      .1       0  695.65    .045       0  767.62      .1       0
  784.94    .035       0  884.57      .1       0
Bank Sta=695.65,767.62
XS Rating Curve= 0 ,0
Exp/Cntr=0.5,0.3

Type RM Length L Ch R = 1 ,127597  ,150.6,142.9,124.9
XS GIS Cut Line= 5
2399031.38141486612298.5109699672399460.84709135612327.358025134
2399589.52367127612407.3709884582399775.40026802612588.332896873
2400270.62139043613096.007078379
#Sta/Elev= 30
       0 2063.05   247.9 2050.69   428.3 2044.93   482.6 2046.56     606 2046.27
   615.7 2044.87   630.6 2038.54  669.762035.467   684.3 2034.09   751.1 2033.64
  769.542035.609   780.5  2038.3   794.6 2046.07     807 2046.57   943.5 2040.73
  1063.4 2039.86  1094.5 2035.86  1141.1 2035.67    1167 2039.26  1258.5 2035.27
  1364.6 2033.32  1424.7 2037.18  1437.3 2041.69  1447.6 2040.24  1453.4 2041.05
  1476.3 2048.17  1504.9 2051.93  1510.7 2053.78  1539.3 2069.01  1550.6 2070.67
#Mann= 19 ,-1 , 0
       0    .035       0   68.66    .055       0  170.61     .06       0
  374.51    .055       0  489.93    .035       0  575.76    .055       0
  632.24    .035       0  669.76    .045       0  769.54    .055       0
  820.93    .035       0  941.04    .055       0  970.26      .1       0
 1060.78     .06       0 1143.08      .1       0 1180.51     .06       0
  1315.9     .05       0 1419.97    .055       0 1488.72      .1       0
 1539.71     .06       0
#XS Ineff= 2 ,-1
       0     637  2046.4     801 1550.58  2046.4
Permanent Ineff=
       F       F
Bank Sta=669.76,769.54
XS Rating Curve= 0 ,0
Exp/Cntr=0.5,0.3

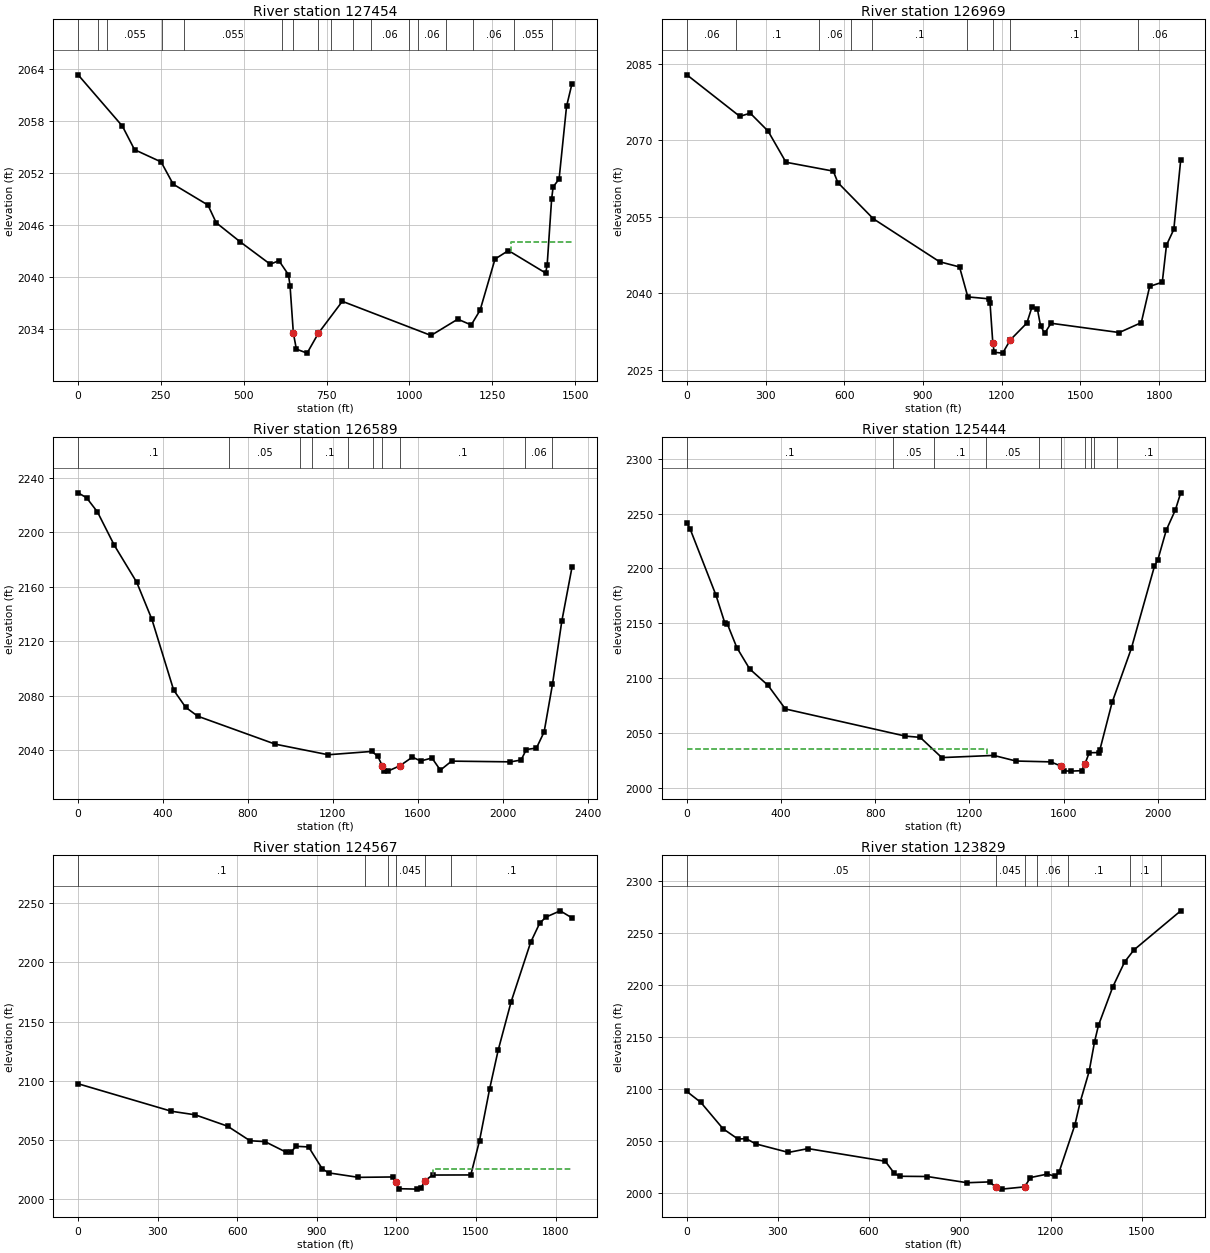
Type RM Length L Ch R = 1 ,127454  ,502.2,485.5,465.1
XS GIS Cut Line= 5
2399032.56809229612359.2952972052399553.91941178612569.123617709
2399753.62832993612699.9612825512399971.38675269612962.603801876
 2400281.3172352613121.701252714
#Sta/Elev= 30
       0 2063.37   133.6 2057.45   170.3 2054.73   250.4 2053.32   286.9 2050.75
   391.8 2048.34   416.7  2046.3   489.6 2044.08   579.8 2041.51     606 2041.92
   634.7  2040.3   639.5 2039.05  649.532033.568   658.6 2031.71     691 2031.25
  725.142033.552   797.3 2037.23    1065 2033.29  1145.7 2035.17  1186.2  2034.5
    1213  2036.2  1258.1 2042.11  1298.6 2043.09    1411 2040.49  1415.5 2041.46
    1429 2049.08  1433.5 2050.44  1451.4 2051.34  1473.9 2059.72  1490.3 2062.35
#Mann= 17 ,-1 , 0
       0    .035       0   61.52     .02       0   88.14    .055       0
  252.24     .06       0   320.2    .055       0   616.7     .06       0
  649.53    .045       0  725.14    .035       0  762.28      .1       0
  828.59    .055       0  884.31     .06       0  997.89      .1       0
 1024.55     .06       0 1111.47      .1       0  1191.4     .06       0
 1314.76    .055       0 1429.25     .06       0
#XS Ineff= 2 , 0
                         1306.95         2044.07
Permanent Ineff=
       F       F
Bank Sta=649.53,725.14
XS Rating Curve= 0 ,0
Exp/Cntr=0.5,0.3

Type RM Length L Ch R = 1 ,126969  ,404.3,380.2,345.3
XS GIS Cut Line= 3
2398421.85966802613036.4291135372399795.34117302613131.573936373
2400301.05276003613133.159563124
#Sta/Elev= 30
       0 2082.88   201.9 2074.73   241.5 2075.36   309.6 2071.84   377.8 2065.73
   558.2 2063.99   575.6 2061.74   710.6 2054.65   963.1 2046.22  1039.4 2045.19
    1071 2039.32  1151.6 2038.94  1155.6 2038.13 1166.172030.323  1171.7 2028.45
  1203.8 2028.29 1233.112030.891    1296 2034.19    1316 2037.42  1336.1 2036.96
  1348.1 2033.66  1364.1 2032.19  1388.2 2034.15  1648.2 2032.33  1732.2 2034.27
  1764.2 2041.38  1812.2  2042.2  1828.2 2049.47  1856.2 2052.57  1882.5 2066.21
#Mann= 9 ,-1 , 0
       0     .06       0  186.61      .1       0  501.91     .06       0
  626.95      .1       0  705.92      .1       0 1067.29     .06       0
 1166.17    .045       0 1233.11      .1       0 1721.36     .06       0
Bank Sta=1166.17,1233.11
XS Rating Curve= 0 ,0
Exp/Cntr=0.3,0.1

Type RM Length L Ch R = 1 ,126589  ,1139.1,1145.2,1150.3
XS GIS Cut Line= 3
2398519.45921037614407.8226962092399780.62991637 613396.96480979
2400426.06825802613100.112385124
#Sta/Elev= 30
       0    2229    39.9 2225.38    91.2 2214.95   170.9 2190.39   276.2 2163.33
   347.7  2136.1   450.2 2084.17   506.6 2071.57   563.6 2065.03   928.9 2044.49
  1178.2 2036.72  1383.2 2039.16  1411.5 2035.74 1432.712028.679    1440 2024.95
  1459.7  2024.7 1516.522028.681  1574.8 2034.98  1613.9 2032.13    1667 2034.34
  1706.7 2025.43  1759.5 2032.04  2036.9 2031.51  2086.9 2032.84  2111.7 2040.57
  2159.3 2041.62  2195.5 2053.49  2234.7  2088.3    2279 2134.95  2326.7 2174.26
#Mann= 10 ,-1 , 0
       0      .1       0  709.54     .05       0 1045.37      .1       0
 1101.09      .1       0  1273.6     .05       0 1387.72     .06       0
 1432.71    .045       0 1516.52      .1       0 2104.52     .06       0
 2234.34      .1       0
Bank Sta=1432.71,1516.52
XS Rating Curve= 0 ,0
Exp/Cntr=0.3,0.1

Type RM Length L Ch R = 1 ,125444  ,872.5,876.1,879.8
XS GIS Cut Line= 2
2399295.95043951615024.5655572122400993.01397452 613791.58902055
#Sta/Elev= 30
       0 2241.37    13.3 2236.34   123.5 2175.73   160.7 2150.68   172.2 2149.28
   212.2 2127.86   266.7 2108.38   344.6 2093.46   418.4 2071.88   928.4 2047.12
   991.2 2045.98  1082.8 2027.52  1303.3 2029.52  1397.9  2024.4  1546.1 2023.63
 1590.242019.626  1601.1 2015.45  1630.1 2015.19  1676.9  2015.6 1690.132021.426
  1709.2 2031.97  1748.8 2032.12  1753.7 2034.12  1806.2 2077.82  1887.9 2127.06
  1986.1 2202.02  2000.9 2208.17  2036.4 2235.01  2075.1 2253.46  2097.7 2268.99
#Mann= 10 ,-1 , 0
       0      .1       0  874.85     .05       0 1049.98      .1       0
  1272.5     .05       0 1495.02     .06       0 1590.24    .045       0
 1690.13      .1       0 1717.54    .055       0 1729.32     .06       0
  1828.8      .1       0
#XS Ineff= 2 , 0
         1274.34  2035.8
Permanent Ineff=
       F       F
Bank Sta=1590.24,1690.13
XS Rating Curve= 0 ,0
Exp/Cntr=0.3,0.1

Type RM Length L Ch R = 1 ,124567  ,727.4,738.8,744
XS GIS Cut Line= 2
2400007.61568287615463.1729477052401591.20273876  614483.5709043
#Sta/Elev= 30
       0 2097.46   351.7 2074.26   441.3 2071.26   563.7 2061.65   648.1 2049.36
   704.5 2048.64   784.5 2039.69   803.3  2039.9   821.7 2044.69   869.1 2044.14
   920.7 2025.63   944.4 2022.26    1057 2018.47    1189  2018.8 1198.772014.235
  1208.4 2008.89  1278.3 2008.53  1292.7 2009.33 1306.662015.385  1336.3 2020.42
  1480.6  2020.5  1513.5 2049.38  1551.6 2093.11    1584 2125.93  1632.7 2166.67
  1706.3 2216.84  1740.2 2232.89  1763.4 2238.09  1817.8 2243.43  1862.1 2237.47
#Mann= 6 ,-1 , 0
       0      .1       0 1082.87     .05       0 1167.58     .06       0
 1198.77    .045       0 1306.66     .06       0 1405.44      .1       0
#XS Ineff= 1 ,-1
 1339.74 1862.08 2025.44
Permanent Ineff=
       F
Bank Sta=1198.77,1306.66
XS Rating Curve= 0 ,0
Exp/Cntr=0.3,0.1

Type RM Length L Ch R = 1 ,123829  ,659.7,701.5,720.4
XS GIS Cut Line= 2
2400444.23423219615840.0366953022401954.14787903615229.039229631
#Sta/Elev= 30
       0 2097.52      46 2087.05   119.2 2061.68   168.7  2051.7     195 2052.18
     227  2047.1     335 2038.85   399.7 2042.52   654.3 2030.35   684.5 2018.62
   701.8 2015.88   792.4 2015.66   924.4 2009.66   999.5 2010.47 1018.032005.414
  1038.1  2003.5 1113.852005.675  1133.3 2014.63  1189.4 2018.03  1215.2 2015.82
  1228.2 2020.37    1280 2065.52  1297.2 2087.26  1326.8 2116.86  1344.7 2145.42
  1357.6 2161.23  1405.1 2198.44  1443.9 2222.29  1474.6 2233.86  1628.9 2271.51
#Mann= 7 ,-1 , 0
       0     .05       0 1018.03    .045       0 1113.85      .1       0
 1154.94     .06       0 1256.79      .1       0 1460.51      .1       0
 1562.36      .1       0
Bank Sta=1018.03,1113.85
XS Rating Curve= 0 ,0
Exp/Cntr=0.3,0.1

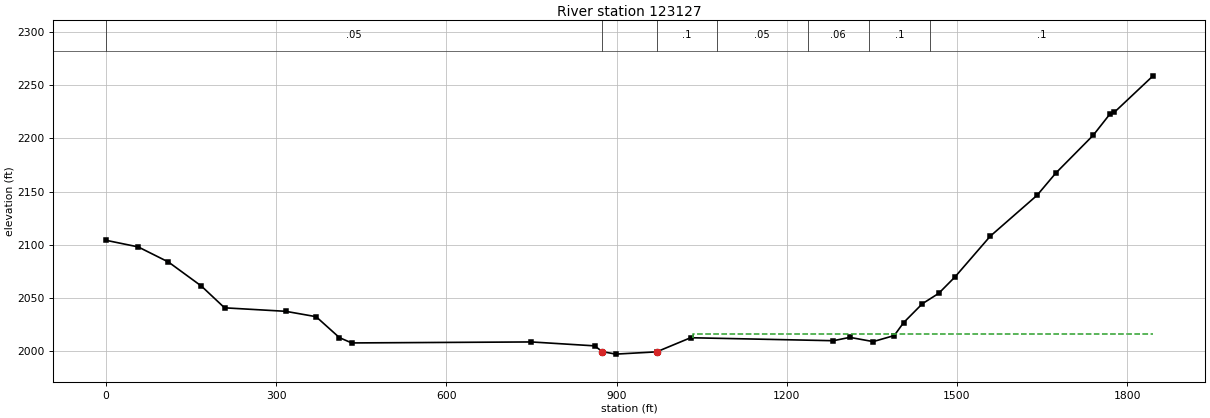
Type RM Length L Ch R = 1 ,123127  ,576.9,579,582.8
XS GIS Cut Line= 2
2400443.39171419615892.107129216 2402233.0062452616342.946450621
#Sta/Elev= 30
       0 2104.26    57.1    2098   110.5 2083.77   168.5 2061.18   209.3 2040.74
     317 2037.46   370.6 2032.41   411.8 2012.69   433.4 2007.73   750.1 2008.66
   861.5 2004.98  874.831999.592   898.6 1997.21   970.71999.353  1030.6 2012.62
  1282.2 2009.82  1311.1 2012.97  1352.3 2008.99  1389.4 2014.66  1405.9  2026.8
  1438.9 2044.55  1467.8 2054.34  1496.7  2069.9  1558.6 2108.06  1641.1 2146.51
  1674.1 2167.39  1740.1 2202.98  1768.9  2222.5  1777.2 2224.51  1845.5 2258.82
#Mann= 7 ,-1 , 0
       0     .05       0  874.83    .045       0   970.7      .1       0
 1076.59     .05       0 1236.59     .06       0 1344.76      .1       0
 1452.94      .1       0
#XS Ineff= 2 , 0
                         1034.48         2016.39
Permanent Ineff=
       F       F
Bank Sta=874.83,970.7
XS Rating Curve= 0 ,0
Exp/Cntr=0.3,0.1