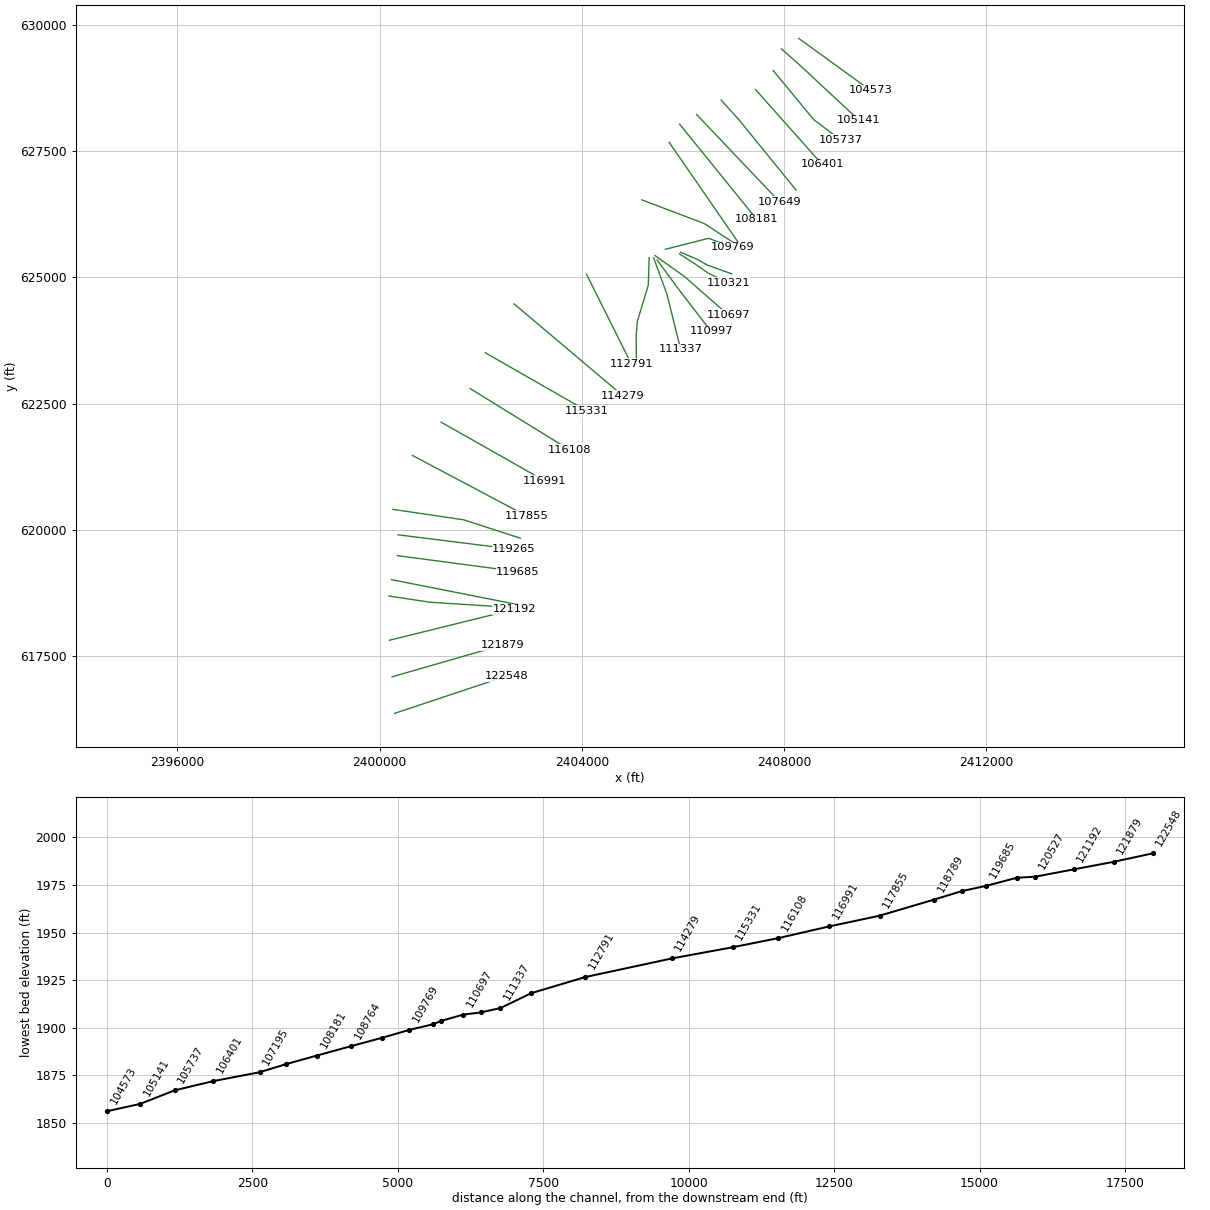
HEC-RAS study NFSBPOTOMC.prj: NFSBPOTOMC

--- NFSBPOTOMC.g01 (geometry) --- (continued)

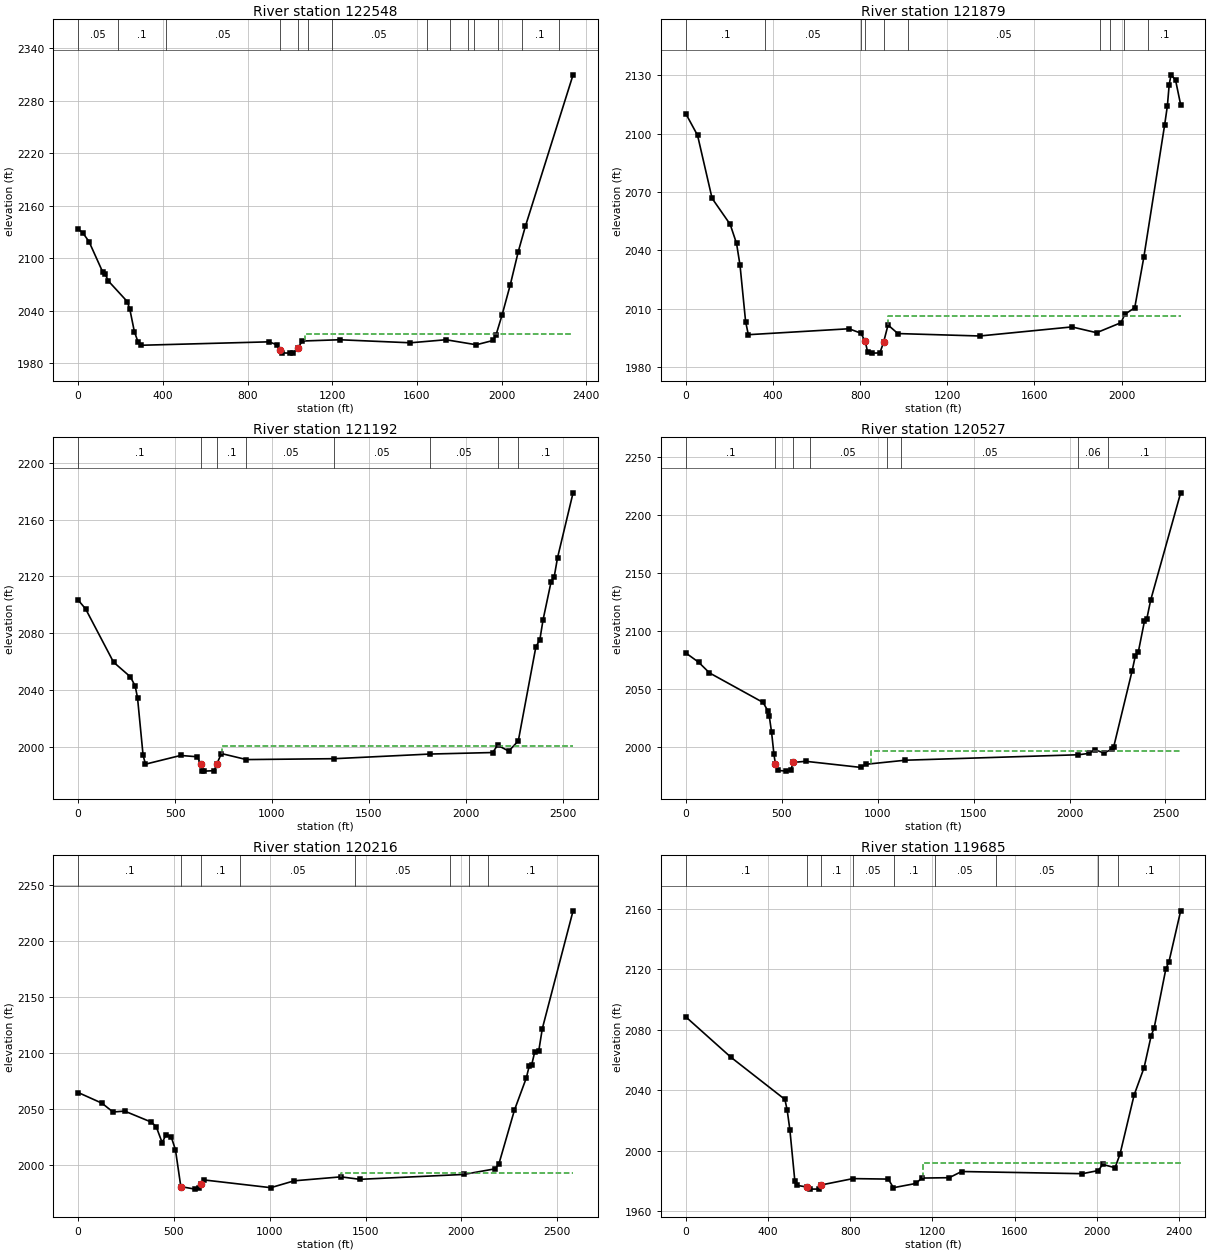
Type RM Length L Ch R = 1 ,122548  ,670,669.5,666.2
XS GIS Cut Line= 2
2400294.96484569616374.0897610492402512.21795711617113.104031041
#Sta/Elev= 30
       0 2133.08    20.8 2129.32    51.1 2119.04   116.4 2083.93     127 2081.99
   143.1 2073.84   231.7 2050.48     244 2041.68   265.4  2016.1   282.3 2004.62
   294.6 2000.49   902.1 2004.43     940 2000.86  950.851995.271   961.1 1991.79
  1001.9 1991.52  1015.9 1991.69 1038.74 1997.67  1058.1 2005.35  1235.2  2006.8
    1569 2003.33  1736.9 2006.81  1880.3 2001.08  1960.4 2006.06    1973 2012.08
  2001.3 2034.58  2040.5 2069.48  2078.4  2107.5  2112.1 2136.51  2337.2 2309.54
#Mann= 14 ,-1 , 0
       0     .05       0   188.7      .1       0  412.93     .05       0
  950.85    .045       0 1038.74     .05       0 1085.63      .1       0
 1197.74     .05       0 1646.21     .06       0 1758.32      .1       0
 1843.35     .06       0 1870.44      .1       0 1982.55      .1       0
 2094.67      .1       0 2269.13     .12       0
#XS Ineff= 1 ,-1
 1069.81 2337.17 2013.82
Permanent Ineff=
       F
Bank Sta=950.85,1038.74
XS Rating Curve= 0 ,0
Exp/Cntr=0.3,0.1

Type RM Length L Ch R = 1 ,121879  ,687.4,686.4,684.3
XS GIS Cut Line= 2
 2400246.8035247617097.2831965392402429.37822777617726.359694287
#Sta/Elev= 30
       0 2110.37    54.1 2099.19   120.8 2066.76   203.9 2053.35   233.1 2043.54
   249.1 2032.27   274.7 2003.29   287.2 1996.58   749.2 1999.63   803.4 1997.37
  823.791993.109     835 1987.48   854.4 1987.09   890.8  1987.2  907.771992.608
   928.3 2001.58   973.5 1997.16    1349 1995.91  1772.1 2000.58  1885.7  1997.6
  1998.1 2002.79  2014.8 2007.07  2060.5 2010.41  2102.2 2036.37  2197.9 2104.61
  2210.4 2114.32  2218.7 2125.26  2227.1 2130.32  2247.9  2127.6  2271.4 2114.88
#Mann= 10 ,-1 , 0
       0      .1       0  365.48     .05       0  804.86      .1       0
  823.79    .045       0  907.77      .1       0 1020.54     .05       0
  1903.3     .06       0 1946.71     .05       0 2013.14     .06       0
 2122.99      .1       0
#XS Ineff= 2 , 0
                           929.2         2006.33
Permanent Ineff=
       F       F
Bank Sta=823.79,907.77
XS Rating Curve= 0 ,0
Exp/Cntr=0.3,0.1

Type RM Length L Ch R = 1 ,121192  ,684.9,665.3,649.2
XS GIS Cut Line= 2
2400193.43486503617820.3926427072402673.15234652618433.443581969
#Sta/Elev= 30
       0 2103.41    38.4 2097.21   182.6 2059.76   269.2 2049.48     294 2043.07
   306.3 2034.85   335.1  1994.3   347.5 1988.04   528.8 1994.15   615.3 1993.24
   631.61988.129     640 1983.38   650.7 1983.14   701.8 1983.45  715.541988.044
   738.9 1995.51   868.7 1991.26    1323 1991.89  1814.3 1995.14  2139.9 1996.22
  2164.6  2001.4  2222.3 1997.21  2271.7  2004.4  2362.4 2070.49    2383 2075.58
  2399.4 2089.47  2440.6 2116.04  2457.1 2119.87  2474.3 2133.25  2554.4 2178.82
#Mann= 8 ,-1 , 0
       0      .1       0   631.6    .045       0  715.54      .1       0
   868.7     .05       0    1323     .05       0  1814.3     .05       0
  2164.6     .06       0  2271.7      .1       0
#XS Ineff= 1 ,-1
     740 2554.38 2000.63
Permanent Ineff=
       F
Bank Sta=631.6,715.54
XS Rating Curve= 0 ,0
Exp/Cntr=0.3,0.1

Type RM Length L Ch R = 1 ,120527  ,312.4,310.4,311
XS GIS Cut Line= 3
2400184.48639211618695.2672052982400993.77512786618572.942646801
2402750.83723053618460.742739961
#Sta/Elev= 30
       0 2081.28      67 2073.29   123.6 2064.05   402.8 2038.57   427.1 2031.57
   435.1 2026.81   447.3 2012.68   459.4 1994.08  467.131985.379   479.6  1979.9
   524.1 1979.28   548.4  1980.2  558.961986.766   625.3 1987.76   911.6  1982.5
   939.7  1985.2  1144.1  1988.7  2046.1 1993.41  2102.1 1994.59  2130.1 1997.87
  2178.2    1995  2222.3 1998.17  2230.4 2000.43  2326.5 2066.11  2342.5  2078.5
  2358.6 2082.32  2390.6 2108.93  2402.7 2110.76  2422.7 2126.81  2579.1 2219.47
#Mann= 8 ,-1 , 0
       0      .1       0  467.13    .045       0  558.96      .1       0
  647.78     .05       0 1046.13     .05       0 1121.89     .05       0
 2043.99     .06       0 2202.17      .1       0
#XS Ineff= 2 , 0
                          963.26         1996.36
Permanent Ineff=
       F       F
Bank Sta=467.13,558.96
XS Rating Curve= 0 ,0
Exp/Cntr=0.3,0.1

Type RM Length L Ch R = 1 ,120216  ,531.2,531.5,532.7
XS GIS Cut Line= 2
2400236.54074994619019.033290043 2402770.7390936618518.357454121
#Sta/Elev= 30
       0 2064.82   124.6 2055.28   181.6 2047.47   242.8 2048.26   381.4  2038.5
   407.2 2034.47   438.5 2020.15   458.9 2027.32   485.5 2025.43   507.8 2013.81
  535.831980.996   609.8 1978.75   630.2 1979.45   639.81983.394   654.6 1986.98
  1005.3 1980.04  1127.6 1986.16  1372.2 1989.69  1470.1 1987.48  2012.4 1991.84
  2175.5 1996.83  2195.8 2001.06  2277.4 2049.25  2338.6 2077.55  2354.6 2088.51
  2367.1 2089.41  2383.4 2101.27  2403.8  2101.6  2422.7 2121.77  2583.2  2226.7
#Mann= 8 ,-1 , 0
       0      .1       0  535.83    .045       0   639.8      .1       0
  847.32     .05       0 1443.58     .05       0 1940.46     .05       0
 2039.83     .06       0 2139.21      .1       0
#XS Ineff= 1 ,-1
 1370.27 2583.19 1992.96
Permanent Ineff=
       F
Bank Sta=535.83,639.8
XS Rating Curve= 0 ,0
Exp/Cntr=0.3,0.1

Type RM Length L Ch R = 1 ,119685  ,419.6,419.6,418.2
XS GIS Cut Line= 2
2400348.63599819 619494.81613113 2402735.1548472619178.475228384
#Sta/Elev= 30
       0  2088.5     220 2061.72   482.3 2033.85   493.5 2026.62   506.5 2013.66
   530.7 1979.74   542.8 1976.95  587.851975.923   603.3 1974.49   646.7 1974.54
  659.831977.268   813.2 1981.45   985.1 1981.13  1010.1 1975.43  1119.8 1978.26
  1148.1 1981.81  1281.7 1982.06  1341.7 1986.14  1929.3 1984.71  2007.4  1986.8
  2027.7 1990.86  2088.2 1988.65  2112.4 1997.71    2181 2036.76  2229.4 2054.87
  2264.1 2076.07  2278.4 2081.16  2335.4 2120.24  2350.5 2124.99  2407.4 2158.64
#Mann= 9 ,-1 , 0
       0      .1       0  587.85    .045       0  659.83      .1       0
  812.67     .05       0 1011.38      .1       0  1210.1     .05       0
 1508.18     .05       0 2004.98     .06       0 2104.34      .1       0
#XS Ineff= 2 , 0
                         1154.61         1991.77
Permanent Ineff=
       F       F
Bank Sta=587.85,659.83
XS Rating Curve= 0 ,0
Exp/Cntr=0.3,0.1

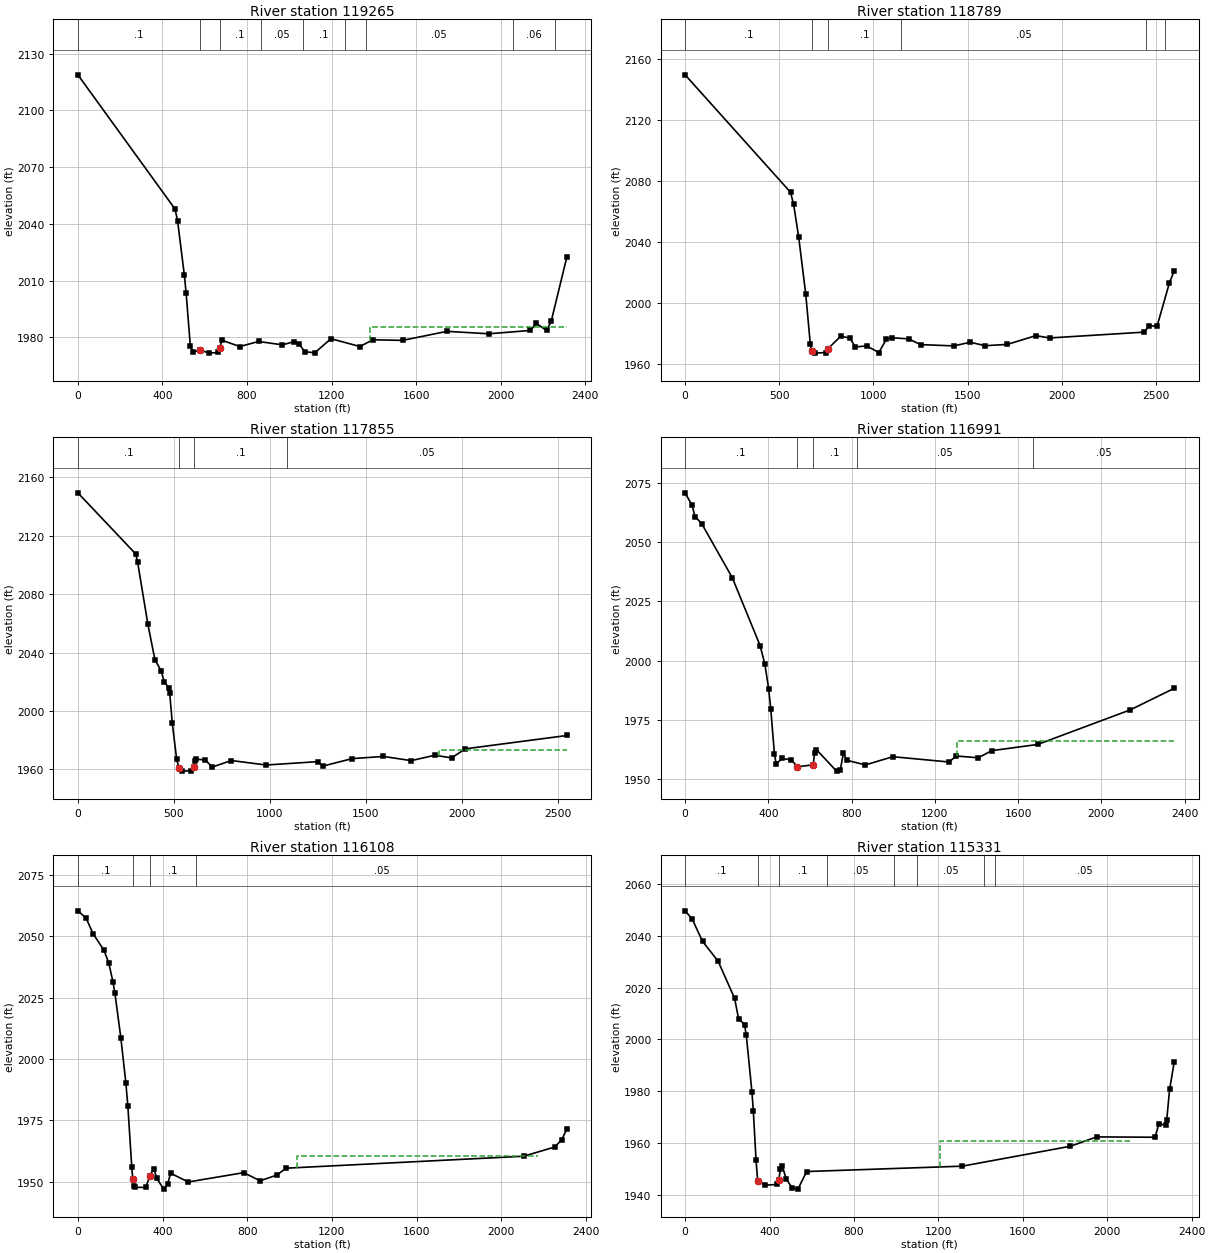
Type RM Length L Ch R = 1 ,119265  ,477.7,476.5,476.4
XS GIS Cut Line= 2
2400362.80821395619906.5134704562402658.56641769619619.954660371
#Sta/Elev= 30
       0 2118.82   459.5 2047.89   471.6 2041.71   503.8 2012.83   511.9 2003.69
     532 1975.45   544.1 1972.36  579.391973.345   619.6  1971.7   665.1 1972.04
   671.31974.468   681.2 1978.55   765.8 1975.17   854.5 1977.86   967.4 1976.08
    1021 1977.69    1048 1976.44  1072.2 1972.49  1120.6 1971.86  1197.2 1979.33
  1334.2 1975.18  1394.7 1978.76  1535.8 1978.44    1746 1983.21  1942.9 1981.93
  2140.4 1983.68  2168.6 1987.41    2217 1983.69  2238.9 1988.49  2313.6 2022.76
#Mann= 9 ,-1 , 0
       0      .1       0  579.39    .045       0   671.3      .1       0
  864.81     .05       0 1063.58      .1       0 1262.34     .05       0
 1361.73     .05       0 2057.41     .06       0 2256.18      .1       0
#XS Ineff= 1 ,-1
 1383.55 2313.57 1985.73
Permanent Ineff=
       F
Bank Sta=579.39,671.3
XS Rating Curve= 0 ,0
Exp/Cntr=0.3,0.1

Type RM Length L Ch R = 1 ,118789  ,946.8,933.7,920.5
XS GIS Cut Line= 3
 2400260.9074991620410.0849698782401660.11631486620203.552902624
2402785.23381528619839.022791788
#Sta/Elev= 30
       0 2149.48   559.8 2072.59     576 2064.87   603.4 2043.02   640.7 2005.77
     665 1973.02  671.231968.872   689.2 1967.26   749.9 1967.67  759.121970.206
   826.7 1978.35   875.2  1977.1   903.5 1971.32   964.2 1971.97  1028.9 1967.67
  1069.3  1976.5  1097.6 1977.34  1186.6 1976.59  1251.2 1972.84  1426.5 1971.99
  1513.8 1974.38  1593.7 1972.12  1711.5 1972.98  1862.8 1978.72  1935.6 1977.19
  2438.9 1981.02  2464.1 1985.32  2506.2 1984.86  2571.5 2013.18  2597.1 2021.11
#Mann= 6 ,-1 , 0
       0      .1       0  671.23    .045       0  759.12      .1       0
 1144.85     .05       0 2448.01     .06       0 2548.49      .1       0
Bank Sta=671.23,759.12
XS Rating Curve= 0 ,0
Exp/Cntr=0.3,0.1

Type RM Length L Ch R = 1 ,117855  ,866,864.6,863.7
XS GIS Cut Line= 2
2400648.16492668621477.1412347112402899.57184118620283.591456458
#Sta/Elev= 30
       0 2149.48   301.7 2107.55   310.8 2102.34   364.5 2059.69   401.3 2035.18
     433 2027.72   450.3    2020   474.5 2015.72   478.3 2012.47   491.9 1991.71
   514.5 1967.13  527.221960.696   542.8 1958.84   591.5 1959.08   603.11961.779
   610.1 1966.03     616 1967.04   663.9 1966.48   700.1 1961.61   799.7 1966.11
   980.8 1963.02  1252.5 1965.36  1275.1 1962.25    1429 1967.41    1592  1968.9
  1736.9 1966.02  1859.1 1969.72  1947.1  1967.9  2018.5 1974.11  2548.2 1983.25
#Mann= 4 ,-1 , 0
       0      .1       0  527.22    .045       0   603.1      .1       0
 1090.26     .05       0
#XS Ineff= 2 , 0
                         1880.72         1973.37
Permanent Ineff=
       F       F
Bank Sta=527.22,603.1
XS Rating Curve= 0 ,0
Exp/Cntr=0.3,0.1

Type RM Length L Ch R = 1 ,116991  ,880,883.1,874.7
XS GIS Cut Line= 2
2401217.41411626622133.938149467 2403261.6557627620975.229508877
#Sta/Elev= 30
       0 2070.94    33.7 2065.61    47.5 2060.92    79.7 2057.92   226.8 2035.04
   360.2 2006.35   383.2 1998.51   401.5 1988.07   411.8 1979.34   429.1 1960.58
   437.5 1956.38   466.9 1958.57   510.9 1957.95  539.491955.055  615.42 1955.88
   622.2 1960.82   631.2 1962.29   727.8 1953.22   745.6 1953.68   760.6 1960.88
   776.8 1957.82   865.9 1955.84     998 1959.32    1268 1957.08  1302.7 1959.62
  1408.5 1958.87  1473.4 1961.88  1693.7  1964.5  2139.6 1979.16  2349.8 1988.25
#Mann= 5 ,-1 , 0
       0      .1       0  539.49    .045       0  615.42      .1       0
  825.91     .05       0 1673.25     .05       0
#XS Ineff= 1 ,-1
 1304.41 2349.79 1966.03
Permanent Ineff=
       F
Bank Sta=539.49,615.42
XS Rating Curve= 0 ,0
Exp/Cntr=0.3,0.1

Type RM Length L Ch R = 1 ,116108  ,775.4,776.2,777.7
XS GIS Cut Line= 2
2401789.99466401622799.4699548782403756.15756188621586.645793749
#Sta/Elev= 30
       0 2060.39    38.8 2057.45    71.4 2051.13   123.1 2044.34   145.9 2039.17
   165.4 2031.55   174.8 2026.91     203 2008.64   226.5 1990.45   235.9 1981.04
   254.7 1955.93  259.271951.249   264.1 1948.38   268.4 1947.79   320.7  1947.7
  339.781952.394   358.5 1955.43   372.2 1951.47   405.3 1947.03   423.9 1949.06
     438  1953.5   521.3 1949.94   782.9 1953.73   860.9 1950.43   938.2  1952.7
     984 1955.56  2105.5 1960.43  2252.1 1964.18  2285.7 1967.22  2310.1  1971.6
#Mann= 4 ,-1 , 0
       0      .1       0  259.27    .045       0  339.78      .1       0
  556.53     .05       0
#XS Ineff= 1 ,-1
 1034.48 2174.62 1960.58
Permanent Ineff=
       F
Bank Sta=259.27,339.78
XS Rating Curve= 0 ,0
Exp/Cntr=0.3,0.1

Type RM Length L Ch R = 1 ,115331  ,1059.8,1052.1,1038.3
XS GIS Cut Line= 2
2402091.04786769623507.4852711262404101.59763099 622355.88434623
#Sta/Elev= 30
       0 2049.57    33.4 2046.44    82.6 2037.81   156.4 2030.16   234.6 2015.84
   253.2    2008   281.6 2005.71   290.1 2001.52   316.8  1979.6   323.1 1972.53
   336.2 1953.35   343.8 1945.58   377.6  1943.8   437.6 1944.12  443.741945.708
   451.4  1950.1   460.4 1951.23   479.1 1946.17   506.7 1942.87   534.4  1942.3
   575.9 1949.08    1313 1951.15  1825.1 1958.82  1949.3 1962.43  2226.1  1962.3
  2244.6 1967.48  2276.8 1966.93  2281.4 1968.79  2295.3 1980.73    2317 1991.24
#Mann= 8 ,-1 , 0
       0      .1       0   343.8    .045       0  443.74      .1       0
  672.45     .05       0  991.24     .05       0  1097.5     .05       0
 1416.28     .05       0 1467.09     .05       0
#XS Ineff= 1 ,-1
 1209.72 2106.78  1960.8
Permanent Ineff=
       F
Bank Sta=343.8,443.74
XS Rating Curve= 0 ,0
Exp/Cntr=0.3,0.1

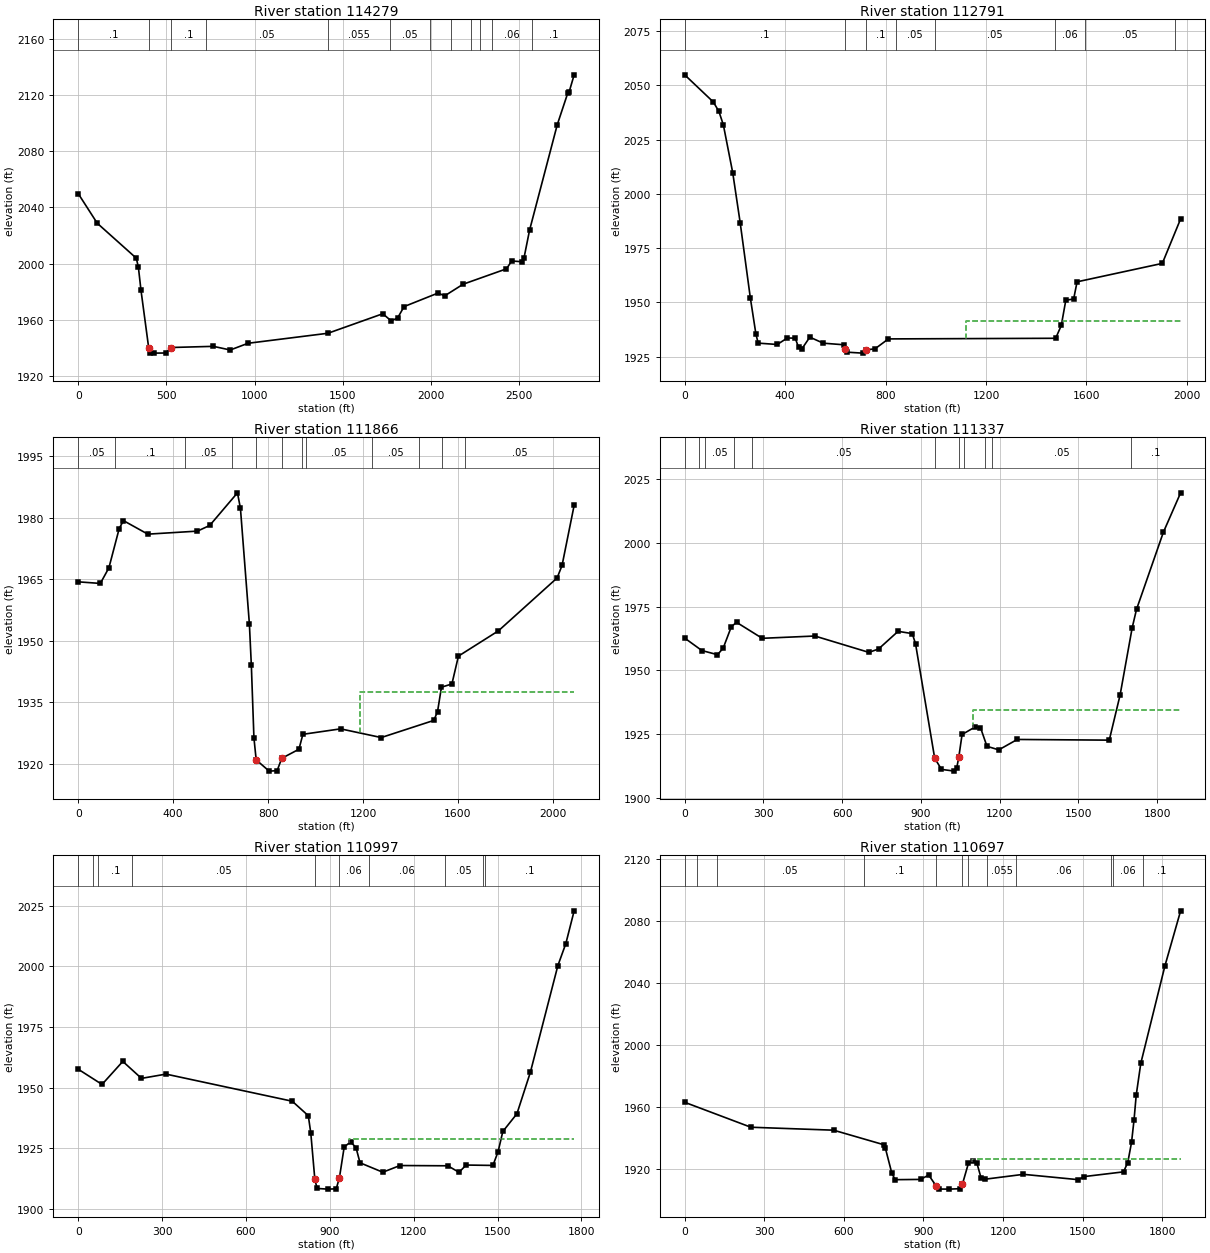
Type RM Length L Ch R = 1 ,114279  ,1506,1488.5,1436.7
XS GIS Cut Line= 2
2402658.74423885624475.0302520392404807.94400868622660.788145632
#Sta/Elev= 30
       0  2049.8     108 2028.73   329.4 2003.89   341.3 1997.43     356 1981.06
  399.511940.307     406 1936.71   428.7 1936.39   496.3 1936.49  527.361940.389
   766.5 1941.21   862.2 1938.62   963.2  1943.4  1416.5 1950.52  1727.4 1964.39
  1774.5 1959.36  1811.2 1961.35  1848.1 1969.47  2041.5 1979.14  2077.9 1977.07
  2182.9 1985.38  2428.9 1996.33  2458.2 2001.92  2517.9 2001.34  2528.3 2004.14
  2559.7 2023.79  2716.8 2098.76  2776.2 2121.22  2784.8 2122.38  2812.6 2134.24
#Mann= 12 ,-1 , 0
       0      .1       0  399.51    .045       0  527.36      .1       0
   723.3     .05       0  1418.2    .055       0 1765.65     .05       0
 1997.29     .06       0  2113.1     .05       0 2228.92     .06       0
 2276.28     .05       0 2344.74     .06       0 2576.37      .1       0
Bank Sta=399.51,527.36
XS Rating Curve= 0 ,0
Exp/Cntr=0.3,0.1

Type RM Length L Ch R = 1 ,112791  ,958.7,924.7,883.3
XS GIS Cut Line= 2
2404092.01958752625060.7334769672404974.79406869623293.712732792
#Sta/Elev= 30
       0 2054.82   113.8 2042.34   136.2    2038   154.1 2031.73   191.3 2009.77
   221.2 1986.57   261.4 1952.15   283.8 1935.32   292.7 1931.22   368.7 1930.59
   408.9 1933.59   440.3  1933.5   453.7 1929.27   467.1 1928.62   498.4 1933.97
     552 1931.19   632.6 1930.47  639.761928.557   645.9 1927.05   708.5 1926.61
  723.731928.166   757.8 1928.57   811.4 1933.16  1477.6 1933.45    1500 1939.35
  1518.1 1951.03  1549.2 1951.51  1562.9 1959.46  1902.4 1967.95  1975.3 1988.45
#Mann= 8 ,-1 , 0
       0      .1       0  639.76    .045       0  723.73      .1       0
   840.3     .05       0  996.23     .05       0 1474.72     .06       0
 1594.34     .05       0 1953.21      .1       0
#XS Ineff= 1 ,-1
 1120.41 1975.27 1941.28
Permanent Ineff=
       F
Bank Sta=639.76,723.73
XS Rating Curve= 0 ,0
Exp/Cntr=0.3,0.1

Type RM Length L Ch R = 1 ,111866  ,507.1,528.6,555.3
XS GIS Cut Line= 5
2405331.55286962625388.0848563762405314.27698553624846.123013794
2405096.78693494624123.8341040462405075.04714903623857.850055963
2405078.34701118623331.846842885
#Sta/Elev= 30
       0 1964.36    93.2 1963.97   129.3 1967.78   172.6 1977.34   190.6 1979.29
   293.3 1975.99   502.3 1976.73     554 1978.11   670.9 1986.07   683.5 1982.27
   721.1 1954.15   729.4    1944   740.3 1926.31  749.781920.937   804.5 1918.19
     838  1918.3  857.541921.315   929.9 1923.53   946.6 1927.17  1105.4  1928.5
  1276.7 1926.38  1498.2 1930.56  1513.9 1932.72  1530.3 1938.66  1574.4 1939.45
  1601.8 1946.24  1770.4 1952.41  2017.6 1965.31  2038.4 1968.36  2089.4 1983.03
#Mann= 12 ,-1 , 0
       0     .05       0  156.86      .1       0  451.66     .05       0
  648.41      .1       0  749.78    .045       0  857.54      .1       0
  943.83    .055       0  958.01     .05       0 1239.25     .05       0
 1435.23     .06       0 1533.02    .035       0  1631.5     .05       0
#XS Ineff= 2 , 0
                         1185.84         1937.49
Permanent Ineff=
       F       F
Bank Sta=749.78,857.54
XS Rating Curve= 0 ,0
Exp/Cntr=0.3,0.1

Type RM Length L Ch R = 1 ,111337  ,323.4,340.9,361.1
XS GIS Cut Line= 3
2405420.15833545625384.3096014562405681.72342911624669.769035801
2405954.64348695623575.194125205
#Sta/Elev= 30
       0 1962.61    65.5 1957.72     125 1956.09   146.6 1958.65   177.7 1967.07
   197.5  1968.8   295.4 1962.52   495.8 1963.42   701.6    1957   738.4 1958.33
   812.9 1965.26   866.9 1964.36   879.3 1960.38  952.251915.463   978.2 1911.07
  1027.7 1910.39    1036 1911.53 1043.931915.796  1056.6 1924.77  1107.3 1927.79
  1126.7 1927.47  1151.4 1920.13  1196.4 1918.74  1266.8 1922.82  1617.2 1922.55
  1658.5 1940.28  1704.5 1966.66    1721 1973.87  1823.3 2004.15    1889 2019.62
#Mann= 11 ,-1 , 0
       0     .05       0   53.78      .1       0   77.74     .05       0
  189.19      .1       0  256.62     .05       0  952.25    .045       0
 1043.93      .1       0 1064.64     .06       0 1142.42    .055       0
 1170.46     .05       0 1699.59      .1       0
#XS Ineff= 2 , 0
                         1097.35         1934.29
Permanent Ineff=
       F       F
Bank Sta=952.25,1043.93
XS Rating Curve= 0 ,0
Exp/Cntr=0.3,0.1

Type RM Length L Ch R = 1 ,110997  ,290.7,299.6,309.2
XS GIS Cut Line= 3
2405488.52466851625343.7476747192405935.86170036624736.381763458
2406558.31747645623928.717696384
#Sta/Elev= 30
       0 1957.58    85.2  1951.3   159.5  1960.8   226.3  1953.8   314.1 1955.56
   765.6 1944.37     823  1938.4     832 1931.19   846.31912.272   854.4 1908.37
   892.6 1908.09   922.9 1908.22  934.271912.739   951.4 1925.46   974.2 1927.59
   993.6 1925.26    1008 1918.96  1089.5 1915.07    1151 1917.83  1322.1 1917.72
  1362.2 1915.03  1387.5 1918.03  1483.4 1917.87  1501.8  1923.5  1518.9 1931.89
  1569.3  1939.2  1617.5 1956.37  1715.7 2000.32  1744.3 2009.46    1774 2022.95
#Mann= 10 ,-1 , 0
       0      .1       0   54.57     .05       0   72.34      .1       0
     193     .05       0   846.3    .045       0  934.27     .06       0
 1039.66     .06       0 1312.83     .05       0 1448.19     .06       0
  1454.4      .1       0
#XS Ineff= 2 , 0
                          970.04         1928.67
Permanent Ineff=
       F       F
Bank Sta=846.3,934.27
XS Rating Curve= 0 ,0
Exp/Cntr=0.3,0.1

Type RM Length L Ch R = 1 ,110697  ,370.9,375.7,390.3
XS GIS Cut Line= 3
2405445.43584394625431.5949399622406025.04229626625019.082641631
2406896.76594654624257.117302045
#Sta/Elev= 30
       0 1962.91   249.6 1946.83   561.3 1944.93   749.6  1935.6   756.2 1933.51
   780.8 1917.14   793.4 1913.03     889  1913.2   919.7    1916  946.971909.187
   958.1    1907   996.2 1906.94  1038.8 1907.22 1046.781910.136  1069.6 1923.69
  1085.6  1924.8  1101.1 1923.84  1117.4 1913.98  1132.3 1913.34  1276.9 1916.47
  1483.8 1913.03  1505.3 1915.02    1654 1918.07    1670  1924.1  1684.2 1937.07
  1693.6 1951.51  1701.8 1967.48  1719.1 1988.02  1809.8 2050.68  1869.2 2086.31
#Mann= 12 ,-1 , 0
       0     .05       0   47.13      .1       0  120.69     .05       0
  674.28      .1       0  946.97    .045       0 1046.78    .055       0
 1067.05    .035       0 1140.34    .055       0 1249.45     .06       0
 1608.52     .05       0 1614.27     .06       0 1725.56      .1       0
#XS Ineff= 2 , 0
                         1084.23         1926.38
Permanent Ineff=
       F       F
Bank Sta=946.97,1046.78
XS Rating Curve= 0 ,0
Exp/Cntr=0.5,0.3

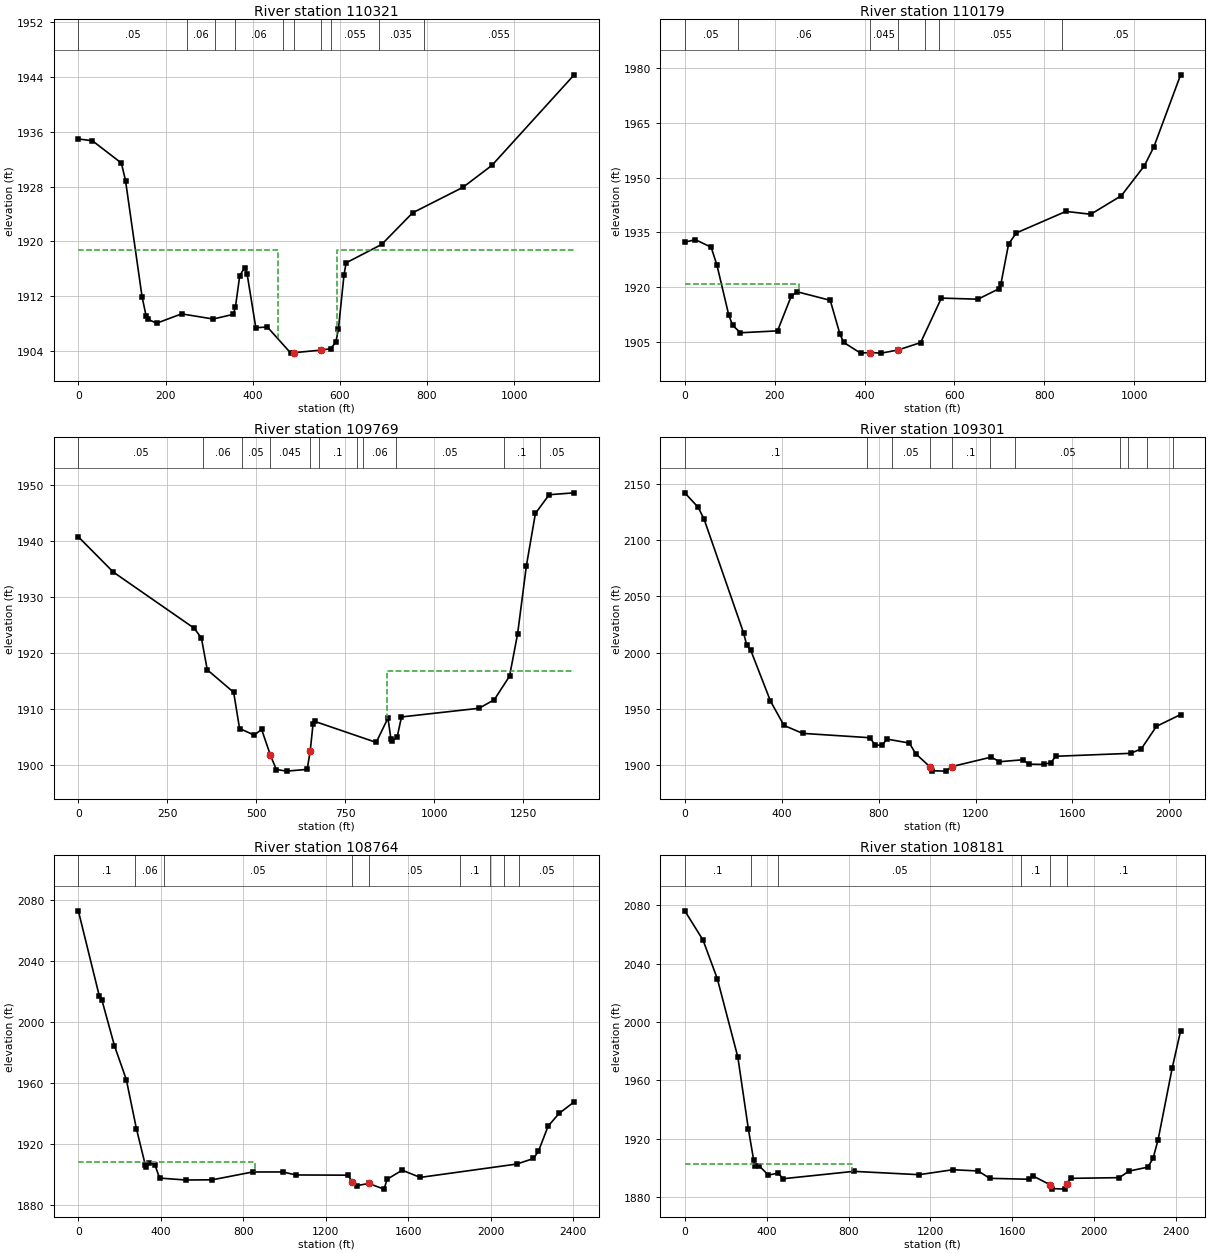
Type RM Length L Ch R = 1 ,110321  ,138.6,142.3,143.4
XS GIS Cut Line= 4
2405931.60416293625463.0423836262406225.45856211625274.647419214
2406497.65158728625083.731462464 2406908.8413817624886.382775798
#Sta/Elev= 30
       0 1934.94    32.2 1934.68    98.8 1931.42   108.3 1928.85   146.3 1911.87
   155.8 1909.03   160.5 1908.61   179.5 1908.04   236.9 1909.41   309.3 1908.66
   355.5 1909.34   360.4 1910.37   370.2 1914.94   381.4 1916.17   387.1 1915.29
   407.2 1907.39   433.7 1907.49   487.4 1903.68  494.561903.745  557.111904.122
   579.5 1904.33     591 1905.35   596.8 1907.22   609.6 1915.14   614.5 1916.86
   696.1 1919.55     767 1924.16   882.4 1927.88     949 1931.09  1137.6  1944.3
#Mann= 10 ,-1 , 0
       0     .05       0  249.96     .06       0  313.92     .05       0
  358.39     .06       0  468.74    .055       0  494.56    .045       0
  557.11      .1       0  579.09    .055       0  688.95    .035       0
  792.49    .055       0
#XS Ineff= 2 , 0
             457  1918.8     594          1918.8
Permanent Ineff=
       F       F
Bank Sta=494.56,557.11
XS Rating Curve= 0 ,0
Exp/Cntr=0.5,0.3

Type RM Length L Ch R = 1 ,110179  ,392.2,410,430.6
XS GIS Cut Line= 4
2405952.77406812625495.9379871342406278.36593661625357.970743373
2406473.32322386625246.1031849682406966.67886445625067.445077717
#Sta/Elev= 30
       0 1932.32    23.7 1932.98    58.6 1930.93    71.6 1925.97    97.7 1912.38
   106.4 1909.53   123.8 1907.48   206.3    1908   236.7 1917.49   249.8 1918.72
   323.6 1916.37   345.3 1907.04   353.6 1904.83   390.9 1901.91  412.171902.069
   437.1  1901.9  474.161902.754   524.7 1904.78   570.8 1916.98   652.2 1916.68
     699 1919.55   703.3 1920.88   720.3 1931.77   737.3 1934.82   847.9 1940.74
   903.2 1939.96   971.3 1945.05  1022.3 1953.22  1043.6 1958.43  1103.1 1978.17
#Mann= 7 ,-1 , 0
       0     .05       0  117.73     .06       0  412.17    .045       0
  474.16    .055       0  533.29    .035       0  566.28    .055       0
  838.66     .05       0
#XS Ineff= 2 , 0
          255.06  1920.8
Permanent Ineff=
       F       F
Bank Sta=412.17,474.16
XS Rating Curve= 0 ,0
Exp/Cntr=0.5,0.3

Type RM Length L Ch R = 1 ,109769  ,496.8,467.9,438.9
XS GIS Cut Line= 3
2405651.78385645625554.7278957962406507.67551735625771.702527463
2406984.55612528625591.909579962
#Sta/Elev= 30
       0 1940.69      98 1934.41   324.9 1924.41   345.6 1922.67   362.1 1916.98
   436.3 1912.96   452.8 1906.51   494.1 1905.33   514.7 1906.36  539.371901.773
     556  1899.2   584.9 1898.91   642.7 1899.22  651.241902.479   659.2  1907.3
   664.3 1907.77   836.6 1904.03   869.6 1908.36   877.9 1904.67     882 1904.35
   895.3 1904.93   907.6 1908.57  1125.6 1910.12  1168.4 1911.65  1211.1 1915.84
  1233.7 1923.36  1258.5 1935.56  1283.8 1944.86  1322.3 1948.19  1392.6 1948.53
#Mann= 11 ,-1 , 0
       0     .05       0  350.47     .06       0  458.71     .05       0
  539.37    .045       0  651.24     .06       0  675.21      .1       0
  783.45    .055       0  799.64     .06       0  891.14     .05       0
 1195.14      .1       0 1296.48     .05       0
#XS Ineff= 2 , 0
                          868.17         1916.76
Permanent Ineff=
       F       F
Bank Sta=539.37,651.24
XS Rating Curve= 0 ,0
Exp/Cntr=0.3,0.1

Type RM Length L Ch R = 1 ,109301  ,563.5,536.6,512.8
XS GIS Cut Line= 3
2405188.05217236626531.6321099552406424.85219219626062.038560957
2407030.24140134625665.567241043
#Sta/Elev= 30
       0 2142.13    55.4  2129.2    79.9 2118.52   242.5 2017.71   255.3 2007.01
   272.4 2002.09   353.7 1957.01   409.3  1935.4   486.4 1928.34   764.5 1924.45
   785.9 1917.74   815.8 1917.98   833.8 1923.28   927.1  1919.7   952.7  1910.3
 1011.191898.789  1021.2 1895.11  1076.8 1894.77 1103.121898.855  1265.1 1907.24
  1298.9 1903.12  1394.4 1904.85  1420.8 1900.93  1482.6 1900.73  1511.7 1902.39
  1530.8 1907.97  1839.8 1910.58  1884.2 1914.55  1946.8 1934.56  2046.6 1945.05
#Mann= 11 ,-1 , 0
       0      .1       0  752.35     .06       0  853.73     .05       0
 1011.19    .045       0 1103.12      .1       0 1259.26    .035       0
 1363.37     .05       0 1798.27      .1       0 1829.79     .05       0
    1907      .1       0 2015.72     .05       0
Bank Sta=1011.19,1103.12
XS Rating Curve= 0 ,0
Exp/Cntr=0.3,0.1

Type RM Length L Ch R = 1 ,108764  ,587,583,595.4
XS GIS Cut Line= 2
2405726.93888986 627670.593086632407092.30558169625692.613774881
#Sta/Elev= 30
       0 2073.03   101.7 2017.12   114.7 2014.23   175.1 1984.49   232.6 1962.25
   281.4 1930.14   324.6 1906.22   330.3 1904.77   344.7  1907.5   370.6  1906.5
     394 1897.62   520.1 1896.36   649.5 1896.49   844.6 1901.62   991.2 1901.64
    1055 1899.66    1308 1899.53  1327.71894.935  1349.2 1892.62 1407.261894.084
  1482.1 1890.37  1496.7 1896.83  1569.7 1902.81    1657 1898.06  2126.1 1906.84
  2206.3 1910.48  2230.6 1915.31  2277.1 1931.68  2330.3 1940.05  2403.5 1947.61
#Mann= 9 ,-1 , 0
       0      .1       0  272.59     .06       0  416.01     .05       0
  1327.7    .045       0 1407.26     .05       0 1850.23      .1       0
 1993.65     .05       0 2061.39      .1       0 2137.07     .05       0
#XS Ineff= 2 , 0
          856.42  1908.1
Permanent Ineff=
       F       F
Bank Sta=1327.7,1407.26
XS Rating Curve= 0 ,0
Exp/Cntr=0.3,0.1

Type RM Length L Ch R = 1 ,108181  ,527.3,532.2,533.9
XS GIS Cut Line= 2
2405934.70455045628028.1320697072407459.97643426626146.490163714
#Sta/Elev= 30
       0 2076.21    89.1 2056.14   158.9 2029.63   259.1 1975.97   310.5 1926.71
   336.7 1905.12     345 1901.11   362.1 1901.53   408.4 1895.13   455.9 1896.38
   480.5  1892.6   825.5 1897.65  1144.7 1895.37  1309.5 1898.77  1433.1 1897.91
  1489.7 1892.86  1680.2 1892.25  1702.4 1894.39 1782.671888.593  1795.4 1885.85
  1855.3 1885.47 1866.611889.073  1886.2 1892.86    2123 1893.33  2169.4 1897.81
  2261.8 1900.53  2287.4 1906.48  2312.3 1919.42  2381.2 1968.56  2422.2 1993.94
#Mann= 6 ,-1 , 0
       0      .1       0  321.13     .06       0  454.27     .05       0
 1641.72      .1       0 1782.67    .045       0 1866.61      .1       0
#XS Ineff= 2 , 0
          818.26 1902.45
Permanent Ineff=
       F       F
Bank Sta=1782.67,1866.61
XS Rating Curve= 0 ,0
Exp/Cntr=0.3,0.1

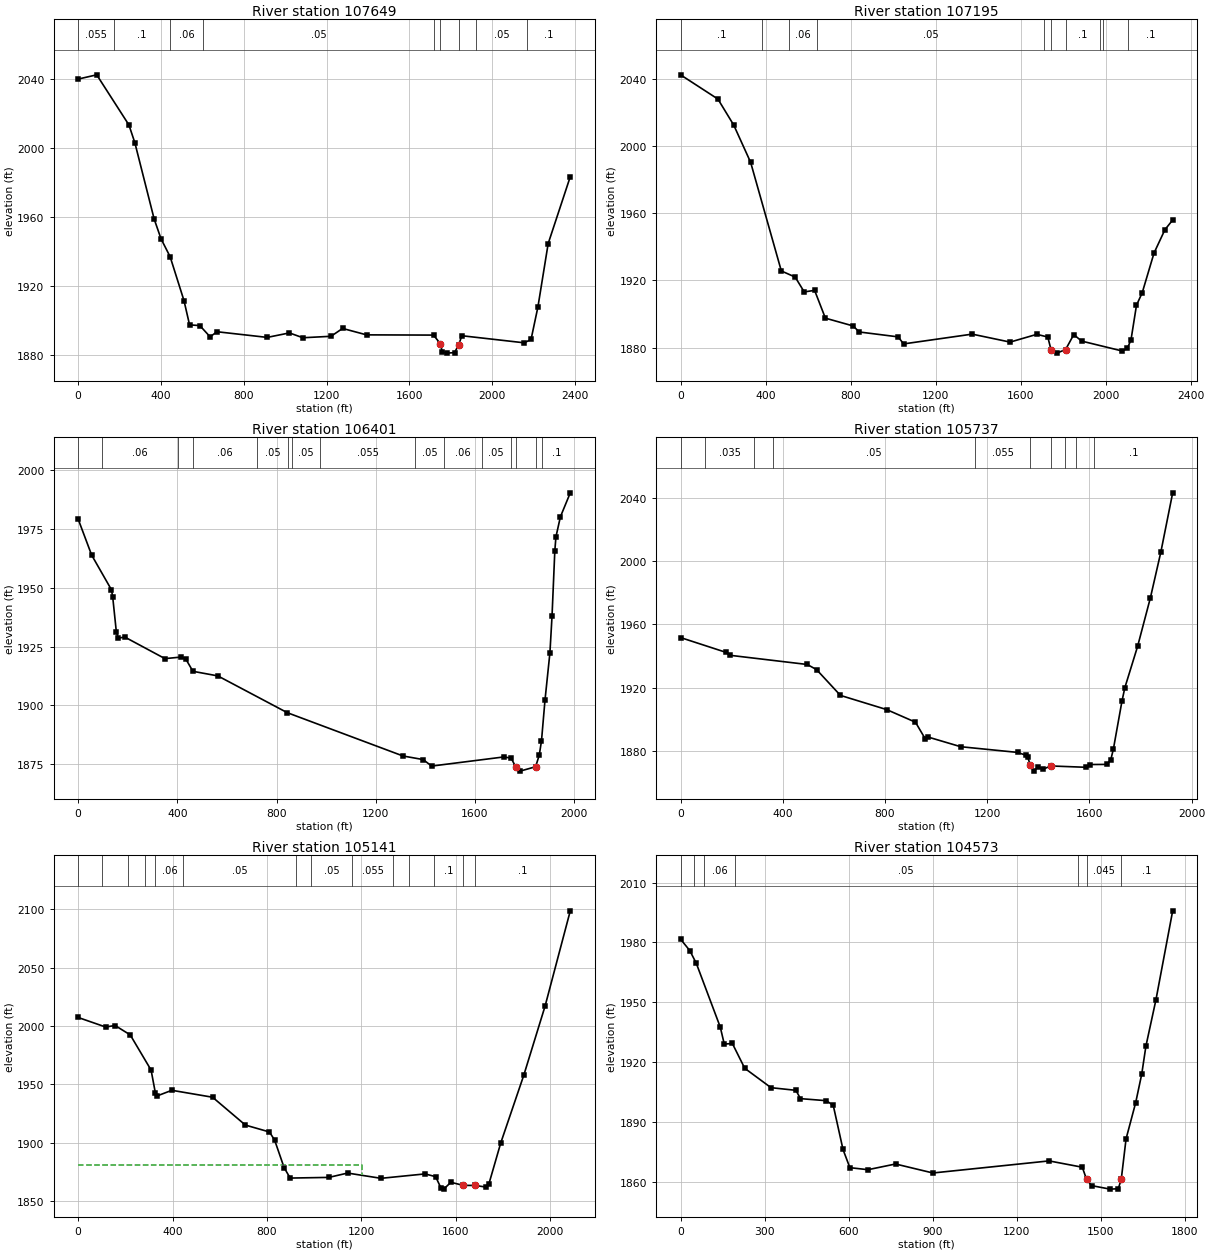
Type RM Length L Ch R = 1 ,107649  ,460.3,454.3,450.7
XS GIS Cut Line= 2
2406270.13662237628221.0634423792407907.43912202626497.487165123
#Sta/Elev= 30
       0 2040.03    89.7  2042.5   245.3  2013.4   273.9 2003.08   367.1 1958.83
   400.2 1947.36   444.4 1936.89   511.3 1911.42   538.2 1897.36   587.8 1896.94
   637.5 1890.42   670.6 1893.37   913.3 1890.08  1020.5 1892.68  1085.6 1889.88
  1221.4 1890.72  1277.4 1895.28  1393.3 1891.55  1716.6 1891.42    1750 1886.37
    1759 1881.66  1779.5 1880.95  1818.1 1881.24  1837.91885.693  1853.6 1891.05
  2154.7 1886.94  2187.8 1888.88  2220.9  1907.7  2270.5 1944.53  2377.3 1983.39
#Mann= 9 ,-1 , 0
       0    .055       0  173.32      .1       0  443.39     .06       0
  603.11     .05       0 1721.12      .1       0    1750    .045       0
  1837.9      .1       0 1920.34     .05       0 2169.91      .1       0
Bank Sta=1750,1837.9
XS Rating Curve= 0 ,0
Exp/Cntr=0.3,0.1

Type RM Length L Ch R = 1 ,107195  ,783.8,794.2,793.7
XS GIS Cut Line= 3
2406755.14483869628504.9588719612407105.13298386628119.980967373
2408237.07461759626726.783622548
#Sta/Elev= 30
       0 2042.24   175.8 2027.82   250.4 2012.31   329.7 1990.19   474.1 1925.59
   539.3 1921.93   581.9 1913.11   630.7 1914.04   681.4  1897.5   812.2 1892.86
   840.7 1889.28    1024 1886.37  1049.3 1882.18  1372.1    1888  1550.5 1883.26
  1676.1 1887.88  1727.9 1886.27 1743.661878.391  1770.5  1876.7 1811.631878.849
  1850.1 1887.74  1886.7 1883.87  2078.1 1877.97  2102.3 1879.59  2119.4 1884.66
  2145.1 1905.19  2172.1 1912.62  2227.6 1936.23  2279.1 1950.18  2315.4 1955.87
#Mann= 10 ,-1 , 0
       0      .1       0   384.1    .055       0  511.03     .06       0
   643.6     .05       0  1707.7      .1       0 1743.66    .045       0
 1811.63      .1       0 1973.73     .05       0 1985.52      .1       0
 2106.74      .1       0
Bank Sta=1743.66,1811.63
XS Rating Curve= 0 ,0
Exp/Cntr=0.3,0.1

Type RM Length L Ch R = 1 ,106401  ,666.7,663.2,683.7
XS GIS Cut Line= 2
2407434.05325776628715.5985425412408753.20416278627233.409577802
#Sta/Elev= 30
       0 1979.31    54.5 1963.97   134.2 1949.24   139.4 1946.11     154 1931.29
   161.6 1928.67   188.4 1929.09     350 1919.93   416.2 1920.61   434.5 1919.67
   462.8 1914.53   563.2 1912.58   843.4 1896.92  1309.9  1878.5  1390.9 1876.98
  1425.3 1874.21  1715.8 1878.09  1745.9  1877.6 1764.611873.746    1782 1872.06
 1844.461873.937  1859.1 1878.87  1868.1 1884.89  1882.2 1902.21  1902.1 1922.41
  1910.6 1937.97  1921.9 1965.88  1926.4 1971.76  1944.4 1980.28  1984.2 1990.48
#Mann= 15 ,-1 , 0
       0      .1       0   94.91     .06       0  401.59    .055       0
  463.14     .06       0  719.17     .05       0  847.18      .1       0
  861.62     .05       0   975.2    .055       0 1359.24     .05       0
 1474.98     .06       0 1628.32     .05       0 1743.29      .1       0
 1764.61    .045       0 1844.46     .05       0 1871.31      .1       0
Bank Sta=1764.61,1844.46
XS Rating Curve= 0 ,0
Exp/Cntr=0.3,0.1

Type RM Length L Ch R = 1 ,105737  ,608.2,596.1,596.2
XS GIS Cut Line= 3
2407785.65950993629089.3527162972408586.09032378 628119.62499696
2409120.37140745627718.529342458
#Sta/Elev= 30
       0 1951.63   178.7 1942.24   192.9 1940.44   495.9 1934.62   532.2 1931.37
   625.6 1915.08   806.6 1906.11   919.1 1898.15   956.8  1887.8   968.6 1888.76
  1096.4 1882.65  1318.4 1879.06  1352.7 1877.19  1358.3 1876.05 1368.751870.926
  1381.2 1867.23  1398.5 1869.86  1418.4 1868.41 1448.281870.499  1588.3 1869.64
  1601.2  1871.4  1668.4 1871.48  1683.4 1874.48  1693.4 1881.09  1726.9 1911.29
  1738.3 1919.94  1788.4 1946.16  1838.4 1976.83    1879 2005.52  1925.5  2043.1
#Mann= 10 ,-1 , 0
       0      .1       0   95.85    .035       0  287.64    .055       0
  360.06     .05       0 1152.69    .055       0 1368.75    .045       0
 1448.28    .055       0 1504.97      .1       0 1546.55      .1       0
 1617.13      .1       0
Bank Sta=1368.75,1448.28
XS Rating Curve= 0 ,0
Exp/Cntr=0.3,0.1

Type RM Length L Ch R = 1 ,105141  ,563.8,568.5,572.4
XS GIS Cut Line= 3
2407949.66836828629517.9817802912408310.75327602629198.289178208
 2409482.9677951628106.096152633
#Sta/Elev= 30
       0 2007.23   116.3 1999.06   156.4 2000.34   220.5 1992.32     309  1962.1
   327.3 1942.25   332.7 1939.85   396.8 1944.81   569.4 1938.86   708.3    1915
   810.3 1909.09   832.2  1902.1   872.4  1878.5     898 1869.58  1061.8 1870.15
  1141.3 1873.87  1282.8 1869.36  1469.6 1873.15  1514.1 1870.77  1537.4 1860.75
  1548.4  1860.1  1578.7 1865.95 1631.291863.326 1681.541863.228  1728.8 1861.83
  1739.7 1864.55  1789.9 1899.68  1887.3 1957.62  1977.7 2016.99  2084.4 2098.63
#Mann= 14 ,-1 , 0
       0      .1       0  101.13      .1       0   209.9     .05       0
  281.73      .1       0  327.42     .06       0  444.93     .05       0
  922.18      .1       0   984.4     .05       0 1161.12    .055       0
 1331.95      .1       0 1400.06     .05       0 1505.72      .1       0
 1631.29    .045       0 1681.54      .1       0
#XS Ineff= 2 , 0
         1201.24 1880.46
Permanent Ineff=
       F       F
Bank Sta=1631.29,1681.54
XS Rating Curve= 0 ,0
Exp/Cntr=0.3,0.1

Type RM Length L Ch R = 1 ,104573  ,626.8,650.9,660.9
XS GIS Cut Line= 2
2408289.17425093629727.4725030512409712.15631312628695.759343371
#Sta/Elev= 30
       0 1981.66      33 1975.94    56.3 1969.52   141.9 1937.52   156.2 1929.01
     185 1929.34   229.2 1916.88   323.1 1907.15     412 1905.82   428.3 1901.65
   520.7 1900.62   545.4 1898.24   580.2 1876.14   604.7 1867.02   669.3    1866
   767.8 1868.86   901.2 1864.35  1316.2 1870.41  1434.8 1867.24 1450.051861.145
    1468 1858.01  1534.2 1856.25  1563.2 1856.45 1573.891861.113  1591.1 1881.46
  1625.5 1899.66  1647.2 1914.06    1662 1928.01  1697.8 1951.24  1757.6 1995.88
#Mann= 7 ,-1 , 0
       0      .1       0   46.43    .055       0   83.35     .06       0
  194.55     .05       0 1417.79      .1       0 1450.05    .045       0
 1573.89      .1       0
Bank Sta=1450.05,1573.89
XS Rating Curve= 0 ,0
Exp/Cntr=0.3,0.1