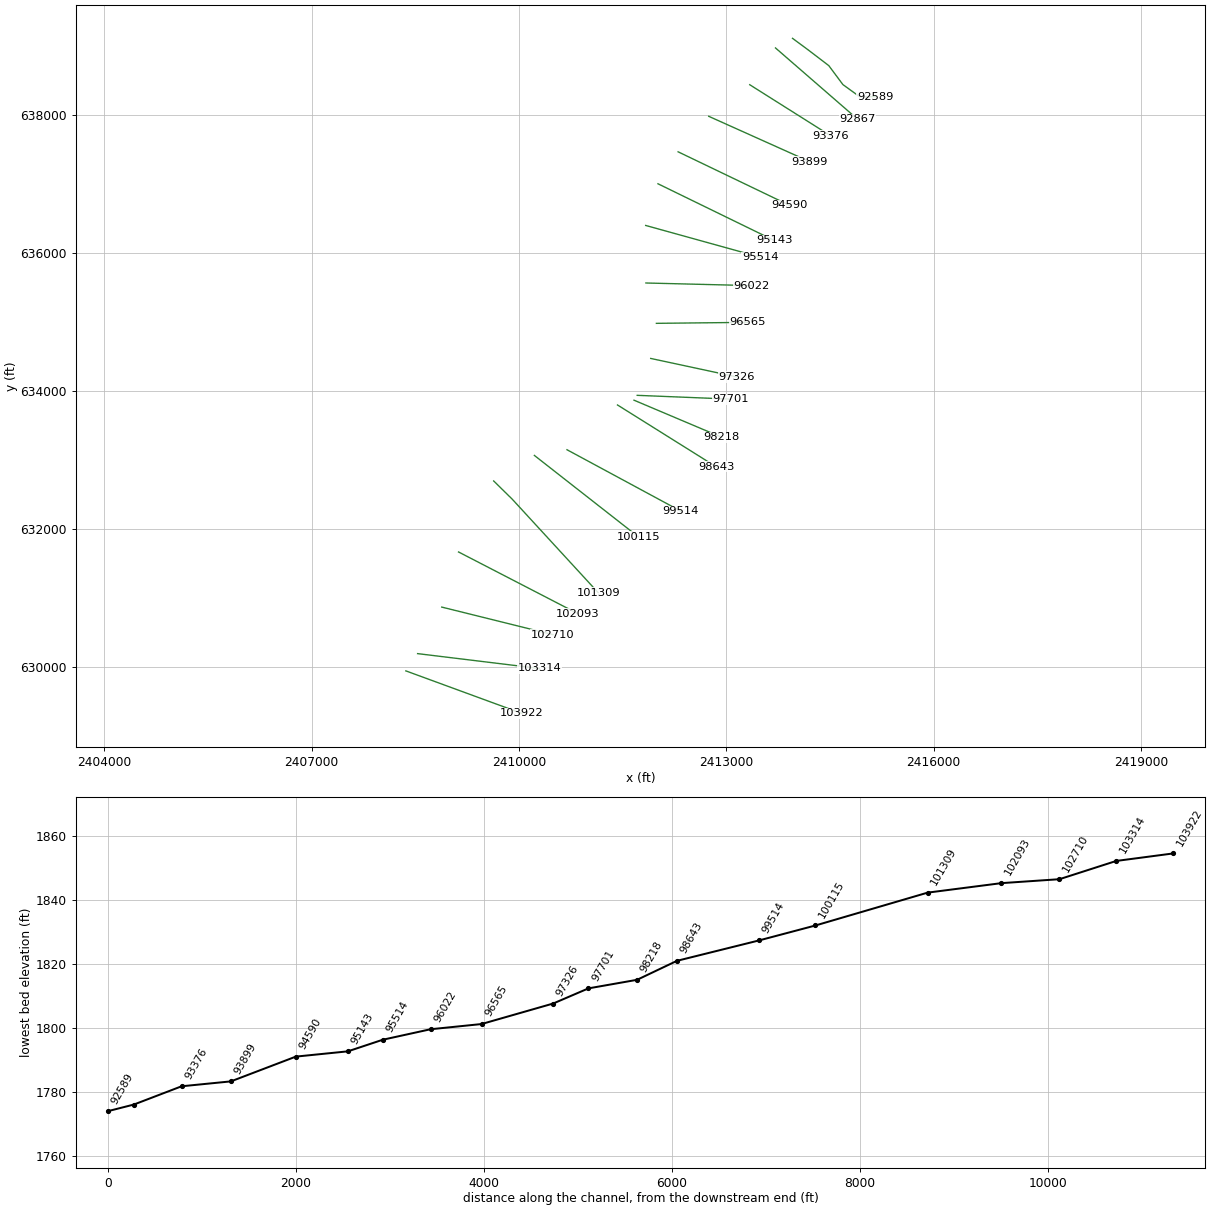
HEC-RAS study NFSBPOTOMC.prj: NFSBPOTOMC

--- NFSBPOTOMC.g01 (geometry) --- (continued)

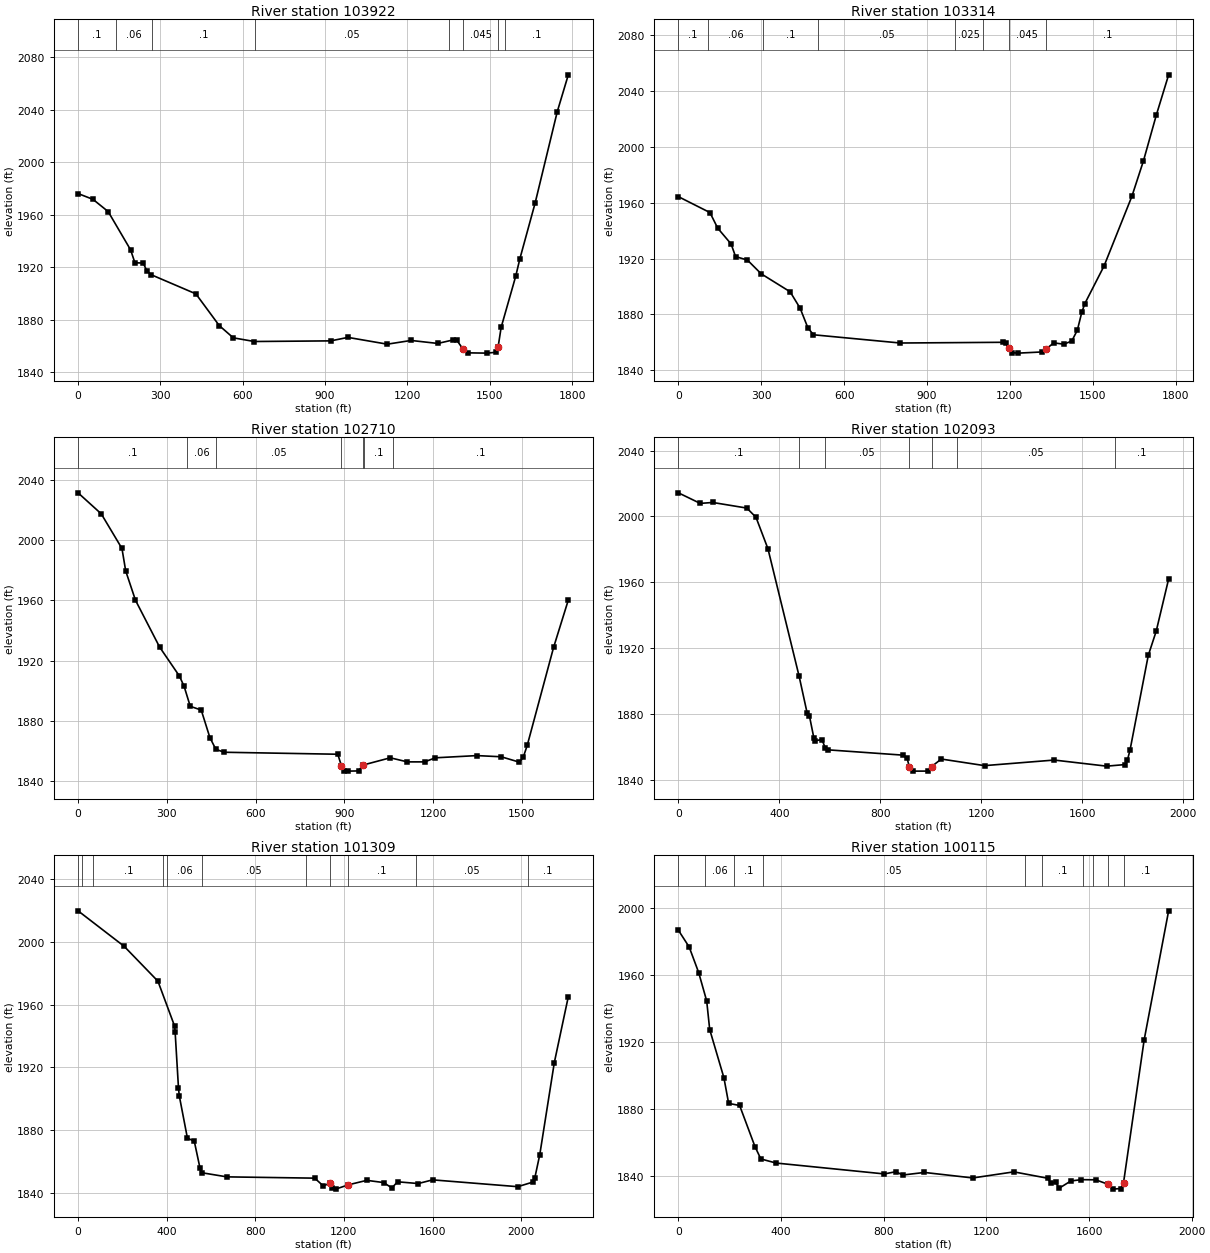
Type RM Length L Ch R = 1 ,103922  ,591.9,608.3,620.5
XS GIS Cut Line= 2
2408363.77318311629945.7004130482410040.44699511629330.429333881
#Sta/Elev= 30
       0 1976.03    54.4 1971.62   109.7  1962.3   191.5 1933.14   207.1 1923.34
   237.5 1923.12   250.3 1917.33   267.3 1914.16   429.2 1899.68   514.5  1875.5
   565.6 1866.19   642.3  1863.4   920.9 1863.88   983.2 1866.53  1126.6 1861.36
  1213.2  1864.2  1310.5 1861.92  1366.7 1864.62  1379.4 1864.46 1402.431857.635
    1422 1854.75  1490.2 1854.55  1524.3 1855.25 1530.28 1859.17  1541.3 1874.11
  1594.2  1912.9  1609.5 1926.34  1664.9 1968.61  1745.8 2038.38    1786 2066.42
#Mann= 8 ,-1 , 0
       0      .1       0  137.55     .06       0  271.02      .1       0
  643.33     .05       0 1351.42    .055       0 1402.43    .045       0
 1530.28      .1       0 1553.73      .1       0
Bank Sta=1402.43,1530.28
XS Rating Curve= 0 ,0
Exp/Cntr=0.3,0.1

Type RM Length L Ch R = 1 ,103314  ,606.3,604,605.9
XS GIS Cut Line= 2
2408533.34502244630195.8472224622410294.68926877629981.264318287
#Sta/Elev= 30
       0 1964.33   114.2 1952.93   142.4 1941.73   190.8 1930.42   206.9  1921.4
     250 1918.86   299.6 1909.05   404.4 1896.16   440.6 1884.39   468.8 1870.29
     489 1865.34   803.1 1859.44    1174 1859.95  1186.1 1859.18  1194.91855.757
  1206.3 1852.51  1230.3 1852.19  1315.1 1853.02 1330.771855.115  1358.7 1859.54
  1395.4 1858.59  1423.9 1860.88    1444 1868.62  1460.1 1881.46  1471.2 1887.72
  1540.7 1914.65  1641.4 1964.53  1683.2 1989.92  1730.1 2022.96  1774.4 2051.63
#Mann= 8 ,-1 , 0
       0      .1       0   107.1     .06       0  305.89      .1       0
  504.68     .05       0 1001.65    .025       0 1101.05     .05       0
  1194.9    .045       0 1330.77      .1       0
Bank Sta=1194.9,1330.77
XS Rating Curve= 0 ,0
Exp/Cntr=0.3,0.1

Type RM Length L Ch R = 1 ,102710  ,625.3,616.4,606
XS GIS Cut Line= 2
2408882.70029485630869.9236302082410490.77844352630470.563208461
#Sta/Elev= 30
       0 2031.57    78.4  2017.6   148.4 1994.55     161 1979.65     194 1960.16
   275.5 1929.04   342.6 1909.71   358.6 1902.77   379.2 1889.59   416.3  1887.1
   445.5 1868.82   465.8 1860.94   494.5 1859.03   877.9 1857.71  890.351849.853
   898.5 1846.58   910.9 1846.48     948 1846.62  962.211850.471  1055.2 1855.35
  1112.9 1852.63  1171.3 1852.63  1207.5 1855.34  1347.8 1856.81  1430.2 1856.03
  1491.5 1852.45  1504.4  1855.6    1518 1863.54  1607.4 1928.92  1656.9 1960.24
#Mann= 7 ,-1 , 0
       0      .1       0   367.9     .06       0  467.56     .05       0
  890.35    .045       0  962.21     .05       0  965.84      .1       0
  1065.5      .1       0
Bank Sta=890.35,962.21
XS Rating Curve= 0 ,0
Exp/Cntr=0.3,0.1

Type RM Length L Ch R = 1 ,102093  ,800.7,784.7,771.8
XS GIS Cut Line= 2
2409125.87861428631668.1559576242410850.43848535630775.868372127
#Sta/Elev= 30
       0 2014.36    86.5 2007.94   136.1  2008.5   271.2 2005.09   307.4 1999.49
   354.8 1980.35   478.4 1902.78   509.9 1880.59   518.9 1878.89   536.9 1865.19
   541.4 1863.72   568.5 1864.43     582 1859.26     591  1858.2   888.2 1854.98
   906.2 1853.07  914.931847.468   928.7 1845.25   987.3 1845.27 1002.821848.007
  1041.3  1852.6  1212.5 1848.59  1488.6 1851.98  1696.3 1848.27  1769.8 1849.24
  1778.5 1851.94  1788.9 1858.11    1861 1915.52  1892.5 1930.29  1941.7 1962.01
#Mann= 7 ,-1 , 0
       0      .1       0  476.71     .06       0  581.22     .05       0
  914.93    .045       0 1002.82      .1       0  1103.8     .05       0
 1730.89      .1       0
Bank Sta=914.93,1002.82
XS Rating Curve= 0 ,0
Exp/Cntr=0.3,0.1

Type RM Length L Ch R = 1 ,101309  ,1205.9,1193.3,1203.3
XS GIS Cut Line= 3
2409634.44518244632696.3832318782409903.49352884632431.626215458
2411145.00909045631080.121044457
#Sta/Elev= 30
       0 2019.75   208.1 1997.12   360.5 1974.88   435.5 1946.33   438.2 1942.37
   453.2 1906.99   456.7 1901.94   493.5 1874.86   524.7 1872.77   550.1 1855.89
   558.6 1852.73   671.8  1850.1  1068.2 1849.28  1106.3 1844.38 1137.141845.951
    1145 1843.02  1162.8 1842.28 1218.971844.987  1303.2 1847.88  1379.6 1846.46
  1416.4 1843.01  1441.9 1846.96  1535.3 1845.84  1600.4 1848.19  1984.6 1843.84
  2051.4 1846.71  2061.5  1849.4    2084  1864.3  2149.6 1922.98  2212.7 1964.99
#Mann= 11 ,-1 , 0
       0      .1       0   19.91      .1       0   69.19      .1       0
  385.41      .1       0  401.75     .06       0   558.1     .05       0
 1027.14      .1       0 1137.14    .045       0 1218.97      .1       0
 1523.13     .05       0 2028.79      .1       0
Bank Sta=1137.14,1218.97
XS Rating Curve= 0 ,0
Exp/Cntr=0.3,0.1

Type RM Length L Ch R = 1 ,100115  ,590.5,601.5,612.1
XS GIS Cut Line= 2
2410223.10739094633066.158739045 2411726.5853551631888.164703965
#Sta/Elev= 30
       0 1986.45      42 1976.47      79 1961.22   110.3 1944.26     122 1927.23
   177.4 1898.43   195.8 1883.16   238.6  1881.9   298.4 1857.38   321.2 1850.01
   380.7 1847.56   802.7 1841.06   847.2  1842.4   873.9 1840.41   958.7 1841.95
  1147.4 1838.67    1307  1842.3  1438.1 1838.52  1451.6 1835.54  1469.4 1836.11
    1484 1832.59  1529.1 1836.87  1569.7 1837.65  1626.1 1837.55 1672.69 1834.97
  1691.6    1832    1723 1832.35 1734.191835.706  1814.8 1921.15    1910 1998.03
#Mann= 10 ,-1 , 0
       0      .1       0  103.06     .06       0  217.03      .1       0
  329.89     .05       0 1350.59      .1       0 1414.82      .1       0
 1577.41     .05       0 1614.45      .1       0 1672.69    .045       0
 1734.19      .1       0
Bank Sta=1672.69,1734.19
XS Rating Curve= 0 ,0
Exp/Cntr=0.3,0.1

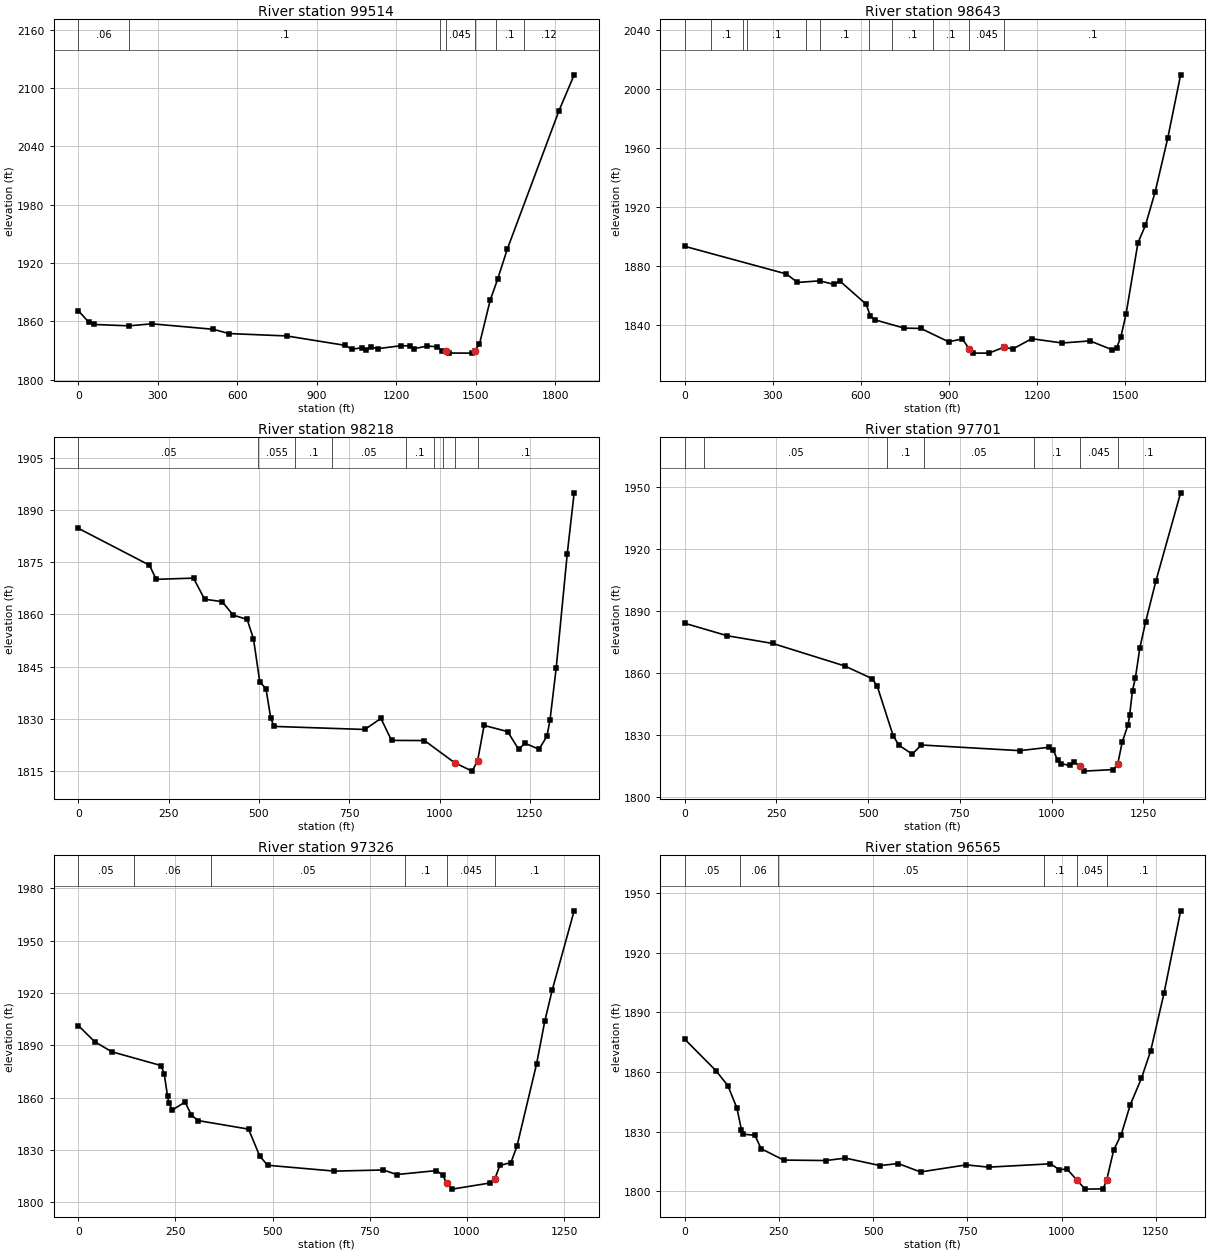
Type RM Length L Ch R = 1 ,99514   ,870.3,871.1,860.3
XS GIS Cut Line= 2
 2410694.7564993633148.9332457242412341.14034564632259.717176383
#Sta/Elev= 30
       0 1870.93    39.9 1858.96    59.1 1856.78   190.9 1855.37   277.3 1857.45
   509.2 1851.82   568.2 1847.44   786.5 1844.97  1008.1 1835.24    1032 1831.23
  1070.1 1832.89  1086.5 1830.83  1104.7 1833.15  1132.1 1831.97  1218.4 1834.95
  1250.1 1834.75  1264.9 1831.81  1317.4 1834.61  1354.7 1833.78  1372.9 1829.75
  1386.6 1829.81  1400.2  1827.4  1485.7 1827.31  1495.1 1829.43  1513.9 1836.63
  1554.2 1881.56    1582 1903.03  1619.1 1934.46  1813.9 2076.57  1871.2  2113.5
#Mann= 7 ,-1 , 0
       0     .06       0  192.78      .1       0 1366.16     .05       0
  1386.6    .045       0  1495.1    .055       0 1576.45      .1       0
 1681.59     .12       0
Bank Sta=1386.6,1495.1
XS Rating Curve= 0 ,0
Exp/Cntr=0.3,0.1

Type RM Length L Ch R = 1 ,98643   ,424.3,424.2,400.4
XS GIS Cut Line= 2
2411425.67117311633797.0675086982412856.24475552632900.020418272
#Sta/Elev= 30
       0 1893.39   345.9 1874.66   383.7  1868.9   459.2 1869.97   508.6 1867.57
   527.6 1869.94   617.5 1854.13     632 1846.12   648.1 1843.49   747.2 1837.91
   803.9 1837.69   898.3 1828.63   945.3 1830.57   967.9 1823.98   982.9 1820.95
  1035.4 1820.94  1087.6 1824.99  1116.6 1823.71  1181.6 1830.71  1285.5 1827.81
  1379.9 1829.23  1456.1 1823.17  1470.7 1824.48  1485.2 1832.03  1502.7 1847.37
  1543.2 1895.74  1568.8 1907.68  1601.8 1930.29  1644.8 1966.89  1688.6 2009.77
#Mann= 11 ,-1 , 0
       0    .055       0   89.56      .1       0  197.36     .05       0
  212.54      .1       0  412.95     .05       0  459.55      .1       0
  628.55    .055       0  706.56      .1       0  844.15      .1       0
   967.9    .045       0  1087.6      .1       0
Bank Sta=967.9,1087.6
XS Rating Curve= 0 ,0
Exp/Cntr=0.3,0.1

Type RM Length L Ch R = 1 ,98218   ,493.7,517.1,531.3
XS GIS Cut Line= 2
2411664.21901003633866.3995926232412928.34541878633331.258602545
#Sta/Elev= 30
       0 1884.72   196.9 1874.14   215.6 1870.07   318.9 1870.42   349.5 1864.36
   398.3 1863.66   428.4 1859.82   467.5 1858.55   484.9 1852.97   502.3  1840.7
   519.6 1838.59   532.7 1830.25   541.7 1827.84   793.3 1826.96   837.7 1830.14
   867.1 1823.82   958.3 1823.78 1041.521817.426  1090.3    1815 1105.371817.981
  1123.4 1828.12  1188.6 1826.35    1219 1821.25  1236.3 1823.02  1275.4 1821.28
  1297.2    1825  1305.8 1829.64    1323 1844.61  1353.6 1877.45  1372.7 1894.91
#Mann= 9 ,-1 , 0
       0     .05       0  498.45    .055       0  600.69      .1       0
  702.93     .05       0  907.41      .1       0   985.5     .05       0
 1009.65      .1       0 1041.52    .045       0 1105.37      .1       0
Bank Sta=1041.52,1105.37
XS Rating Curve= 0 ,0
Exp/Cntr=0.3,0.1

Type RM Length L Ch R = 1 ,97701   ,383.1,375.1,364.2
XS GIS Cut Line= 2
2411710.82882494633936.6002396352413061.80807835633882.048839539
#Sta/Elev= 30
       0    1884     116 1877.97   240.1 1874.22   436.2 1863.32   511.3 1857.14
   524.9 1853.42   568.4 1829.37   584.4 1824.82   620.4 1820.55   644.4    1825
   913.5 1822.25   992.7 1823.88  1004.7 1822.59  1016.7 1817.59  1024.8 1815.97
  1049.4 1815.11  1061.9 1816.61 1076.881814.898  1088.8 1812.32  1168.9 1813.07
 1180.581815.804  1192.9 1826.43  1208.9 1834.91  1212.9 1839.36  1220.9 1851.41
  1228.9 1857.71  1240.9 1872.08  1256.9 1884.88    1285 1904.72  1352.1 1947.28
#Mann= 7 ,-1 , 0
       0    .055       0   52.53     .05       0  552.74      .1       0
  652.78     .05       0  952.91      .1       0 1076.88    .045       0
 1180.58      .1       0
Bank Sta=1076.88,1180.58
XS Rating Curve= 0 ,0
Exp/Cntr=0.3,0.1

Type RM Length L Ch R = 1 ,97326   ,753.2,761.7,768.9
XS GIS Cut Line= 2
2411906.40717393634471.0335539582413153.84595203634202.994063795
#Sta/Elev= 30
       0 1901.38    41.9 1892.16    86.3 1886.33   213.1 1878.43   221.3 1873.36
   229.5  1860.9   233.5 1856.76   241.7 1852.94   274.5  1857.5   290.8 1850.16
   307.7 1846.91     438 1841.99   466.8 1826.52   487.2 1821.26     659 1817.91
   785.1 1818.56   819.4 1815.94   920.9 1818.19   937.3 1815.76  947.941811.057
   961.8 1807.58    1060 1811.12 1071.931813.475  1084.5 1821.15  1113.2 1822.81
  1128.6 1832.11  1179.1 1879.27  1200.2 1903.81  1219.6 1921.86  1275.9 1967.17
#Mann= 6 ,-1 , 0
       0     .05       0  143.46     .06       0  342.35     .05       0
  839.58      .1       0  947.94    .045       0 1071.93      .1       0
Bank Sta=947.94,1071.93
XS Rating Curve= 0 ,0
Exp/Cntr=0.3,0.1

Type RM Length L Ch R = 1 ,96565   ,543.9,542.4,541.3
XS GIS Cut Line= 2
2411988.47065809634979.3255163732413304.26559868634993.651931301
#Sta/Elev= 30
       0 1876.49    82.3 1860.78   114.3 1853.18   138.3  1841.9   150.3 1831.03
   154.3 1828.81   186.3 1828.21   202.3 1821.51   262.3 1815.77   374.3 1815.53
   426.3 1816.76   518.3    1813   566.3 1814.01   625.6 1809.79   746.9 1813.35
   806.3 1812.21   970.3 1813.88   994.3 1810.91  1014.3 1811.31  1039.91805.842
  1062.3 1801.16  1110.3  1801.3 1119.891805.923  1138.3 1820.83  1158.3  1828.6
  1182.3 1843.59    1212 1856.91  1236.5 1870.73  1272.1 1899.88  1315.9 1941.07
#Mann= 6 ,-1 , 0
       0     .05       0  145.76     .06       0  246.56     .05       0
  952.15      .1       0  1039.9    .045       0 1119.89      .1       0
Bank Sta=1039.9,1119.89
XS Rating Curve= 0 ,0
Exp/Cntr=0.3,0.1

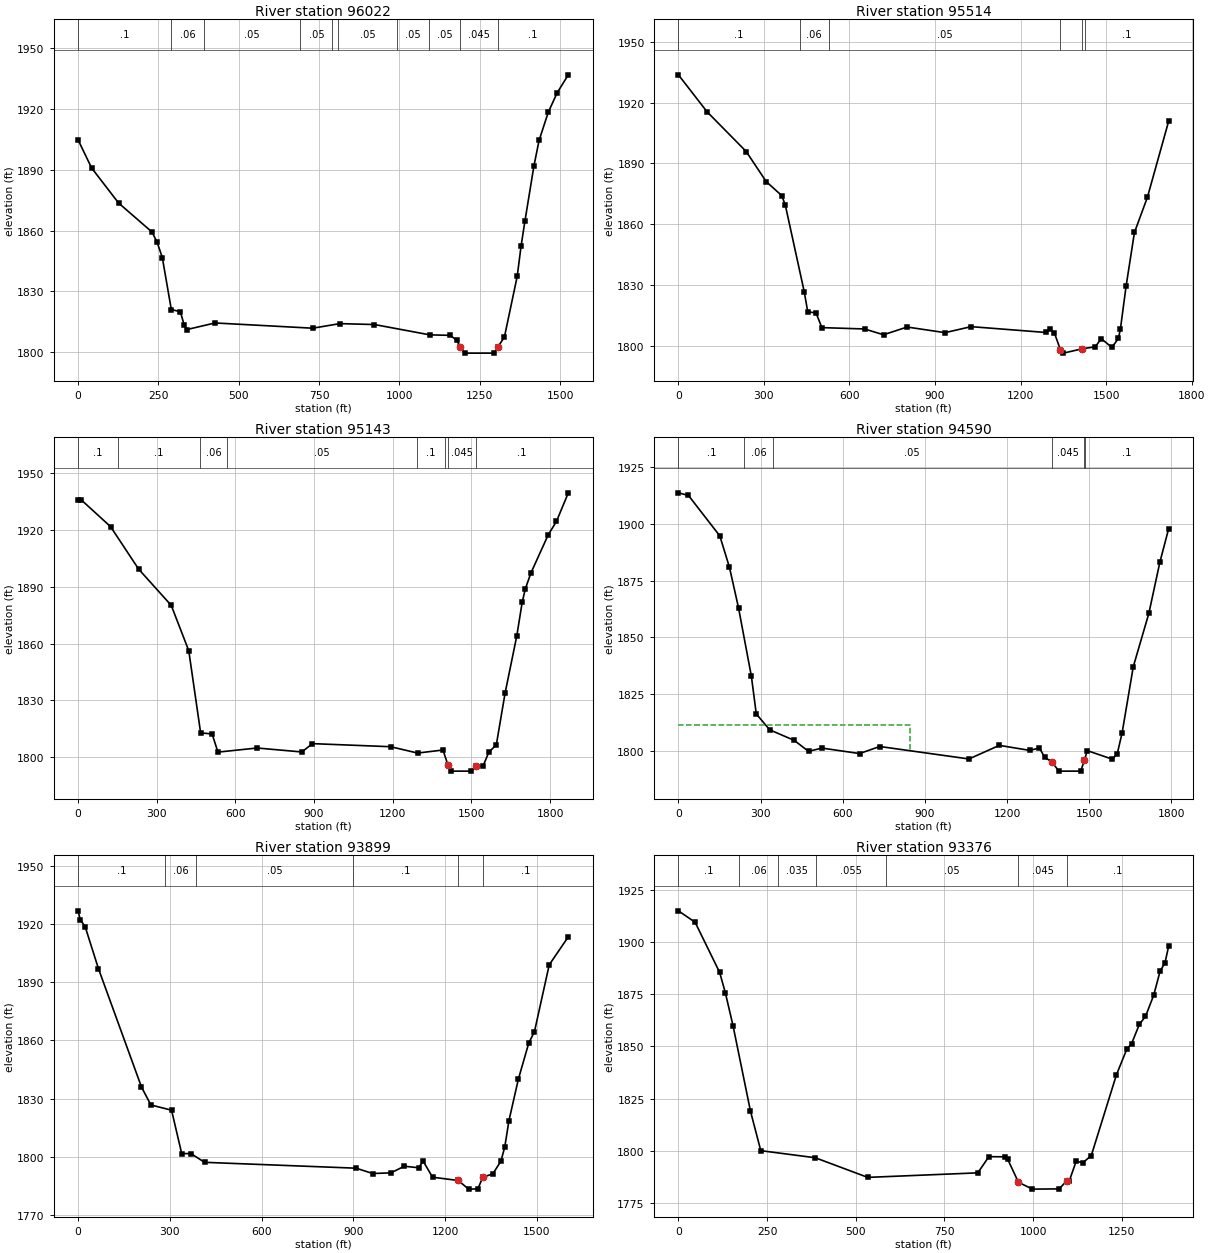
Type RM Length L Ch R = 1 ,96022   ,517.2,507.8,493.2
XS GIS Cut Line= 2
2411836.65632918635563.700988039 2413361.6372031635525.851654291
#Sta/Elev= 30
       0 1904.82    42.1 1890.94   126.1 1873.62   230.2 1859.29   246.2 1854.18
   262.2 1846.69   290.2 1821.02   318.2    1820   330.2 1813.45   338.2 1811.15
   426.2 1814.42   730.3 1811.83   814.3 1814.09   922.4 1813.64  1094.4 1808.55
  1158.5 1808.31  1178.5 1805.81 1190.011802.398  1202.5 1799.53  1294.5 1799.53
 1305.821802.531  1326.5 1807.35  1366.5 1837.42  1378.5 1852.36  1390.5 1864.72
  1418.5 1891.91  1434.5  1904.5    1463 1918.35  1490.5 1927.95  1525.5 1936.89
#Mann= 10 ,-1 , 0
       0      .1       0  290.37     .06       0  390.61     .05       0
  691.34     .05       0  791.58     .05       0  808.41     .05       0
  992.07     .05       0 1092.31     .05       0 1190.01    .045       0
 1305.82      .1       0
Bank Sta=1190.01,1305.82
XS Rating Curve= 0 ,0
Exp/Cntr=0.3,0.1

Type RM Length L Ch R = 1 ,95514   ,376.7,371,363.3
XS GIS Cut Line= 2
2411833.60088912636397.0201875422413490.40236554635937.672352955
#Sta/Elev= 30
       0 1933.82   100.8 1915.51   237.8 1895.91   308.1 1881.02   362.3 1874.15
   374.8 1869.52   441.4 1826.55   453.6 1816.67   482.7 1816.14   503.1 1808.86
   652.9 1808.19   719.3 1805.33   802.1 1809.15   935.1 1806.37  1026.5 1809.34
    1288 1806.47  1304.6 1808.15  1318.9 1806.11 1339.461798.026  1350.2 1796.25
 1415.431798.371  1461.8 1799.39  1483.1 1803.39  1520.3 1799.06  1543.1 1803.54
  1550.1 1808.16  1570.2  1829.5  1599.3 1855.88  1644.9 1873.34  1719.3  1910.9
#Mann= 6 ,-1 , 0
       0      .1       0  426.65     .06       0  526.57     .05       0
 1339.46    .045       0 1415.43     .05       0 1425.83      .1       0
Bank Sta=1339.46,1415.43
XS Rating Curve= 0 ,0
Exp/Cntr=0.3,0.1

Type RM Length L Ch R = 1 ,95143   ,552.1,553.4,553
XS GIS Cut Line= 2
 2412011.3505336637000.6141247152413691.34684554636180.514386967
#Sta/Elev= 30
       0 1935.82      13 1935.89     124 1921.84   231.1 1899.38   355.4 1880.21
   422.2 1856.25   467.4 1812.86   511.2 1812.25   533.5 1802.67   682.8 1804.84
   853.3 1802.75     894 1807.15  1192.2 1805.52  1294.6 1802.17  1391.7 1803.78
  1410.11795.955  1423.7 1792.62  1499.4 1792.62 1517.951795.381  1543.9 1795.18
  1566.1 1802.54  1595.1 1806.61  1628.4 1833.88    1673 1864.07  1693.8 1882.03
  1705.7 1888.97  1726.4  1897.2  1793.1 1917.57  1824.3 1924.62  1869.5 1939.72
#Mann= 8 ,-1 , 0
       0      .1       0  153.14      .1       0  464.39     .06       0
  568.14     .05       0 1294.39      .1       0 1398.14     .05       0
  1410.1    .045       0 1517.95      .1       0
Bank Sta=1410.1,1517.95
XS Rating Curve= 0 ,0
Exp/Cntr=0.3,0.1

Type RM Length L Ch R = 1 ,94590   ,690.5,690.6,691.1
XS GIS Cut Line= 2
2412302.48840278637463.6742222162413915.79816827636687.636076123
#Sta/Elev= 30
       0 1913.81    36.7 1912.66   151.2 1894.81   186.4 1880.95   219.6 1863.04
   266.6 1832.77   284.4 1816.22   333.5  1809.2   423.4 1804.52   475.2 1799.69
   524.1 1801.14   661.7 1798.73   735.1 1801.84  1061.1 1796.34  1172.1 1802.34
  1283.1 1800.12  1318.6  1801.2  1337.5 1797.04 1362.67 1795.15  1389.6 1790.97
  1469.5 1790.97 1482.561795.825  1493.3 1800.01  1584.9 1796.23  1602.7 1798.72
  1620.4 1807.88  1661.1 1837.06  1718.1 1860.65    1758 1883.08  1790.3 1897.97
#Mann= 6 ,-1 , 0
       0      .1       0  241.19     .06       0  344.76     .05       0
 1362.67    .045       0 1482.56      .1       0 1484.04      .1       0
#XS Ineff= 2 , 0
          846.81 1811.48
Permanent Ineff=
       F       F
Bank Sta=1362.67,1482.56
XS Rating Curve= 0 ,0
Exp/Cntr=0.3,0.1

Type RM Length L Ch R = 1 ,93899   ,529.3,523.8,519.7
XS GIS Cut Line= 2
2412745.58594176637977.8047556282414207.65913311637320.853969797
#Sta/Elev= 30
       0  1926.9     7.1 1922.39    23.2 1918.72    66.6 1897.07   207.4 1835.93
   238.1 1826.67   305.7 1823.97   338.9 1801.56   369.2 1801.58   413.5 1797.06
     909 1794.03   963.5 1791.28  1022.7 1791.62  1066.9 1795.04  1113.5 1794.25
  1128.3 1797.67    1159 1789.38 1243.131787.676  1276.9 1783.22  1307.2 1783.35
 1323.081789.321  1356.3 1791.15  1382.6 1797.69  1394.9 1804.78  1408.9 1818.65
  1439.6    1840  1473.6 1858.63  1492.3 1864.59  1540.5 1899.03  1602.9 1913.49
#Mann= 6 ,-1 , 0
       0      .1       0  283.08     .06       0  385.89     .05       0
  899.96      .1       0 1243.13    .045       0 1323.08      .1       0
Bank Sta=1243.13,1323.08
XS Rating Curve= 0 ,0
Exp/Cntr=0.3,0.1

Type RM Length L Ch R = 1 ,93376   ,511.1,508.1,489.2
XS GIS Cut Line= 2
2413338.91119868638435.3330400442414507.14409843637697.238715708
#Sta/Elev= 30
       0  1914.9    47.1 1909.43   116.2 1885.46   132.3 1875.71   153.9    1860
   203.2 1818.99   232.2  1800.1   385.8 1796.71   533.7 1787.31     844 1789.48
   875.1 1797.23   919.4 1797.16   928.1 1796.05  958.521784.954   998.1 1781.69
    1073 1781.81 1094.311785.569  1102.2 1785.81  1121.2 1795.02  1140.1 1794.35
  1163.7  1797.7  1234.7  1836.4  1264.4  1848.9  1277.3 1851.24  1299.2 1860.53
  1316.6 1864.34  1339.8 1874.52  1357.7 1885.97  1371.7  1890.1  1381.9 1898.01
#Mann= 7 ,-1 , 0
       0      .1       0  172.03     .06       0  279.99    .035       0
  387.94    .055       0  585.54     .05       0  958.52    .045       0
 1094.31      .1       0
Bank Sta=958.52,1094.31
XS Rating Curve= 0 ,0
Exp/Cntr=0.5,0.3

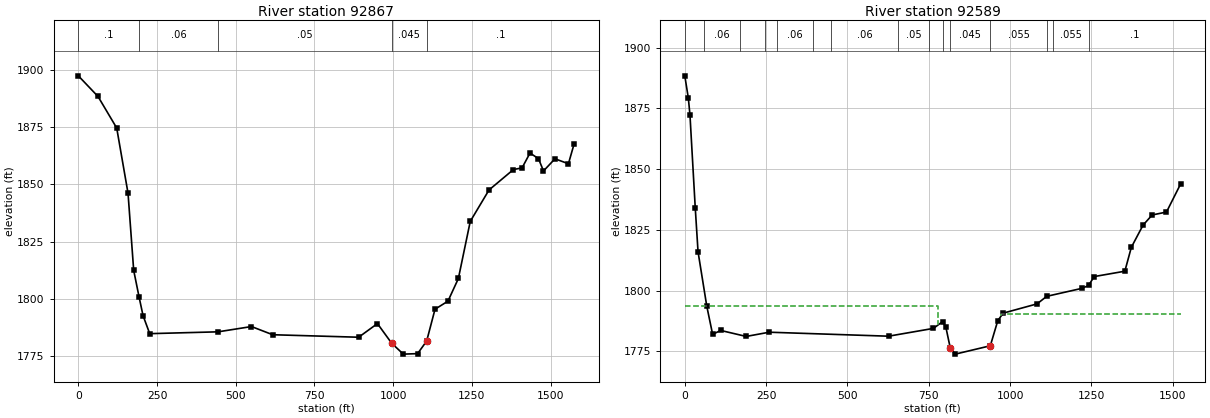
Type RM Length L Ch R = 1 ,92867   ,292.7,278.5,264.9
XS GIS Cut Line= 2
2413711.65716151638967.8370602622414900.28141318637934.919282725
#Sta/Elev= 30
       0 1897.37    62.4 1888.38   121.9  1874.6   157.8 1846.19   175.8 1812.52
   192.8 1800.98   205.5 1792.77   226.7  1784.9   443.9  1785.7   549.9    1788
   617.4 1784.43   890.3 1783.34   949.9 1789.29     995 1780.76    1032 1775.97
  1077.5 1776.18  1106.3 1781.69  1132.8 1795.56  1173.9 1799.08    1207 1808.97
  1244.7 1833.87  1304.3 1847.58  1381.9  1856.5  1409.2  1857.2  1434.5  1863.7
  1461.4 1861.23  1477.3 1855.87  1513.8 1861.18  1556.5 1859.01  1574.7 1867.76
#Mann= 5 ,-1 , 0
       0      .1       0   192.8     .06       0   443.9     .05       0
     995    .045       0  1106.3      .1       0
Bank Sta=995,1106.3
XS Rating Curve= 0 ,0
Exp/Cntr(USF)=0,0
Exp/Cntr=0.3,0.1

Type RM Length L Ch R = 1 ,92589   ,97.9,100.7,97
XS GIS Cut Line= 6
2413957.97229654 639107.083008872414182.01449937638941.425859883
 2414482.6133076638711.8990879652414686.71198076638437.407510966
2414932.66096395638259.0830644672415154.30225295638261.543033302
#Sta/Elev= 30
       0 1888.43    10.9 1879.23    15.9  1872.3    32.1 1834.15    40.7 1816.03
    67.6  1793.6    85.5 1782.02   110.4 1783.63   188.7 1781.16   259.6  1782.9
   626.3 1781.26   764.3 1784.47   792.7 1787.28   802.7 1784.91  815.941776.516
   831.4 1773.88  939.241777.317   962.2 1787.65   978.8 1790.75  1082.9 1794.56
  1112.6 1797.67  1221.3 1800.97  1241.3 1802.13  1258.5  1805.8  1352.8 1808.01
  1372.8 1817.85  1408.8 1826.98  1436.8 1831.16  1480.8 1832.36  1524.3 1843.93
#Mann= 15 ,-1 , 0
       0     .05       0   58.47     .06       0  170.21    .055       0
  245.84     .05       0  281.97     .06       0  394.61    .055       0
  450.97     .06       0  655.17     .05       0  749.88    .035       0
  794.77     .06       0  815.94    .045       0  939.24    .055       0
  1112.8     .06       0 1132.47    .055       0 1243.68      .1       0
#XS Ineff= 2 , 0
          778.76 1793.67     973          1790.4
Permanent Ineff=
       F       F
Bank Sta=815.94,939.24
XS Rating Curve= 0 ,0
Exp/Cntr=0.5,0.3