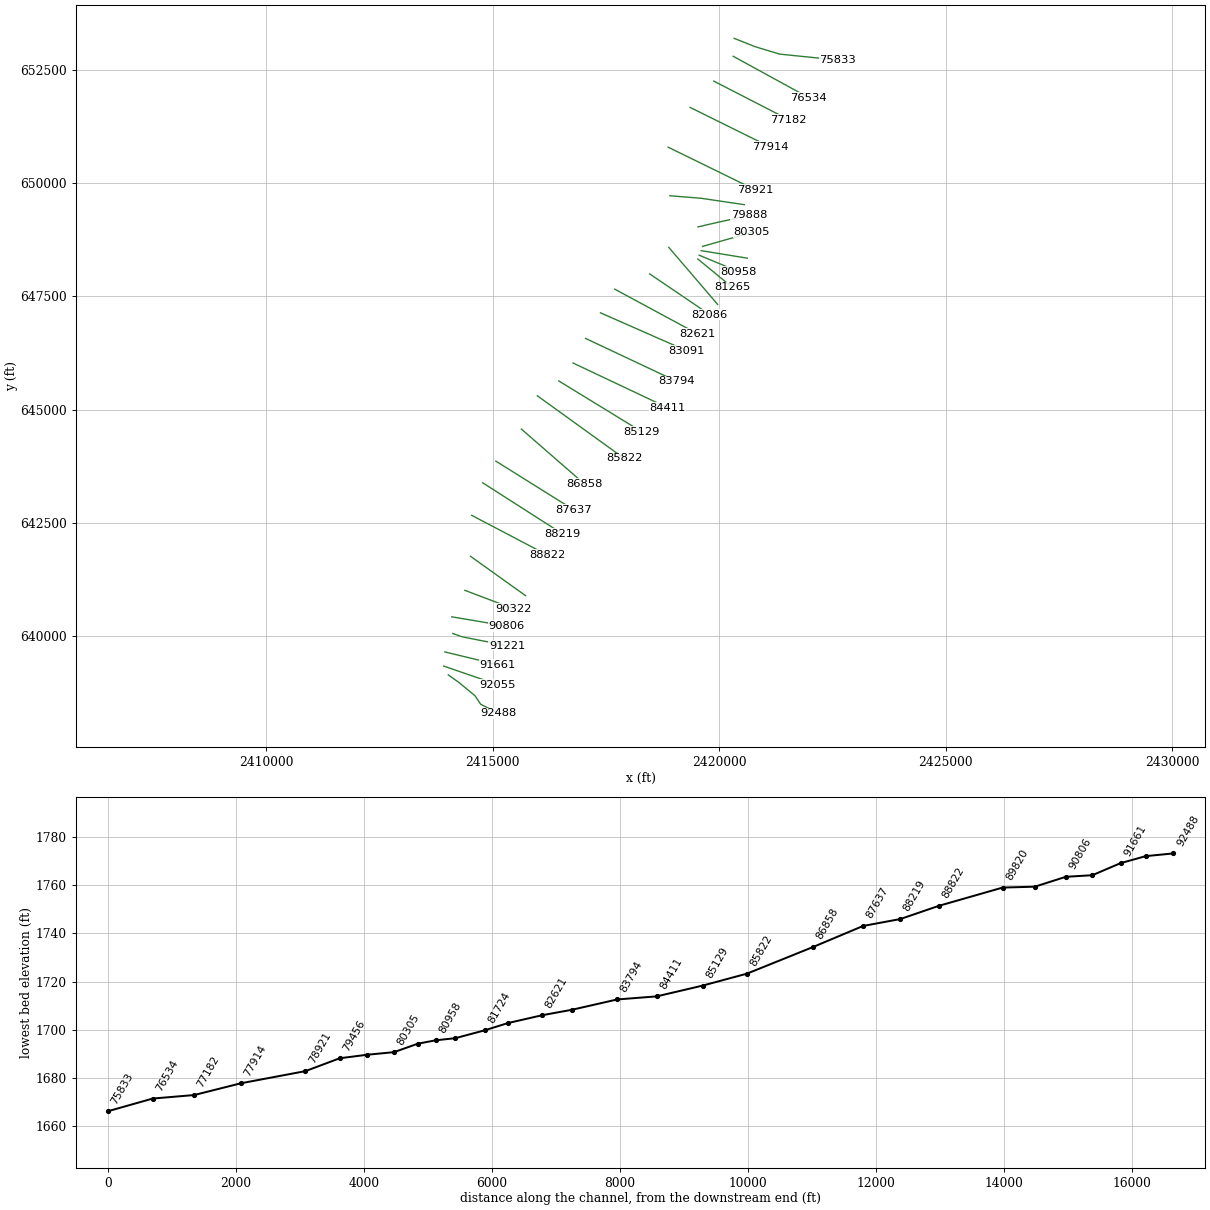
HEC-RAS study NFSBPOTOMC.prj: NFSBPOTOMC

--- NFSBPOTOMC.g01 (geometry) --- (continued)

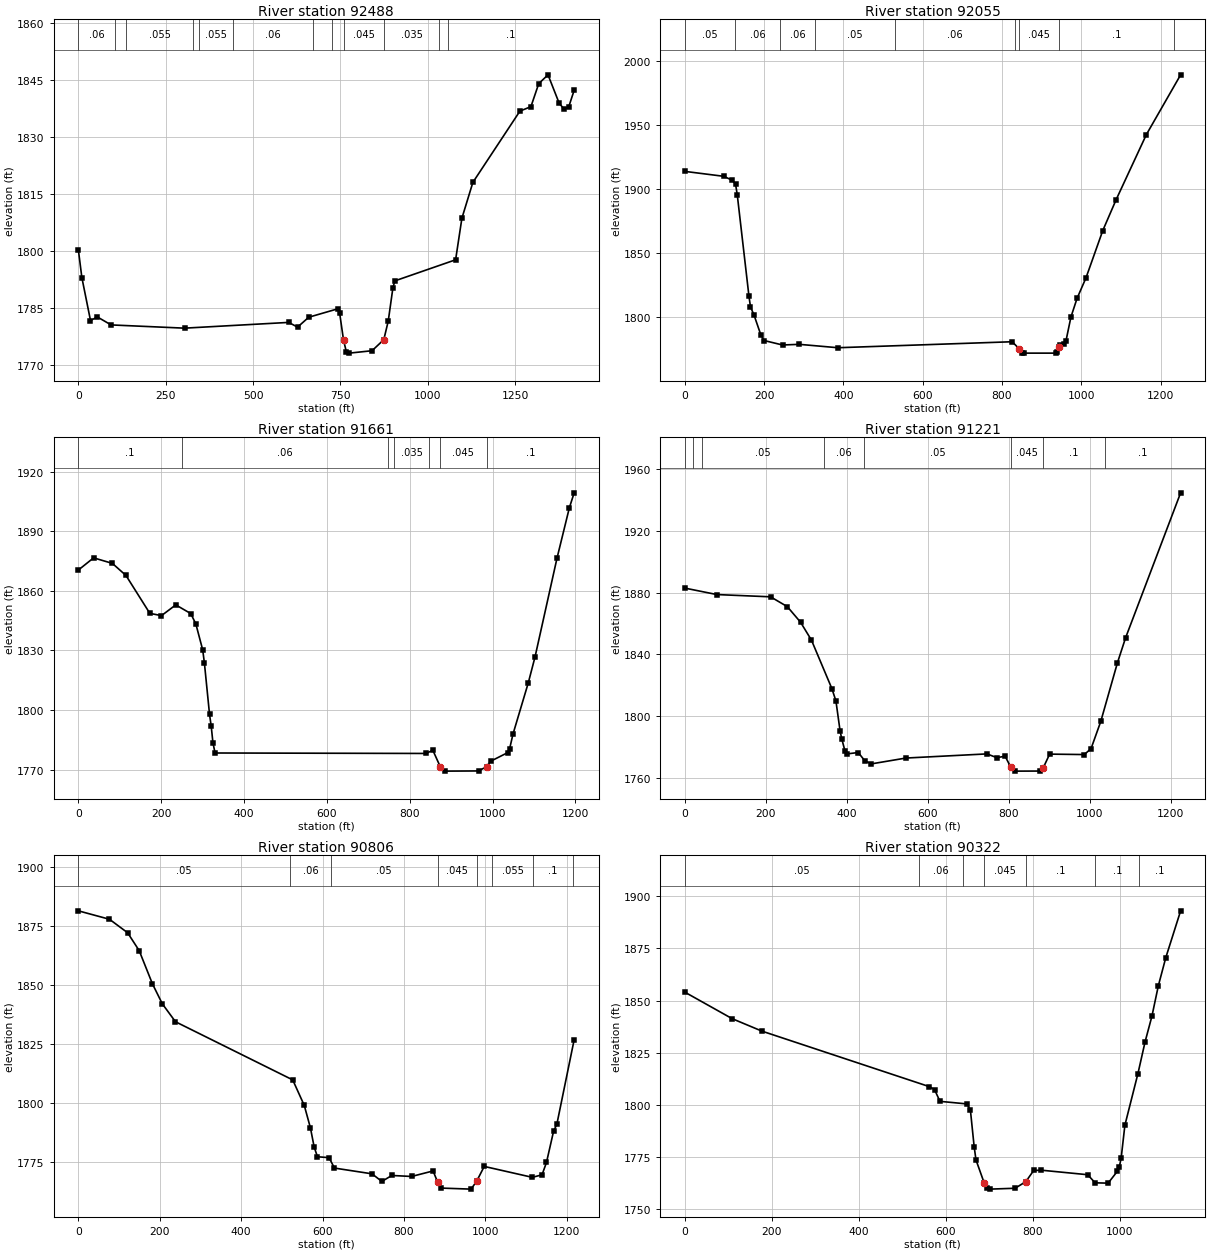
Type RM Length L Ch R = 1 ,92488   ,402.4,432.9,472
XS GIS Cut Line= 5
2414022.50136694 639142.849669622414254.36835727638976.451052293
2414613.34073645638680.1563692992414736.13609451638494.632790208
2415132.96830609638292.449795634
#Sta/Elev= 30
       0 1800.45    10.1  1793.1    34.8 1781.82    54.5 1782.75    93.8 1780.66
   303.8 1779.81     602 1781.32   627.2 1780.08   659.3 1782.68   742.3 1784.89
   747.5  1783.9   758.81776.676   766.8 1773.61   775.1 1773.25   840.4 1773.88
  874.021776.784   886.7 1781.65     900 1790.34   905.6 1792.23  1079.5 1797.77
  1097.5 1808.69  1128.9 1818.11  1263.5 1836.83    1295    1838  1317.4 1844.06
  1343.9 1846.36  1375.8 1838.91  1389.3 1837.41  1402.7 1837.81  1418.7 1842.31
#Mann= 12 ,-1 , 0
       0     .06       0  104.23     .06       0  136.89    .055       0
  327.61     .06       0  345.13    .055       0  442.68     .06       0
   672.8    .055       0  727.18    .035       0   758.8    .045       0
  874.02    .035       0  1032.7    .055       0 1057.01      .1       0
Bank Sta=758.8,874.02
XS Rating Curve= 0 ,0
Exp/Cntr=0.5,0.3

Type RM Length L Ch R = 1 ,92055   ,389.6,394.6,398.8
XS GIS Cut Line= 2
2413921.59704119639336.2859625522415104.43293011638930.038415462
#Sta/Elev= 30
       0 1914.09    98.5 1910.23   119.6 1907.13   127.9 1904.33   132.3 1895.89
   161.9 1816.41   165.7 1808.25   174.6 1801.88   191.5 1786.65     200 1781.97
   246.5 1778.48   288.8 1778.98     386 1776.34   825.9 1781.01  843.091775.598
   851.3 1772.23   855.5 1772.12   935.9 1772.12   940.1 1773.02  942.991776.591
   946.4 1778.66     957 1779.28   961.3  1781.4     974 1800.31   989.4 1814.85
    1012 1830.94  1054.3 1867.84  1087.9  1891.9  1164.3 1942.84  1250.7 1989.51
#Mann= 9 ,-1 , 0
       0     .05       0  126.39     .06       0  241.09     .06       0
  327.93     .05       0  529.47     .06       0  831.78      .1       0
  843.09    .045       0  942.99      .1       0 1234.87      .1       0
Bank Sta=843.09,942.99
XS Rating Curve= 0 ,0
Exp/Cntr=0.3,0.1

Type RM Length L Ch R = 1 ,91661   ,438.8,440.3,443
XS GIS Cut Line= 2
 2413946.9217937639649.2098773722415110.36697337639368.522774711
#Sta/Elev= 30
       0 1870.43    36.9 1876.58    82.1  1873.8     115 1867.71   172.6 1848.63
   200.7 1847.49   235.2  1852.9   271.4 1848.52   283.7 1843.26   300.2 1830.22
   304.3 1823.64   316.7 1797.73   320.8  1791.7   324.9 1783.51     330 1778.32
   839.2 1778.09   855.7 1779.71  873.681771.364   884.5 1769.19   966.4 1769.28
  985.391771.461   995.6 1774.21  1036.7 1778.54  1040.9 1780.35  1049.3 1787.94
  1086.1 1813.66  1102.4 1826.74  1155.4 1876.41  1185.2 1901.77  1196.8 1909.32
#Mann= 7 ,-1 , 0
       0      .1       0  249.69     .06       0  747.71     .05       0
  762.28    .035       0  847.32     .06       0  873.68    .045       0
  985.39      .1       0
Bank Sta=873.68,985.39
XS Rating Curve= 0 ,0
Exp/Cntr=0.3,0.1

Type RM Length L Ch R = 1 ,91221   ,413.8,414.8,416.2
XS GIS Cut Line= 3
2414122.65110102640055.7152979672414336.54207745639981.043859378
2415316.26157469639788.536370382
#Sta/Elev= 30
       0 1882.88    79.2 1878.68   211.9 1877.22   253.3 1870.84   285.9 1860.78
   312.9 1849.14   363.3 1817.76   373.4 1809.68   383.7 1790.15   387.8 1785.12
   395.9 1777.07     400 1775.33   428.5 1776.26   444.8 1770.88   461.2  1768.9
   546.2 1772.67   746.5 1775.36     771 1772.91   791.4 1773.88  805.661766.551
   815.8 1764.19     877 1764.24  885.531766.312   901.4 1775.22     987 1774.93
  1003.7 1778.77  1027.8 1796.48  1068.8 1834.37  1088.9 1850.56    1225 1944.65
#Mann= 8 ,-1 , 0
       0     .05       0   21.41      .1       0   41.89     .05       0
  342.73     .06       0   442.1     .05       0  805.66    .045       0
  885.53      .1       0 1038.33      .1       0
Bank Sta=805.66,885.53
XS Rating Curve= 0 ,0
Exp/Cntr=0.3,0.1

Type RM Length L Ch R = 1 ,90806   ,492.3,483.8,473.6
XS GIS Cut Line= 2
2414099.33159387640424.2791933722415300.56934887640222.330778375
#Sta/Elev= 30
       0 1881.54    76.5 1877.96   121.1 1872.24   149.5 1864.66   181.9 1850.64
   206.3 1842.11   238.7  1834.5   526.7 1809.85   555.1    1799   570.2  1789.5
   579.4 1781.36   587.5 1777.25   615.9 1776.88   629.2 1772.46   721.4 1770.02
   745.7 1766.79   770.1 1769.32   818.7  1768.9   871.5 1771.24  882.621766.534
   891.8 1763.97   964.8 1763.53  978.471766.855   997.2 1773.16  1115.3 1768.53
  1139.2  1769.6  1150.1 1774.85  1167.4 1787.98  1175.7 1791.14  1218.1 1826.89
#Mann= 8 ,-1 , 0
       0     .05       0  520.53     .06       0  619.85     .05       0
  882.62    .045       0  978.47      .1       0 1017.13    .055       0
 1116.44      .1       0 1215.76      .1       0
Bank Sta=882.62,978.47
XS Rating Curve= 0 ,0
Exp/Cntr=0.3,0.1

Type RM Length L Ch R = 1 ,90322   ,510.5,502.1,486.2
XS GIS Cut Line= 2
2414388.93534535641009.2691651282415454.54082569640605.465838879
#Sta/Elev= 30
       0 1854.03   108.9 1841.28   177.3  1835.3   562.3 1808.62     574  1807.2
   586.4 1801.58   648.5 1800.34   656.4 1797.32     665 1779.81   669.2 1773.45
  687.731762.577   694.9 1759.92   701.2 1759.42   759.1 1759.84  783.691763.001
   801.8 1768.37   818.6 1768.53   925.9 1766.34     943 1762.45   972.9 1762.29
   994.3 1768.04   998.6 1770.09  1002.9 1774.45  1011.4 1790.11  1041.4 1814.92
  1057.9 1830.24  1073.5 1842.45  1088.4  1857.2  1105.5 1870.66  1139.5 1893.08
#Mann= 7 ,-1 , 0
       0     .05       0   537.8     .06       0  639.16      .1       0
  687.73    .045       0  783.69      .1       0  943.27      .1       0
 1044.63      .1       0
Bank Sta=687.73,783.69
XS Rating Curve= 0 ,0
Exp/Cntr=0.3,0.1

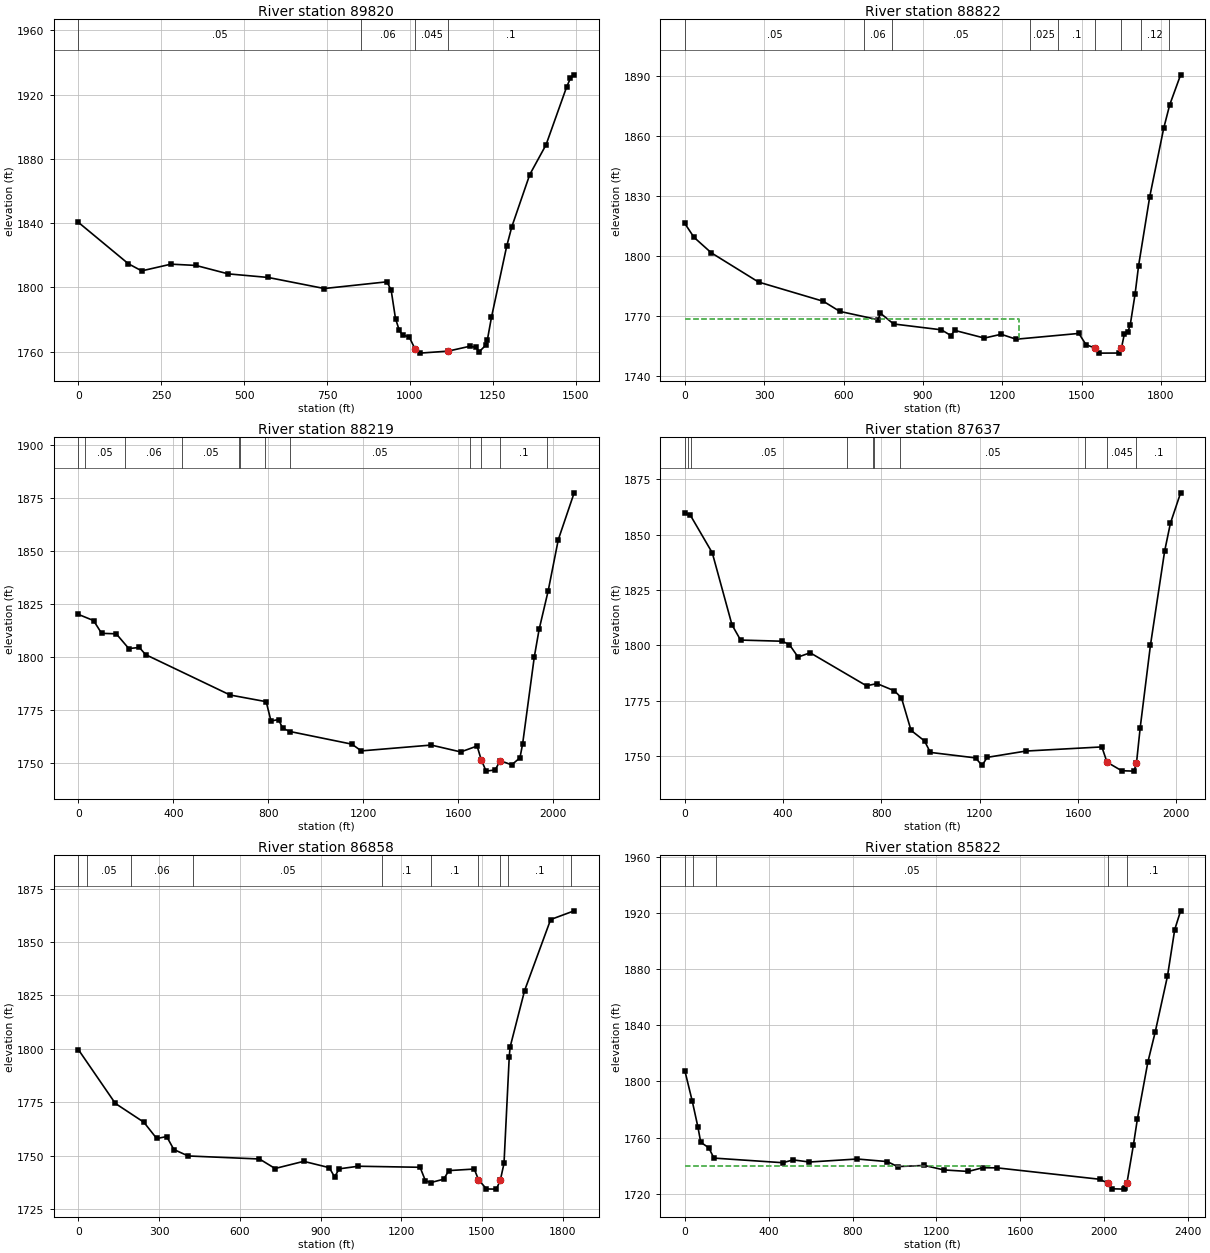
Type RM Length L Ch R = 1 ,89820   ,990.4,997.8,1004.1
XS GIS Cut Line= 2
2414511.32092735641762.1521737872415727.70038435640892.012509882
#Sta/Elev= 30
       0 1840.52     151  1814.7   191.1 1810.28   279.6 1814.46   354.6 1813.66
   451.8 1808.42   572.5 1806.18   741.9 1799.29   930.9 1803.47   943.6 1798.28
   956.7 1780.55   968.1 1773.25     978 1770.24   997.7 1769.27 1015.711761.613
    1030 1759.06 1115.681760.309  1180.3 1763.31  1199.3 1762.66  1209.1 1759.91
  1228.8 1763.97  1233.7 1767.19  1246.2 1781.39  1292.1 1825.64  1307.5 1837.71
  1361.6 1870.21  1410.8 1888.79  1472.7 1924.68  1484.2 1930.17  1495.6 1932.35
#Mann= 4 ,-1 , 0
       0     .05       0  853.89     .06       0 1015.71    .045       0
 1115.68      .1       0
Bank Sta=1015.71,1115.68
XS Rating Curve= 0 ,0
Exp/Cntr=0.3,0.1

Type RM Length L Ch R = 1 ,88822   ,606.6,603.4,599.3
XS GIS Cut Line= 2
 2414540.1253317642665.4403934632416199.26079294641793.774813965
#Sta/Elev= 30
       0 1816.32    34.6 1809.41   100.1 1801.64   278.6 1787.02   523.8 1777.39
   585.8 1772.34   730.4 1768.19   739.5 1771.43   789.2 1766.05   969.9 1763.13
  1006.1 1760.23  1019.6 1762.87  1132.4    1759  1195.8  1760.9  1252.5 1758.43
  1489.5 1761.32  1516.6 1755.67 1550.491754.041  1566.3 1751.47  1641.9 1751.52
 1650.391753.952  1661.2 1760.84  1674.8 1762.14  1683.8 1765.64  1701.9 1780.87
  1715.4 1795.28  1757.4 1829.67  1810.3 1863.97  1832.9 1875.63  1874.2 1890.65
#Mann= 9 ,-1 , 0
       0     .05       0   677.8     .06       0  782.53     .05       0
  1306.2    .025       0 1410.93      .1       0 1550.49    .045       0
 1650.39    .025       0 1725.13     .12       0 1829.86      .1       0
#XS Ineff= 2 , 0
         1261.73 1768.34
Permanent Ineff=
       F       F
Bank Sta=1550.49,1650.39
XS Rating Curve= 0 ,0
Exp/Cntr=0.3,0.1

Type RM Length L Ch R = 1 ,88219   ,577.6,581.6,581.1
XS GIS Cut Line= 2
2414780.23508769643385.5035858752416538.97533661642259.356888041
#Sta/Elev= 30
       0 1820.06    64.2 1817.13      98  1811.1   159.7 1810.87   212.5 1803.91
   257.1 1804.41   283.2 1801.05   639.4 1781.94   791.1  1778.8   811.6 1769.64
   843.1 1770.36   860.8 1766.23   891.2  1764.7  1152.4 1758.71  1191.7 1755.53
  1486.3 1758.29  1610.8 1755.04  1679.6 1757.84 1697.071751.296  1717.6 1745.97
  1755.5 1746.52 1776.931750.948  1825.1 1748.92  1860.1 1752.27  1871.4 1758.89
  1920.6 1800.02  1940.8 1812.94  1978.9 1831.15  2021.6 1855.38  2088.4 1877.51
#Mann= 12 ,-1 , 0
       0     .06       0   26.59     .05       0  195.72     .06       0
  437.42     .05       0     676     .06       0  679.13     .05       0
  784.24     .06       0  892.47     .05       0 1650.12      .1       0
 1697.07    .045       0 1776.93      .1       0 1974.83      .1       0
Bank Sta=1697.07,1776.93
XS Rating Curve= 0 ,0
Exp/Cntr=0.3,0.1

Type RM Length L Ch R = 1 ,87637   ,760.5,779.4,771.6
XS GIS Cut Line= 2
2415072.00648576643863.3343231232416782.10280311642792.826949716
#Sta/Elev= 30
       0 1859.66    22.1 1858.84   111.8 1841.75     192  1809.2     227 1802.33
     397  1801.8     426 1800.21   460.9 1794.66   510.2 1796.58   739.4 1781.66
   781.9 1782.66   852.7 1779.41   881.7 1776.19   920.5 1761.53   975.4 1756.75
     999 1751.56    1183 1749.08  1209.7 1745.66  1230.2 1749.32  1387.9 1752.17
    1697 1754.04  1717.91747.153  1777.6 1743.28  1827.8  1743.1 1837.751746.604
  1853.1 1762.81  1894.6 1799.94  1952.6 1842.61  1975.9  1855.1  2017.5 1868.87
#Mann= 10 ,-1 , 0
       0     .05       0   12.48      .1       0   27.25     .05       0
  659.06     .06       0  766.82    .055       0   769.6     .06       0
  874.59     .05       0 1628.93      .1       0  1717.9    .045       0
 1837.75      .1       0
Bank Sta=1717.9,1837.75
XS Rating Curve= 0 ,0
Exp/Cntr=0.3,0.1

Type RM Length L Ch R = 1 ,86858   ,1027.6,1035.6,1040.9
XS GIS Cut Line= 2
2415635.11592385644571.0048237892417024.66924712643361.011508882
#Sta/Elev= 30
       0 1799.68   137.4 1774.49   243.5 1765.68   291.2 1758.07   328.4 1758.96
   354.9 1752.91   408.1  1749.9   673.1 1748.48   731.1 1744.03   837.5 1747.38
   932.1 1744.44   952.4 1740.12   969.4 1743.87  1040.3 1745.09    1270  1744.6
  1289.8 1738.28  1309.6 1737.44  1357.9 1739.04  1376.8 1743.05  1471.3 1743.78
 1486.821738.829  1516.6 1734.46  1553.4 1734.38  1568.11738.538  1581.8 1746.43
  1601.3 1796.34  1604.5 1800.85  1658.4 1827.31  1755.1 1860.51  1842.5 1864.59
#Mann= 10 ,-1 , 0
       0      .1       0    30.4     .05       0  194.01     .06       0
  427.82     .05       0 1129.26      .1       0 1311.07      .1       0
 1486.82    .045       0  1568.1      .1       0 1596.89      .1       0
  1830.7      .1       0
Bank Sta=1486.82,1568.1
XS Rating Curve= 0 ,0
Exp/Cntr=0.3,0.1

Type RM Length L Ch R = 1 ,85822   ,688.1,692.8,696.5
XS GIS Cut Line= 2
2415987.84061211645305.910834298 2417905.4037061643922.147525713
#Sta/Elev= 30
       0 1807.72    35.8  1785.8    62.8 1767.33    75.9 1756.67   114.5 1752.68
   138.9 1745.38   467.3 1742.09   516.6 1744.09   594.5 1742.58   822.4 1744.73
   965.5 1742.89  1014.8 1739.33    1143 1740.14  1235.6 1736.95  1351.8 1735.87
  1420.1  1738.5  1488.4 1738.44  1978.3 1730.32 2017.191727.561  2035.9 1723.53
  2096.9 1723.28  2101.5 1723.84 2109.061727.986  2139.5 1754.67  2158.8  1773.5
  2208.5 1813.76    2243 1834.85  2302.1 1875.02  2336.5 1908.04  2364.7 1921.45
#Mann= 5 ,-1 , 0
       0      .1       0   37.55     .06       0  148.63     .05       0
 2017.19    .045       0 2109.06      .1       0
#XS Ineff= 2 , 0
         1455.62 1739.57
Permanent Ineff=
       F       F
Bank Sta=2017.19,2109.06
XS Rating Curve= 0 ,0
Exp/Cntr=0.3,0.1

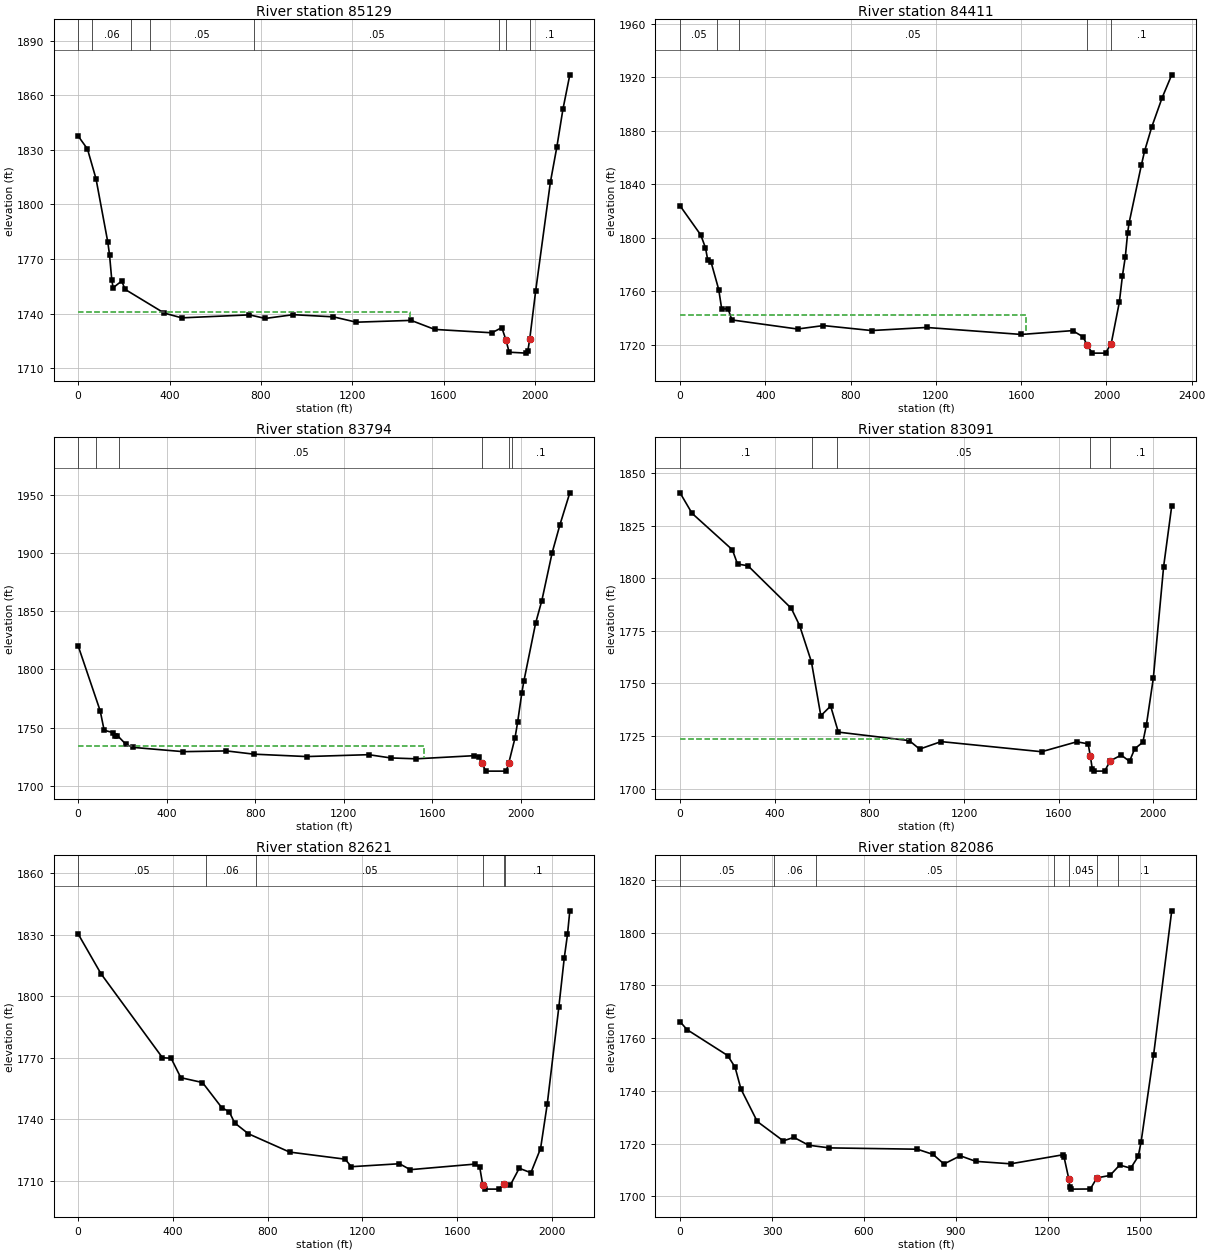
Type RM Length L Ch R = 1 ,85129   ,714.2,718,727.1
XS GIS Cut Line= 2
2416459.98238435645634.7392448782418295.22937003644510.074171379
#Sta/Elev= 30
       0 1837.61    40.8 1830.48    78.3 1814.09   129.9  1779.3   137.5 1772.33
   147.3 1758.49   153.2 1754.22     191 1757.97     205 1753.39   377.1  1740.3
   453.6  1737.7   749.9 1739.34   819.5 1737.38   941.8 1739.44  1117.4 1738.25
  1217.8 1735.32  1457.6 1736.31  1560.8 1731.35  1811.2  1729.5  1854.8 1732.34
 1872.911725.492  1886.8 1718.83  1962.4 1718.32  1968.9 1719.74 1976.741725.884
  2003.1 1752.64  2067.4 1812.25  2095.6 1831.52  2122.4 1852.38  2152.4 1871.21
#Mann= 8 ,-1 , 0
       0     .05       0   61.16     .06       0   233.5     .05       0
  314.24     .05       0  770.19     .05       0 1843.57      .1       0
 1872.91    .045       0 1976.74      .1       0
#XS Ineff= 2 , 0
         1454.21  1740.7
Permanent Ineff=
       F       F
Bank Sta=1872.91,1976.74
XS Rating Curve= 0 ,0
Exp/Cntr=0.3,0.1

Type RM Length L Ch R = 1 ,84411   ,619.1,617.1,617.4
XS GIS Cut Line= 2
2416774.78457627646030.4730334582418859.54221776645044.394296959
#Sta/Elev= 30
       0 1823.99    97.3 1802.14   119.4 1792.52     130 1783.41     146 1781.63
   181.4  1761.4   195.5 1746.79     225 1747.02   243.3 1738.65     551 1731.86
   672.5 1734.44   898.2 1730.72  1156.2 1733.02  1600.8  1727.8  1841.1 1730.66
    1890 1726.05 1910.511719.576  1933.6 1713.84  1995.6 1713.84 2022.421720.999
  2060.4  1751.8  2075.2 1771.86  2088.5 1785.77  2099.5 1803.95  2106.2 1811.16
  2163.7 1854.31  2178.7 1864.74  2212.4 1882.86  2261.1 1904.69  2306.2 1921.87
#Mann= 5 ,-1 , 0
       0     .05       0  174.11     .06       0  277.48     .05       0
 1910.51    .045       0 2022.42      .1       0
#XS Ineff= 2 , 0
          1623.8 1742.09
Permanent Ineff=
       F       F
Bank Sta=1910.51,2022.42
XS Rating Curve= 0 ,0
Exp/Cntr=0.3,0.1

Type RM Length L Ch R = 1 ,83794   ,699.9,703.3,705
XS GIS Cut Line= 2
2417052.48776102646573.1845464562419062.84594503645624.966954708
#Sta/Elev= 30
       0 1820.26    99.8 1764.33   117.6 1747.66   157.3 1745.72   168.7 1742.51
   177.7 1743.12   216.8 1735.45   249.8 1732.93   475.7 1729.28   670.6 1729.93
   794.1 1727.14    1033 1725.08  1313.7 1726.69  1412.8  1723.9  1528.3 1723.14
  1791.5 1725.85  1811.3 1725.09 1826.981719.212  1842.3 1712.56  1935.2 1712.56
 1946.921719.612    1975 1741.03  1986.8 1754.51  2005.9 1779.82  2014.8 1789.59
  2068.2 1839.68  2096.4 1859.14    2143 1900.24  2178.4 1924.43  2222.8 1951.68
#Mann= 6 ,-1 , 0
       0      .1       0   82.55     .06       0  185.89     .05       0
 1826.98    .045       0 1946.92      .1       0 1960.62      .1       0
#XS Ineff= 2 , 0
         1563.03  1734.3
Permanent Ineff=
       F       F
Bank Sta=1826.98,1946.92
XS Rating Curve= 0 ,0
Exp/Cntr=0.3,0.1

Type RM Length L Ch R = 1 ,83091   ,472.5,469.8,466
XS GIS Cut Line= 2
2417380.30895576647138.6611057972419281.96492934 646301.28712438
#Sta/Elev= 30
       0 1840.65    50.7 1830.91   221.2 1813.56     243 1806.77   286.9 1805.98
   470.3 1785.69   505.3 1777.54   555.3 1760.25     595 1734.64   636.4 1739.25
     669 1726.85   968.6 1722.82  1012.6 1718.78  1103.2 1722.34    1528 1717.53
  1676.9 1722.25  1724.7 1721.26 1734.211715.263  1742.2 1709.34  1750.9  1708.3
  1794.6 1708.33 1818.131713.207  1864.5 1715.92  1899.5 1712.97  1921.4  1718.9
  1955.9 1722.06    1971 1730.39    2000 1752.37  2043.7  1805.6  2077.9 1834.38
#Mann= 5 ,-1 , 0
       0      .1       0  559.42     .06       0  662.02     .05       0
 1734.21    .045       0 1818.13      .1       0
#XS Ineff= 2 , 0
          962.41 1723.72
Permanent Ineff=
       F       F
Bank Sta=1734.21,1818.13
XS Rating Curve= 0 ,0
Exp/Cntr=0.3,0.1

Type RM Length L Ch R = 1 ,82621   ,539.6,535,530.4
XS GIS Cut Line= 2
 2417697.4182297647660.3077002912419523.34994528646674.131194964
#Sta/Elev= 30
       0 1830.46    96.5 1811.04   356.1 1770.07   392.5 1769.84   433.4 1760.35
   524.9 1757.99   606.1 1745.77     638 1743.68   660.7  1738.3   718.4 1733.02
   892.5 1724.08  1126.7 1720.62  1153.2 1716.95  1356.3 1718.39  1401.7  1715.5
  1674.5 1718.21  1694.9  1716.8 1707.361708.251  1715.4 1706.03  1774.5 1706.01
 1799.331708.494  1823.3 1707.79  1861.7  1716.2  1910.9 1713.99  1951.8 1725.82
  1979.8 1747.35  2029.1 1795.01  2051.8 1818.77  2065.4 1830.21  2075.2 1841.72
#Mann= 6 ,-1 , 0
       0     .05       0  540.51     .06       0   750.8     .05       0
 1707.36    .045       0 1799.33     .05       0 1802.23      .1       0
Bank Sta=1707.36,1799.33
XS Rating Curve= 0 ,0
Exp/Cntr=0.3,0.1

Type RM Length L Ch R = 1 ,82086   ,373.4,361.7,348.3
XS GIS Cut Line= 2
2418466.30612761647998.271263212 2419793.4297857647097.789140299
#Sta/Elev= 30
       0 1766.25    22.9 1763.23   155.2 1753.42   179.4 1749.02   198.7  1740.7
   251.9  1728.4   336.8 1721.05   371.4 1722.38   419.2 1719.41   486.6 1718.39
   773.9 1717.89   825.3 1715.91   860.9 1712.28   914.1 1715.39   964.6 1713.28
  1078.5 1712.35  1247.7 1715.75  1252.6 1714.92 1267.831706.737  1271.8 1703.44
  1276.7 1702.75  1338.2  1702.8 1359.821707.018  1402.4 1707.94    1434 1711.88
    1470 1710.69  1494.5 1715.19  1503.9 1720.66  1544.8  1753.8  1603.8 1808.29
#Mann= 7 ,-1 , 0
       0     .05       0   306.8     .06       0   442.9     .05       0
 1218.86      .1       0 1267.83    .045       0 1359.82      .1       0
 1428.74      .1       0
Bank Sta=1267.83,1359.82
XS Rating Curve= 0 ,0
Exp/Cntr=0.3,0.1

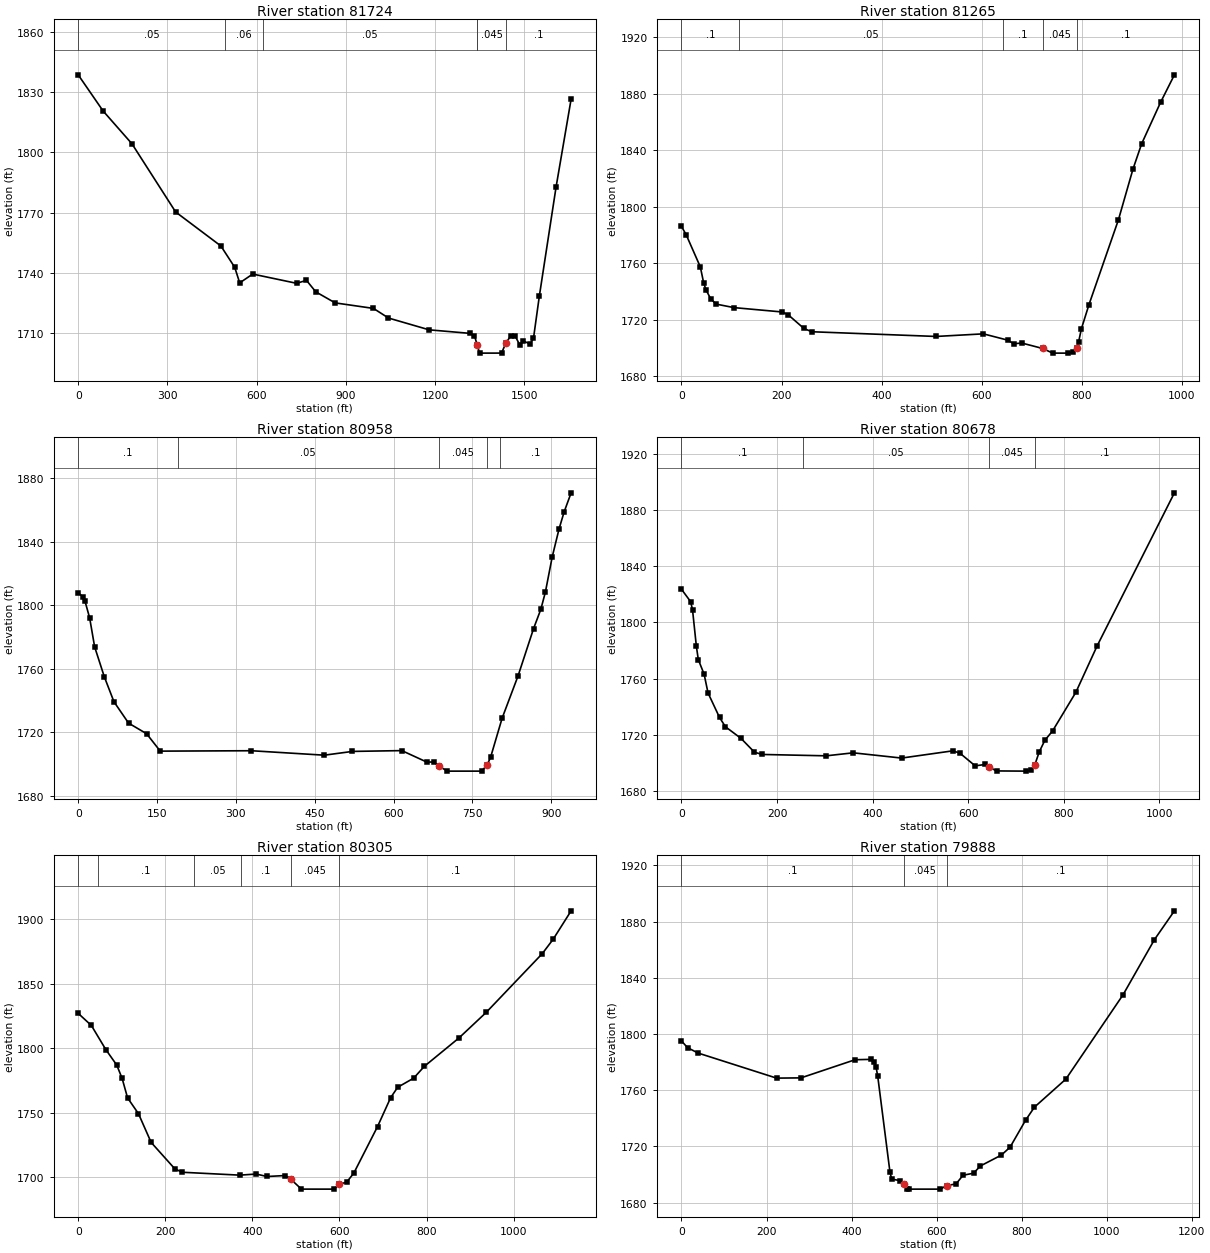
Type RM Length L Ch R = 1 ,81724   ,452.7,459.5,465.7
XS GIS Cut Line= 2
2418889.16945511648583.2622192062419966.85890079647324.561652631
#Sta/Elev= 30
       0 1838.79    83.7 1820.74   180.8 1804.32   327.6 1770.27   479.7 1753.28
   526.2 1742.62   542.9 1734.85   586.7 1739.25   734.3 1734.63   767.3 1736.12
   798.6 1730.38   863.8 1724.85   992.6 1722.09  1043.1 1717.28    1180 1711.38
  1317.7 1709.62  1331.9 1708.55 1341.59 1703.65  1349.3 1699.75  1423.1 1699.77
 1437.421704.711  1453.9 1708.34  1469.7 1708.08  1484.6 1703.76    1496  1705.8
  1519.1 1704.36  1530.5 1707.17  1550.3 1728.39  1606.6 1782.91    1657 1826.67
#Mann= 6 ,-1 , 0
       0     .05       0  492.08     .06       0  622.15     .05       0
 1339.63      .1       0 1341.59    .045       0 1437.42      .1       0
Bank Sta=1341.59,1437.42
XS Rating Curve= 0 ,0
Exp/Cntr=0.3,0.1

Type RM Length L Ch R = 1 ,81265   ,298.2,307.1,317.9
XS GIS Cut Line= 2
2419529.62946028648327.1026265472420290.65090412647701.341738954
#Sta/Elev= 30
       0 1786.07     9.5  1780.1    37.7 1757.41    44.4 1746.06    49.3 1740.95
    58.4 1734.95    69.1 1731.14     105 1728.65   201.9 1725.55   213.8 1723.43
   244.8 1713.89   260.4 1711.59   508.9 1708.26   603.4  1710.1   651.7 1705.69
   664.3 1703.09   680.1 1703.61  721.991699.757     742 1696.48   773.1 1696.47
   782.5 1697.11   789.8 1700.18   793.8 1704.46   799.5 1713.83   814.5 1730.75
   873.4 1790.75   902.5 1826.63   919.8  1844.5   957.6 1873.78   985.3 1893.25
#Mann= 5 ,-1 , 0
       0      .1       0   115.5     .05       0  642.11      .1       0
  721.99    .045       0   789.8      .1       0
Bank Sta=721.99,789.8
XS Rating Curve= 0 ,0
Exp/Cntr=0.3,0.1

Type RM Length L Ch R = 1 ,80958   ,267.7,280.1,288.8
XS GIS Cut Line= 2
2419558.64482218648411.7776540522420423.90227804648050.736381382
#Sta/Elev= 30
       0  1807.7     8.8 1805.37    13.1 1802.31    21.8 1791.98    31.3 1773.76
    49.7 1754.93      68 1739.26    95.8  1725.8   130.1 1719.12   156.1 1708.17
   329.5 1708.42   468.2 1705.62   521.7 1707.99   615.6  1708.5   663.2 1701.26
   676.3 1701.34  686.211698.683   702.3 1695.59   767.3 1695.59  777.981699.497
   784.6 1704.51   806.3 1728.83   836.6 1755.45   866.2 1785.28     880  1797.4
   888.6 1808.15   901.6 1830.32   914.6  1847.9   924.3 1858.66   937.6 1870.66
#Mann= 5 ,-1 , 0
       0      .1       0  189.21     .05       0  686.21    .045       0
  777.98     .05       0  801.89      .1       0
Bank Sta=686.21,777.98
XS Rating Curve= 0 ,0
Exp/Cntr=0.3,0.1

Type RM Length L Ch R = 1 ,80678   ,360.5,372.8,399.4
XS GIS Cut Line= 2
 2419603.9121201648511.4729927182420622.27425662 648345.62457113
#Sta/Elev= 30
       0 1823.57    19.1 1814.78    23.1 1809.06    31.2 1782.89    35.3 1773.44
    47.4 1763.13    55.6 1749.78    79.6 1732.39      92 1725.75   124.5  1717.5
   152.8 1707.63     169 1706.04   302.9 1705.07   359.5  1707.2   460.8 1703.47
   567.6  1708.6   582.4 1707.07   614.8 1697.93   635.1  1698.9  643.861697.059
   659.4 1694.32   720.9 1694.18   732.4 1694.98  739.841698.854   748.8 1707.83
   760.7 1716.17   776.7 1722.73   825.5 1750.25   870.1 1783.33  1031.8 1892.17
#Mann= 4 ,-1 , 0
       0      .1       0  254.62     .05       0  643.86    .045       0
  739.84      .1       0
Bank Sta=643.86,739.84
XS Rating Curve= 0 ,0
Exp/Cntr=0.3,0.1

Type RM Length L Ch R = 1 ,80305   ,421.9,417.1,414.1
XS GIS Cut Line= 2
2419633.64106327648605.7086966342420722.45712709648914.983996704
#Sta/Elev= 30
       0 1826.91    30.3  1817.5    63.5 1798.79    88.5 1786.85   100.9 1776.47
   113.4 1761.39   138.4 1749.14   167.5 1726.88   221.5 1706.54   238.2 1703.75
     371  1701.5   408.7 1702.35   433.6 1700.45   475.2 1701.19  487.951698.409
   512.6 1690.67   587.5 1690.66  599.941694.477   616.6 1696.09     633 1703.14
   687.3 1739.09   717.5 1761.57   733.7 1769.62   770.4 1776.69   794.8 1785.81
   874.4 1807.84   936.8 1827.61  1065.7  1873.2  1090.6 1884.31  1131.9 1906.37
#Mann= 6 ,-1 , 0
       0      .1       0   46.06      .1       0  265.35     .05       0
  374.99      .1       0  487.95    .045       0  599.94      .1       0
Bank Sta=487.95,599.94
XS Rating Curve= 0 ,0
Exp/Cntr=0.3,0.1

Type RM Length L Ch R = 1 ,79888   ,449.7,431.9,411.9
XS GIS Cut Line= 3
2419532.92669776649036.3977958712419968.82346377649137.196150705
2420664.32666594649289.066581875
#Sta/Elev= 30
       0 1795.09    14.2  1790.3    38.8 1786.48   223.6 1768.61     281 1768.78
   408.3  1781.7   445.3 1781.96   453.5 1779.87   457.6 1776.62   461.6 1769.82
   490.3 1701.76   494.4 1696.72   514.9 1695.59  523.391693.534   531.3 1689.77
   535.3 1689.59     609 1689.59  623.371692.057   645.9 1693.32   662.1 1699.46
   686.8 1700.92   703.2 1706.11   752.3 1713.82   772.8 1719.44   809.1 1738.54
   830.1 1747.94   904.1 1767.93  1038.5 1827.93  1112.4 1867.23  1159.3 1887.69
#Mann= 3 ,-1 , 0
       0      .1       0  523.39    .045       0  623.37      .1       0
Bank Sta=523.39,623.37
XS Rating Curve= 0 ,0
Exp/Cntr=0.3,0.1

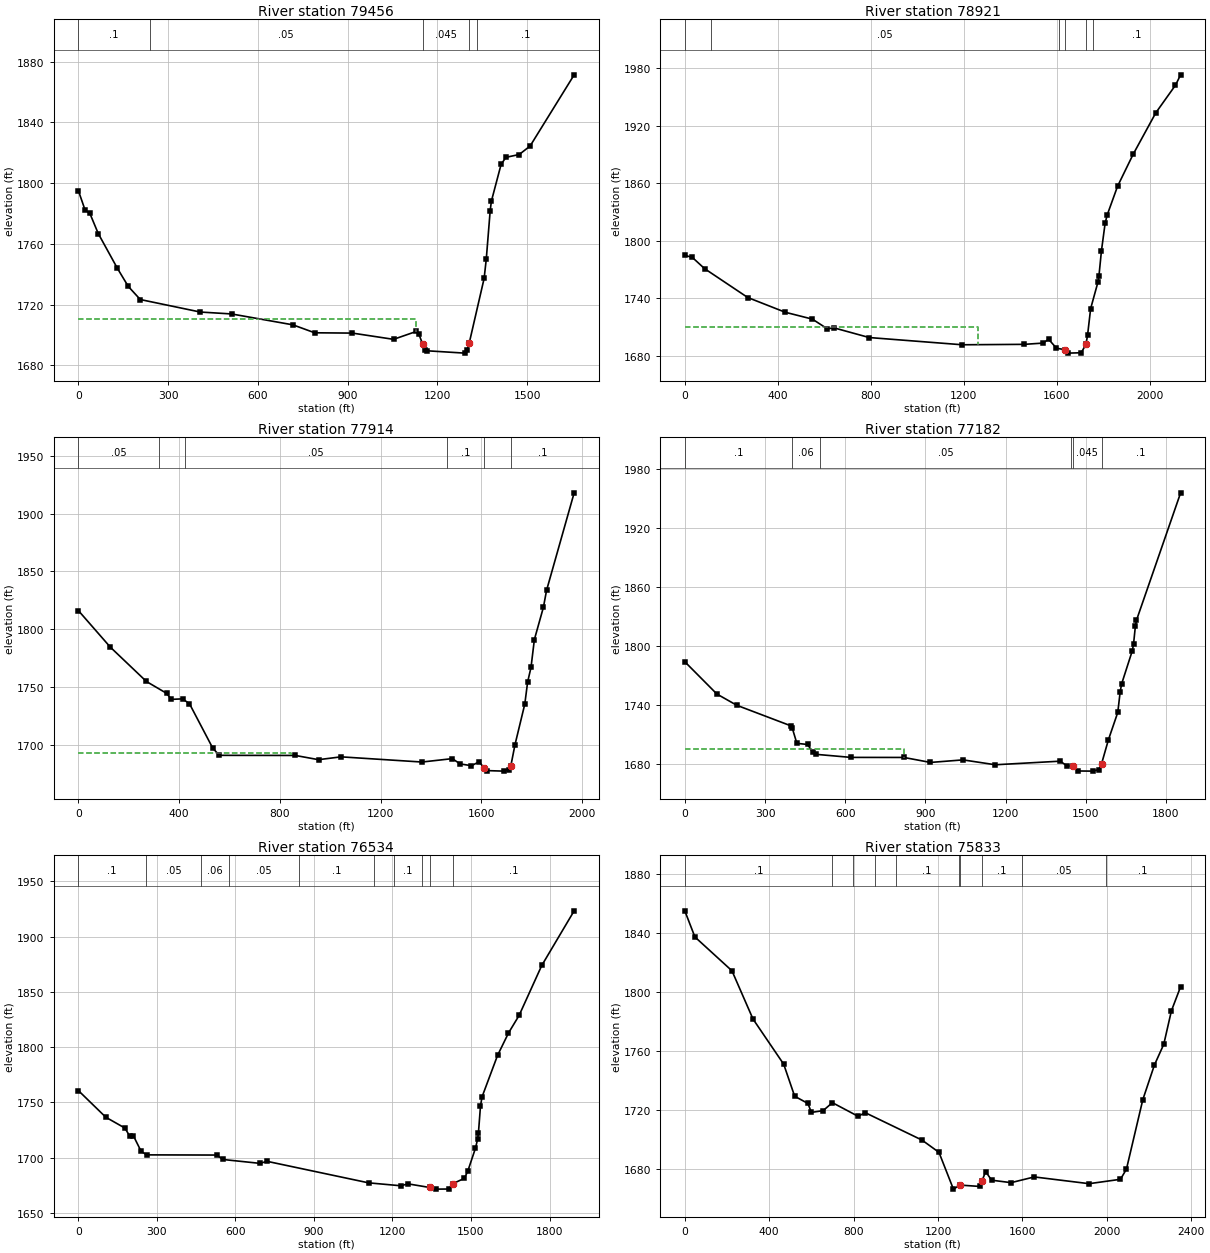
Type RM Length L Ch R = 1 ,79456   ,560.9,534.6,510
XS GIS Cut Line= 3
2418912.40103593649724.3288347132419606.06270635649667.824354544
2420556.31146201649526.918468371
#Sta/Elev= 30
       0  1795.2    22.4  1782.4    38.5 1780.14    66.5 1766.88   130.8 1743.86
   166.9 1732.03     207 1723.41   407.3 1715.18   511.9 1713.92   716.9 1706.75
   789.7 1701.51   915.7 1701.31  1053.1  1697.2  1129.3 1702.41  1137.4  1700.8
 1150.371694.077  1157.6  1690.5  1165.9 1689.65  1291.1 1688.12  1298.6 1689.87
 1305.821694.583  1355.8 1737.32    1363 1750.08    1376 1781.86    1380 1788.14
  1412.4 1812.35  1428.6 1817.04    1473 1818.91  1509.4 1824.49  1656.6 1871.38
#Mann= 5 ,-1 , 0
       0      .1       0  238.23     .05       0 1150.37    .045       0
 1305.82    .055       0 1332.22      .1       0
#XS Ineff= 2 , 0
         1127.79 1710.58
Permanent Ineff=
       F       F
Bank Sta=1150.37,1305.82
XS Rating Curve= 0 ,0
Exp/Cntr=0.3,0.1

Type RM Length L Ch R = 1 ,78921   ,1006.4,1007.4,1005.8
XS GIS Cut Line= 2
 2418874.2387107650796.6921755372420790.54590169649858.846938372
#Sta/Elev= 30
       0 1784.66    31.7 1782.74    85.2 1770.86   270.8 1740.78   432.5 1725.38
   548.9 1718.24   613.8 1708.07   641.1 1709.19   793.3 1699.04  1194.1 1691.49
  1461.3 1691.94  1541.4 1693.25  1565.5 1697.23  1599.3 1687.91 1634.08 1686.43
  1648.3 1682.78  1705.7 1683.17 1725.971691.803    1733 1701.34  1746.3  1729.2
  1777.8 1756.88  1781.9 1762.95  1792.7 1789.25  1808.6 1818.19  1817.5  1826.8
  1862.1 1856.76  1928.9 1889.97  2026.8 1933.41  2111.4 1962.19  2133.5 1972.98
#Mann= 6 ,-1 , 0
       0     .06       0  111.51     .05       0 1608.46      .1       0
 1634.08    .045       0 1725.97      .1       0 1756.52      .1       0
#XS Ineff= 2 , 0
         1263.43  1709.8
Permanent Ineff=
       F       F
Bank Sta=1634.08,1725.97
XS Rating Curve= 0 ,0
Exp/Cntr=0.3,0.1

Type RM Length L Ch R = 1 ,77914   ,732.9,732.1,731.2
XS GIS Cut Line= 2
2419360.08682036651674.3869424612421124.29064101650801.794527546
#Sta/Elev= 30
       0  1816.3     127 1784.71   270.3 1755.08   350.7 1744.82   368.9 1739.66
   413.5 1740.08     441 1735.96     534 1697.43   559.9 1691.36   861.5 1691.26
   953.5 1687.62  1042.7 1690.06    1364 1685.59  1484.5 1688.51  1515.4 1683.99
  1560.4 1682.41  1591.6 1685.86  1608.91680.829  1622.8 1678.19  1688.6 1677.74
  1709.5 1679.08 1716.691682.133  1733.3 1700.54  1772.2 1735.53  1783.5 1754.66
  1796.9  1767.2  1810.3 1791.27    1846 1818.98  1858.7 1833.74  1968.2 1917.85
#Mann= 6 ,-1 , 0
       0     .05       0  320.49     .06       0   424.4     .05       0
 1463.54      .1       0  1608.9    .045       0 1716.69      .1       0
#XS Ineff= 2 , 0
          845.02 1693.19
Permanent Ineff=
       F       F
Bank Sta=1608.9,1716.69
XS Rating Curve= 0 ,0
Exp/Cntr=0.3,0.1

Type RM Length L Ch R = 1 ,77182   ,649.1,647.9,646.3
XS GIS Cut Line= 2
2419881.97554037652255.7709502882421531.19894794651407.362870216
#Sta/Elev= 30
       0 1784.24     120 1751.36   194.3 1739.91   396.3 1719.02   402.2 1716.47
   419.2 1701.13   459.7 1699.97   477.7 1692.19   491.3 1689.93   621.6 1686.82
   819.5 1686.77     919 1681.69  1040.8 1684.29  1161.4 1679.32  1404.3 1682.98
  1431.3 1677.84 1450.951678.027  1471.5 1672.99  1527.9 1672.84  1548.3 1674.49
 1558.871680.232  1584.6 1704.77  1619.6 1732.64  1628.3 1752.99  1633.7  1761.4
  1674.2 1795.66  1678.7 1802.59  1685.4 1820.31  1689.5 1826.43  1854.7 1956.23
#Mann= 6 ,-1 , 0
       0      .1       0   400.4     .06       0  504.84     .05       0
 1444.76      .1       0 1450.95    .045       0 1558.87      .1       0
#XS Ineff= 2 , 0
          821.24 1695.57
Permanent Ineff=
       F       F
Bank Sta=1450.95,1558.87
XS Rating Curve= 0 ,0
Exp/Cntr=0.3,0.1

Type RM Length L Ch R = 1 ,76534   ,681.5,700.9,717.1
XS GIS Cut Line= 2
2420310.63839695652804.3968215442421971.28665045651893.668328047
#Sta/Elev= 30
       0 1760.66     105 1736.47   177.8 1726.69   195.6 1719.69   210.4 1719.63
   239.8 1705.65     261  1702.4   529.3 1702.23   552.1 1698.22   693.5 1694.72
   720.9 1696.55  1108.7 1677.07  1231.9 1674.42  1259.2 1676.16 1342.571672.854
  1365.3 1671.38  1415.4 1671.47 1430.481676.316  1474.3 1681.12  1487.3 1687.42
  1517.1 1708.51  1525.4 1716.85  1528.4 1722.41  1536.2 1746.67  1542.1 1754.88
  1601.4 1792.48  1643.1 1812.72  1683.6 1828.62  1770.2 1873.87    1894 1923.37
#Mann= 10 ,-1 , 0
       0      .1       0  258.98     .05       0  469.74     .06       0
  575.12     .05       0  842.23      .1       0 1128.65    .025       0
 1207.41      .1       0 1312.79     .05       0 1342.57    .045       0
 1430.48      .1       0
Bank Sta=1342.57,1430.48
XS Rating Curve= 0 ,0
Exp/Cntr=0.3,0.1

Type RM Length L Ch R = 1 ,75833   ,730.5,735.6,740.4
XS GIS Cut Line= 4
 2420330.2810742653200.5725383762420796.84313318653015.390165955
2421335.97132003652852.2143112122422614.19907853652721.812669128
#Sta/Elev= 30
       0 1855.25    47.9 1837.49   223.5  1814.5   323.3  1781.7   468.8    1751
   520.7 1729.24   583.4 1724.35   600.1 1718.25   655.6 1719.46   699.6 1724.87
   821.5  1715.6     855 1718.08  1124.3 1699.44  1204.7 1691.11  1273.1 1666.11
 1304.671668.849  1397.7 1667.94 1408.411671.588  1425.9 1678.07    1454 1672.19
  1546.5 1670.51  1656.4  1674.4  1916.4 1669.81    2065 1672.79  2093.3 1679.69
  2170.8 1726.87    2226  1750.5  2270.2 1764.56  2306.4 1787.29  2350.1 1803.72
#Mann= 10 ,-1 , 0
       0      .1       0  698.89      .1       0  799.09     .06       0
   899.3     .05       0   999.5      .1       0 1298.44     .05       0
 1304.67    .045       0 1408.41      .1       0 1596.91     .05       0
 1994.87      .1       0
Bank Sta=1304.67,1408.41
XS Rating Curve= 0 ,0
Exp/Cntr=0.3,0.1