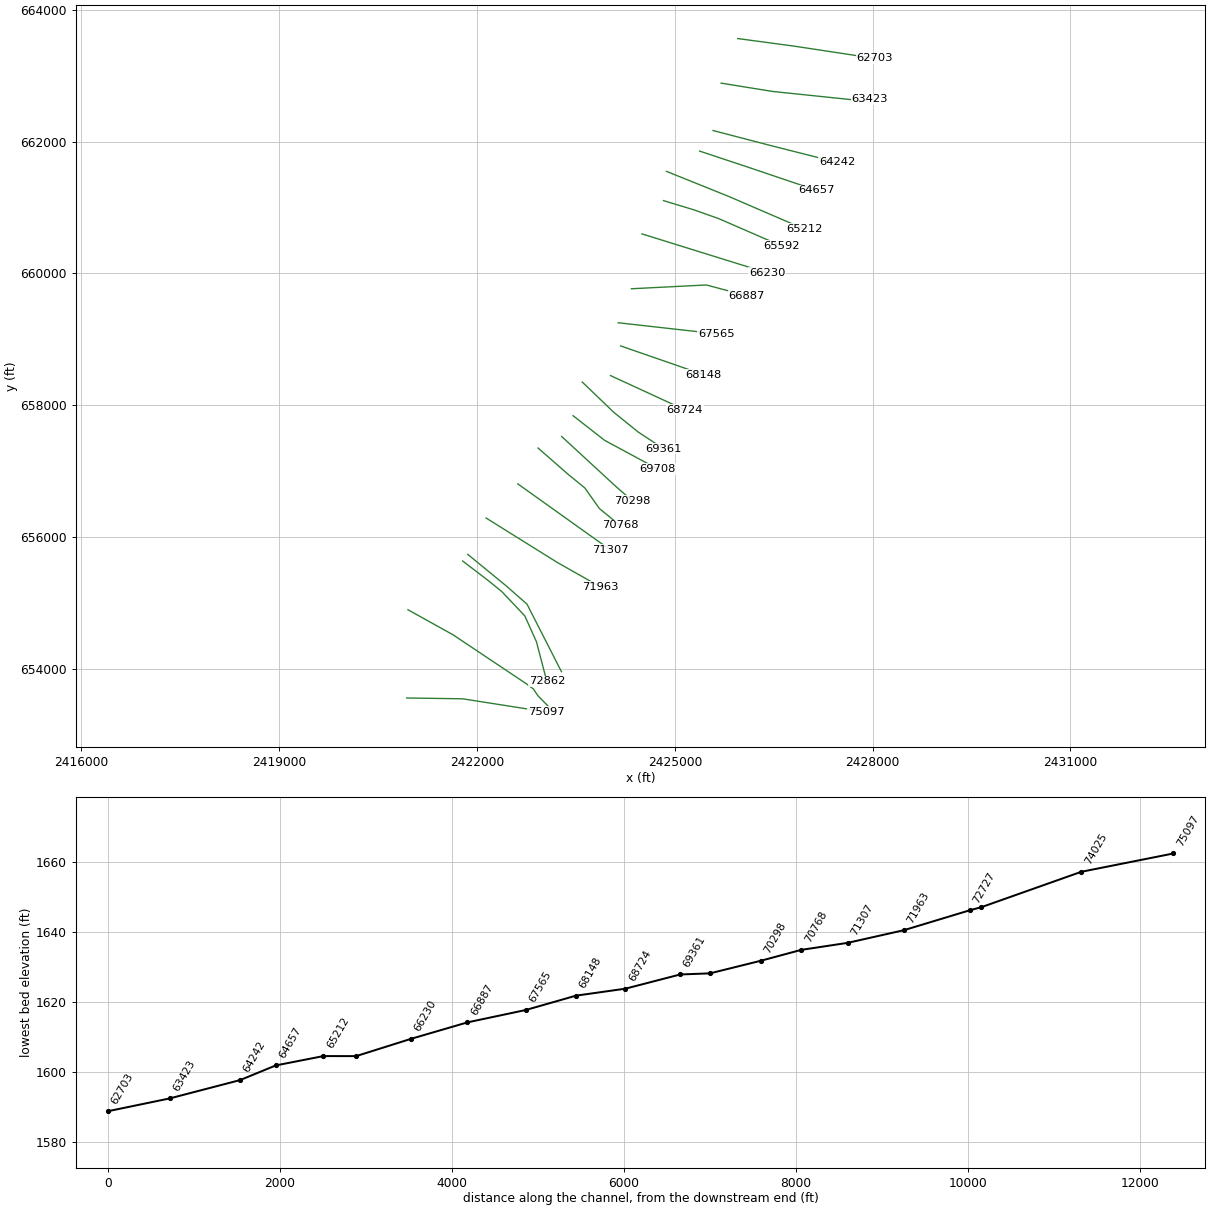
HEC-RAS study NFSBPOTOMC.prj: NFSBPOTOMC

--- NFSBPOTOMC.g01 (geometry) --- (continued)

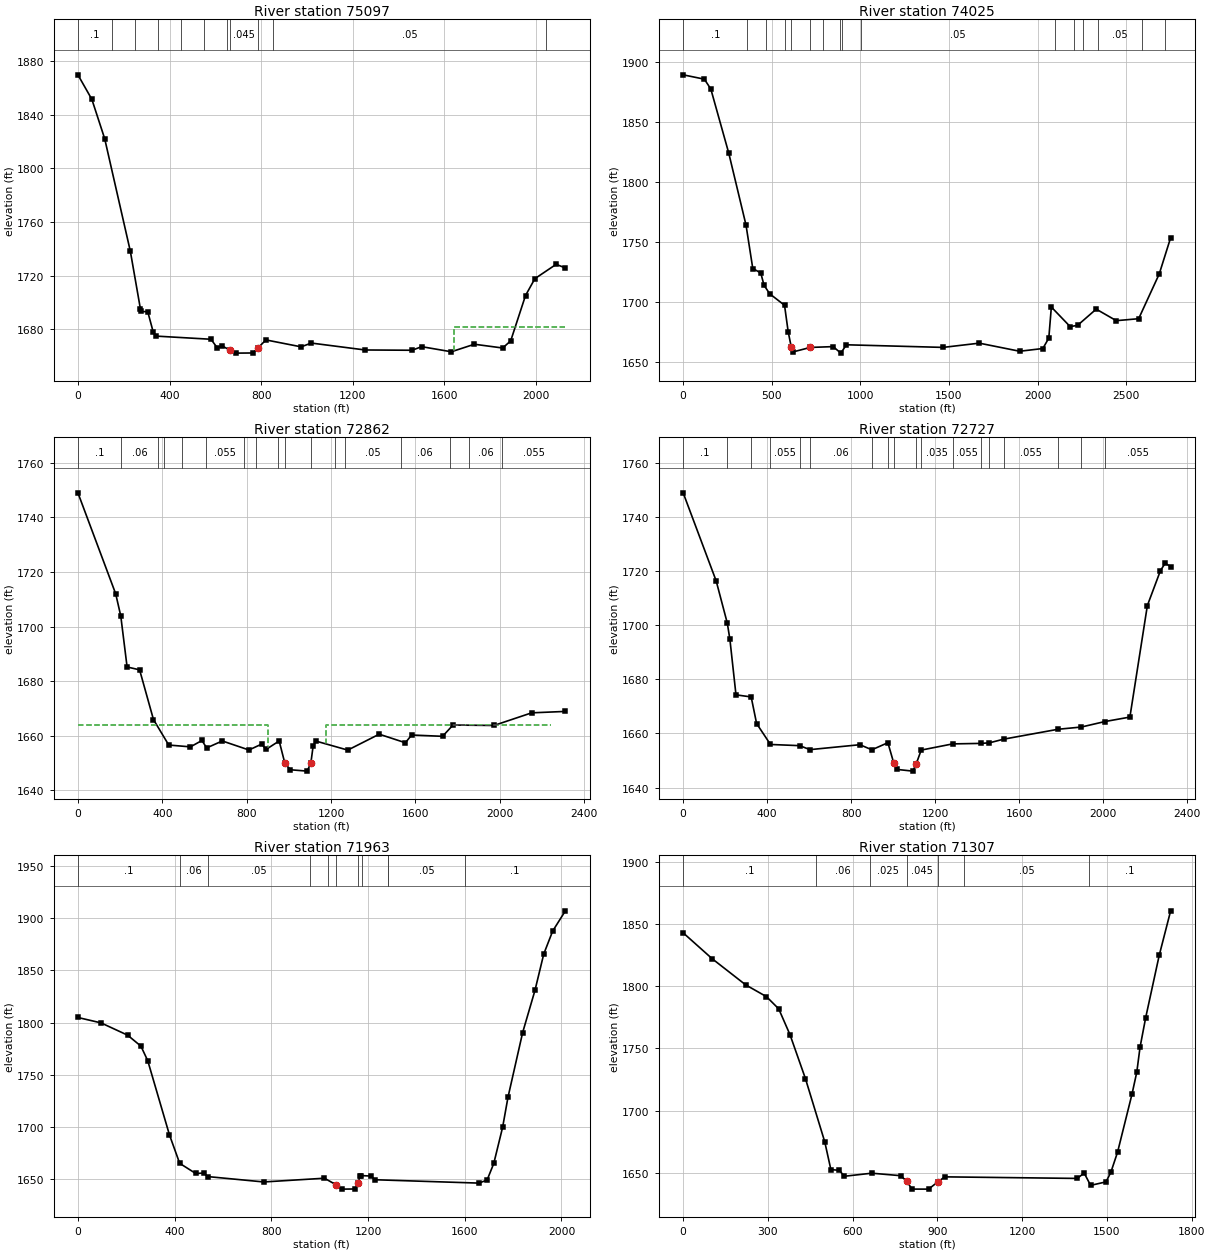
Type RM Length L Ch R = 1 ,75097   ,1090.6,1072,1037.2
XS GIS Cut Line= 3
2420933.81398785653564.5120992062421783.02521595653552.188304961
2423046.72511634653353.838307962
#Sta/Elev= 30
       0 1869.73    60.9 1851.45   116.9 1822.13     229 1738.17     273 1695.18
     277  1693.4     305 1693.17     329 1677.92     341 1675.03     581 1672.67
     609 1666.17     629 1667.74  665.881664.415     689 1662.34     765 1662.46
   785.51666.145     821 1672.18   974.5 1667.03  1019.1 1669.84  1253.9 1664.69
  1459.1 1664.48  1500.9 1667.15  1630.5 1663.35  1731.1 1668.96  1854.6 1666.16
  1889.6 1671.47  1954.4 1705.27  1995.3 1717.84    2088 1728.49  2128.5 1725.83
#Mann= 11 ,-1 , 0
       0      .1       0  149.45      .1       0  249.84     .06       0
  350.23      .1       0  450.62      .1       0     551     .05       0
  651.39      .1       0  665.88    .045       0   785.5    .025       0
  852.14     .05       0 2043.95      .1       0
#XS Ineff= 1 ,-1
 1641.59 2128.47 1681.65
Permanent Ineff=
       F
Bank Sta=665.88,785.5
XS Rating Curve= 0 ,0
Exp/Cntr=0.3,0.1

Type RM Length L Ch R = 1 ,74025   ,1163.4,1162.8,1137.6
XS GIS Cut Line= 6
2420953.43730819654902.2410510482421636.69709653654522.629277468
 2422759.9966872653772.4972475472422856.22188845653700.262155801
2422922.95338228653599.7712150512423187.74287894653330.072935551
#Sta/Elev= 30
       0 1889.37   119.7 1885.74   156.1 1877.51   257.3 1824.03   354.7 1763.98
     393 1727.68     438 1724.03   456.4 1713.72   488.7  1706.6   572.1 1697.05
   592.6 1675.07  610.381661.951   622.5 1658.22  717.951661.854   846.7 1662.53
   889.7  1657.1   921.4 1664.06  1467.2 1661.88  1671.3 1665.42  1899.1 1658.67
  2029.9 1660.94  2063.6 1669.62    2078 1695.57  2184.1 1679.25  2225.9 1680.26
  2331.2 1693.82  2444.6 1684.19  2570.8 1685.83  2687.1 1723.24  2751.3 1753.43
#Mann= 16 ,-1 , 0
       0      .1       0  362.75     .06       0  468.15      .1       0
  574.32     .05       0  610.38    .045       0  717.95     .05       0
   786.8    .025       0  882.58     .05       0  895.97      .1       0
 1005.13     .05       0 2096.78      .1       0 2207.96     .05       0
  2255.9      .1       0 2340.56     .05       0 2592.22      .1       0
 2717.92      .1       0
Bank Sta=610.38,717.95
XS Rating Curve= 0 ,0
Exp/Cntr=0.5,0.3

Type RM Length L Ch R = 1 ,72862   ,130.7,135.1,141.4
XS GIS Cut Line= 6
2421783.57869253655640.5256637042422177.69437411655339.241489381
2422378.26385486655175.8038241272422725.35732079654808.991237551
2422901.63677897654417.6238185222423059.20116887653815.376680128
#Sta/Elev= 30
       0 1749.01   179.2 1711.97   203.2 1703.88   233.2 1685.16   292.5 1684.12
   358.3 1665.88   430.8 1656.54   533.6 1655.88   588.1 1658.21   610.6 1655.49
   684.7 1658.04   811.1 1654.73   871.9 1656.91   891.6 1654.91   954.3 1658.03
  981.471649.818  1007.6 1647.48  1087.2 1646.98 1104.731649.992  1115.1 1656.02
    1128 1658.01  1279.7 1654.69  1428.8 1660.52  1552.8 1657.38  1582.4 1660.22
  1729.1 1659.74  1778.7 1663.88    1973 1663.72  2151.7 1668.35  2311.6 1668.87
#Mann= 17 ,-1 , 0
       0      .1       0   202.4     .06       0   381.8    .055       0
   406.4      .1       0  494.48     .06       0  609.09    .055       0
   789.9      .1       0   845.9     .06       0  949.22    .025       0
  981.47    .045       0 1104.73     .05       0 1220.82     .06       0
 1266.04     .05       0 1530.97     .06       0 1762.55     .05       0
 1852.24     .06       0 2012.88    .055       0
#XS Ineff= 2 ,-1
       0  903.54    1664 1174.53 2245.34    1664
Permanent Ineff=
       F       F
Bank Sta=981.47,1104.73
XS Rating Curve= 0 ,0
Exp/Cntr=0.5,0.3

Type RM Length L Ch R = 1 ,72727   ,756.8,764.7,774.1
XS GIS Cut Line= 4
2421860.07624295655741.5946872982422444.57113695 655262.81808579
2422758.94846094654986.6286775472423280.71250927653963.740631461
#Sta/Elev= 30
       0 1748.92   157.3 1716.36   210.3 1700.75   222.7 1694.75   251.6 1674.28
     324  1673.5   349.9 1663.66     416 1655.94   555.2  1655.5   603.9 1654.03
   842.1 1655.85   898.8 1653.97   975.3 1656.59 1002.65 1649.23  1017.8 1646.73
  1093.9 1646.09 1110.25 1648.77    1134 1653.86  1283.7 1656.15  1420.1 1656.34
  1459.1 1656.55  1527.5 1657.91  1786.2 1661.56  1896.7 1662.38  2009.2 1664.41
  2128.2 1666.06  2211.4 1707.27  2273.9 1720.21  2296.3  1722.9  2322.3 1721.68
#Mann= 18 ,-1 , 0
       0      .1       0   210.3     .06       0     324    .035       0
     416    .055       0   555.2     .05       0   603.9     .06       0
   898.8     .05       0   975.3     .06       0 1002.65    .045       0
 1110.25    .055       0    1134    .035       0  1283.7    .055       0
  1420.1     .06       0  1459.1    .035       0  1527.5    .055       0
  1786.2    .035       0  1896.7     .06       0  2009.2    .055       0
Bank Sta=1002.65,1110.25
XS Rating Curve= 0 ,0
Exp/Cntr=0.5,0.3

Type RM Length L Ch R = 1 ,71963   ,663.2,656,651.6
XS GIS Cut Line= 3
2422137.64556968656292.9895818832423216.29170635655620.264221296
2423864.62505534655253.107475296
#Sta/Elev= 30
       0 1804.87    95.6  1799.7   205.6 1787.93   260.6 1777.42   288.9 1763.42
   378.4 1692.56   420.9 1665.13   487.2 1655.41   519.9 1655.79   536.5 1652.44
   768.8 1647.28  1019.6 1650.86 1067.361644.641  1091.1 1640.41  1146.3 1640.55
  1159.31646.443  1165.7 1652.67  1172.4 1653.37  1212.8 1652.94  1227.6 1649.41
  1658.5 1646.18  1692.4  1649.1    1720 1664.97  1756.7 1699.74  1778.8 1728.38
  1839.5 1790.45  1890.4 1830.81  1926.8  1865.7  1963.7  1887.7  2016.3 1907.08
#Mann= 11 ,-1 , 0
       0      .1       0  422.22     .06       0  536.51     .05       0
  960.66      .1       0 1033.34     .05       0 1067.36    .045       0
  1159.3     .05       0 1176.03      .1       0 1282.92    .025       0
 1283.51     .05       0 1601.22      .1       0
Bank Sta=1067.36,1159.3
XS Rating Curve= 0 ,0
Exp/Cntr=0.3,0.1

Type RM Length L Ch R = 1 ,71307   ,554.4,538.6,516.1
XS GIS Cut Line= 2
2422618.61376786656810.4140719622424023.77467144655808.738253787
#Sta/Elev= 30
       0 1843.06   103.3 1822.11   221.2  1801.2   294.9  1791.7   338.2 1781.89
   378.2 1761.07   432.8 1725.75   501.2 1674.84   522.9 1652.49   553.3 1651.91
     570 1647.12   667.6  1649.6     771 1647.58  790.921642.996   810.7 1636.81
   868.7 1636.78  902.76 1642.82   926.1 1646.66  1395.3 1645.39  1419.4 1649.77
  1442.3 1639.81  1496.8 1642.61    1514 1650.38  1537.7 1666.53  1588.6 1713.04
  1605.8 1731.01  1617.2 1750.89  1637.3 1774.87  1685.1 1824.89  1725.6 1860.78
#Mann= 7 ,-1 , 0
       0      .1       0  469.45     .06       0  661.69    .025       0
  790.92    .045       0  902.76      .1       0  993.97     .05       0
 1437.01      .1       0
Bank Sta=790.92,902.76
XS Rating Curve= 0 ,0
Exp/Cntr=0.3,0.1

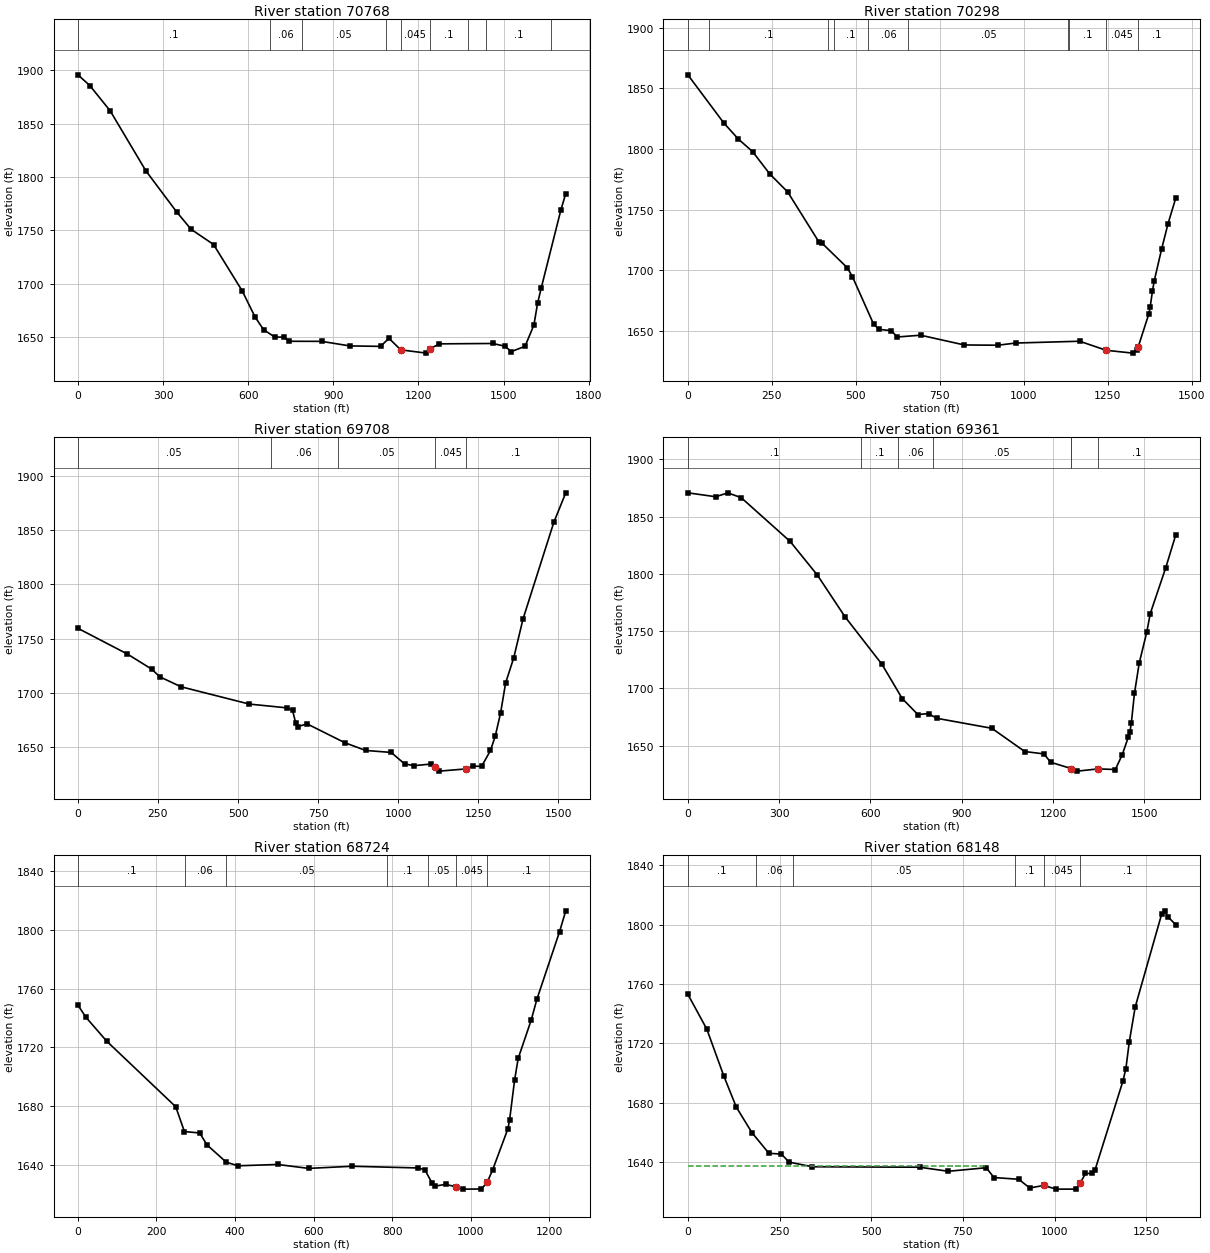
Type RM Length L Ch R = 1 ,70768   ,463.9,469.8,484
XS GIS Cut Line= 5
2422926.70075011657353.6216469562423384.59123853656953.004337966
2423635.30366361656748.706518218 2423857.3918021656435.432538465
2424169.69727987656180.043285459
#Sta/Elev= 30
       0 1895.64    41.7 1885.62   113.5 1861.96   239.2 1805.76   347.8 1767.18
   398.8 1750.86     478  1736.6   579.4 1692.92   624.4  1668.6   654.1 1656.82
   693.7 1649.82   725.2 1649.77   745.3 1645.89   858.7 1645.81   958.6 1641.53
  1066.4 1641.12  1096.3 1648.66 1137.681637.841  1228.3 1634.78 1240.611638.811
  1274.1 1643.47  1462.3 1643.83  1504.8 1641.27  1527.5 1636.19  1575.9 1641.22
  1607.1 1661.13    1620 1681.51  1632.6 1695.52  1702.1 1768.92  1719.3 1784.33
#Mann= 9 ,-1 , 0
       0      .1       0  676.15     .06       0  790.79     .05       0
 1086.05    .025       0 1137.68    .045       0 1240.61      .1       0
 1375.52     .05       0  1437.2      .1       0 1666.71     .12       0
Bank Sta=1137.68,1240.61
XS Rating Curve= 0 ,0
Exp/Cntr=0.3,0.1

Type RM Length L Ch R = 1 ,70298   ,578.1,590.7,597.6
XS GIS Cut Line= 3
2423284.14032394657528.6773992182424112.50120002656765.095921129
2424359.01415843656552.049103126
#Sta/Elev= 30
       0 1861.04   106.9 1821.41   150.4 1808.07   192.8 1797.76   243.7  1779.4
   297.3 1764.48   389.8 1723.49   399.4 1722.32   474.8    1702     490  1694.7
     553  1655.6   569.3 1651.24   606.1 1650.17     623 1644.96   693.1 1646.44
     823  1638.4   923.1 1638.18   976.4 1639.99  1166.6 1641.47 1245.811633.984
  1325.4 1631.67  1335.8    1634 1341.171637.039  1372.8 1664.27  1376.5 1669.63
  1383.3  1682.8  1388.6 1691.28  1410.5 1717.32  1429.7 1738.38  1452.4 1759.22
#Mann= 10 ,-1 , 0
       0      .1       0   61.54      .1       0  418.68     .05       0
  434.99      .1       0  537.73     .06       0  656.77     .05       0
 1132.83    .025       0 1136.08      .1       0 1245.81    .045       0
 1341.17      .1       0
Bank Sta=1245.81,1341.17
XS Rating Curve= 0 ,0
Exp/Cntr=0.3,0.1

Type RM Length L Ch R = 1 ,69708   ,348.7,346.5,341.4
XS GIS Cut Line= 3
2423457.01038504657843.9910730422423936.17773378657469.760522291
2424741.85361585 657035.69478938
#Sta/Elev= 30
       0 1759.52   154.5 1735.83   230.6 1721.88   255.6 1714.88   321.9 1705.72
   534.9 1689.79   651.8 1686.33     670 1684.22   679.9 1672.47   685.8 1668.95
   715.4 1671.59   833.3 1654.23   898.4 1647.08   978.1 1645.29  1019.8 1634.76
    1049 1633.09  1101.6 1634.56 1115.521631.683  1128.7 1628.07 1211.441630.096
  1233.4 1632.64  1260.6  1632.5  1288.2  1647.1  1302.9 1660.09  1319.7  1681.5
  1335.4 1709.19  1360.6 1732.16  1389.9 1768.23    1486 1857.11  1523.2 1884.22
#Mann= 5 ,-1 , 0
       0     .05       0  601.35     .06       0  812.04     .05       0
 1115.52    .045       0 1211.44      .1       0
Bank Sta=1115.52,1211.44
XS Rating Curve= 0 ,0
Exp/Cntr=0.3,0.1

Type RM Length L Ch R = 1 ,69361   ,630.4,637.5,642.4
XS GIS Cut Line= 4
2423596.35065752658354.0891342162424076.91990635657893.069386959
2424446.33911502657595.1959669592424832.41478643657340.997328371
#Sta/Elev= 30
       0 1870.68    91.3 1867.27   131.3 1870.63   175.2 1866.48   335.9  1828.3
   425.5  1798.9     516 1762.61   637.7    1721   704.3 1691.12   755.6 1677.17
   791.1 1677.94   817.3  1673.9   998.8 1665.13  1106.9 1644.86  1170.1 1642.77
    1192  1635.5 1260.051629.955  1279.9 1627.75 1347.711629.701  1404.4 1629.17
  1426.9 1641.85  1447.5 1657.73  1452.3 1661.84  1457.1 1669.95  1467.3 1695.54
  1482.9 1721.98  1507.8  1749.1  1519.3 1765.32  1570.2 1805.36  1602.7 1833.68
#Mann= 7 ,-1 , 0
       0      .1       0  567.78      .1       0  691.63     .06       0
  805.94     .05       0 1257.29      .1       0 1260.05    .045       0
 1347.71      .1       0
Bank Sta=1260.05,1347.71
XS Rating Curve= 0 ,0
Exp/Cntr=0.3,0.1

Type RM Length L Ch R = 1 ,68724   ,570.4,575.3,579
XS GIS Cut Line= 2
2424024.48365954658452.1565233772425152.75075993657932.148377046
#Sta/Elev= 30
       0 1748.74    20.1 1740.57      73 1724.31   249.1 1679.66   271.2  1662.8
   310.2 1661.85   328.4 1653.81   377.8 1641.98   407.7 1639.55     509 1640.44
   587.5 1637.78   698.4 1639.24   864.9 1638.08   883.4 1636.91   901.3 1628.03
   909.8 1625.75   936.2  1626.9  962.711625.284   980.3 1623.69  1027.7 1623.77
  1042.61628.536  1055.9 1636.61  1094.8 1664.58  1099.2 1670.47  1112.1 1697.93
  1121.2 1712.58    1154 1738.31  1168.9 1752.79  1226.7 1798.77  1242.3 1812.82
#Mann= 7 ,-1 , 0
       0      .1       0  272.84     .06       0  375.92     .05       0
  788.25      .1       0  891.33     .05       0  962.71    .045       0
  1042.6      .1       0
Bank Sta=962.71,1042.6
XS Rating Curve= 0 ,0
Exp/Cntr=0.3,0.1

Type RM Length L Ch R = 1 ,68148   ,569.4,583.6,588.9
XS GIS Cut Line= 2
2424177.82357594658901.7127108722425434.94310895 658466.25590463
#Sta/Elev= 30
       0  1753.1    51.8 1729.55    98.3 1697.86   132.2 1676.99   174.5 1659.88
   221.1 1645.84     255 1645.34   276.1 1639.89   339.6 1636.78   631.9 1636.47
   710.4 1633.73   813.7 1636.12   834.9 1629.51   902.6 1628.32   932.3 1622.47
  970.841624.191  1004.2 1621.69  1059.3 1621.69 1070.721625.981  1084.5 1632.25
  1103.4 1632.29  1110.1 1634.32  1186.3 1694.34  1194.6  1702.9    1204 1721.19
  1220.1 1744.55    1292    1807  1300.6 1809.38    1309 1805.38  1330.4 1800.12
#Mann= 6 ,-1 , 0
       0      .1       0  186.23     .06       0  287.05     .05       0
  891.95      .1       0  970.84    .045       0 1070.72      .1       0
#XS Ineff= 2 , 0
          807.24 1637.37
Permanent Ineff=
       F       F
Bank Sta=970.84,1070.72
XS Rating Curve= 0 ,0
Exp/Cntr=0.3,0.1

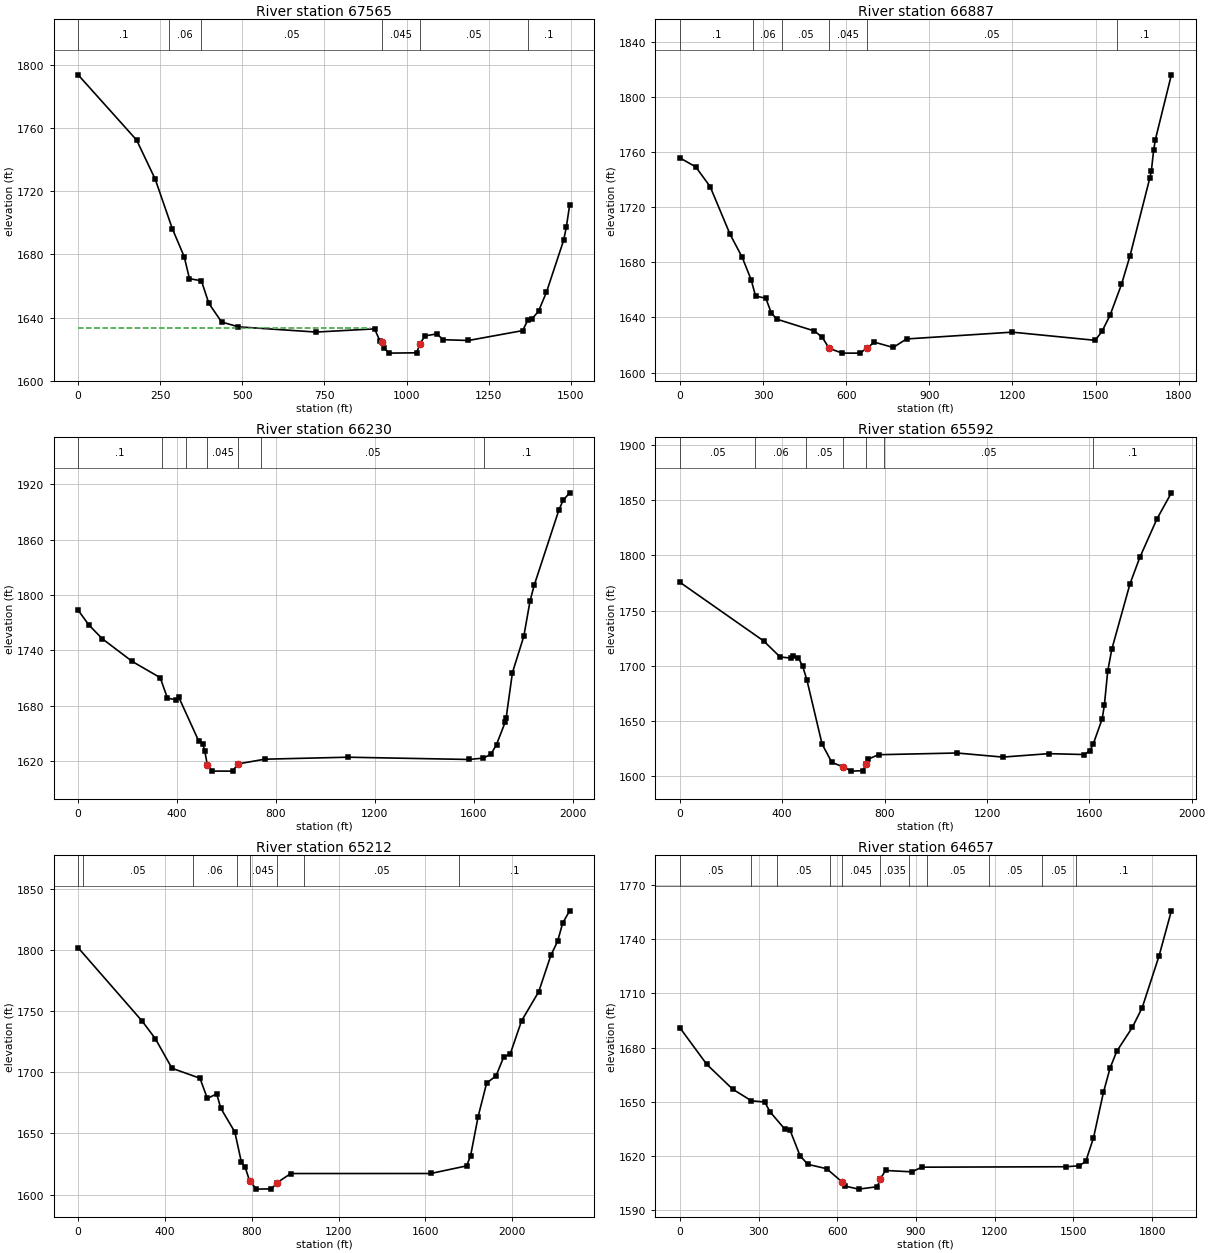
Type RM Length L Ch R = 1 ,67565   ,673.1,677.8,687.1
XS GIS Cut Line= 2
2424141.77017036659252.7172582152425628.94534561659085.751384795
#Sta/Elev= 30
       0 1793.49   178.1 1752.26   234.8  1727.5   286.8 1696.26     323 1678.53
     339 1664.66   375.4  1663.3     398 1649.04   436.8 1637.29     488  1634.2
   724.5 1630.91   902.6 1632.92   918.7 1625.41  925.851624.361   930.8 1620.97
   946.9 1617.59  1030.3  1617.8 1041.581623.608  1055.6 1628.47  1091.8 1629.72
  1111.9 1626.07  1188.4 1625.58  1353.4 1631.83  1369.5 1638.58    1382 1639.25
  1401.7 1644.06  1425.9  1656.1  1478.2 1688.91  1486.3  1697.1  1496.5 1711.17
#Mann= 6 ,-1 , 0
       0      .1       0  275.55     .06       0  374.99     .05       0
  925.85    .045       0 1041.58     .05       0 1369.34      .1       0
#XS Ineff= 2 , 0
          889.99 1633.17
Permanent Ineff=
       F       F
Bank Sta=925.85,1041.58
XS Rating Curve= 0 ,0
Exp/Cntr=0.3,0.1

Type RM Length L Ch R = 1 ,66887   ,680.5,656.8,636.1
XS GIS Cut Line= 3
2424341.79306427659768.1368310452425478.09886253659825.554367125
2426092.76462793659661.857844129
#Sta/Elev= 30
       0  1755.7    57.2 1749.21   109.1 1734.94   181.2  1700.3   225.2  1683.5
   257.3 1667.26   273.3 1655.44   310.3 1653.91   329.4 1643.48   349.4 1638.72
   485.6 1630.12   513.6 1625.57  538.941617.551   585.7 1614.06   649.8 1614.06
  674.671617.578   701.8 1622.02   769.9 1618.16     818 1624.34  1199.3 1629.28
  1498.6 1623.35  1523.4 1629.81  1552.4 1641.51  1593.8 1663.93  1624.3 1684.46
  1696.2 1741.27  1701.4 1745.95  1709.7 1761.11    1716 1768.96  1773.8 1815.96
#Mann= 6 ,-1 , 0
       0      .1       0  265.49     .06       0  367.06     .05       0
  538.94    .045       0  674.67     .05       0 1578.16      .1       0
Bank Sta=538.94,674.67
XS Rating Curve= 0 ,0
Exp/Cntr=0.3,0.1

Type RM Length L Ch R = 1 ,66230   ,649.1,638.2,631
XS GIS Cut Line= 3
2424501.98434493660599.7759158022425191.26249394660385.197932884
2426399.66886976660009.720337376
#Sta/Elev= 30
       0 1783.67    42.7 1767.84    97.2 1752.81   218.6 1728.13   331.8 1710.57
   361.1 1688.41   394.6 1686.65   407.2 1689.21   486.8 1642.41   503.5 1639.08
   511.9 1631.31  522.481616.098   541.2 1609.38     625 1609.35  646.13 1617.15
   754.9 1622.28  1090.8 1624.42  1578.9 1621.97  1638.7 1623.44  1669.3 1627.78
  1691.6 1638.14  1726.8 1662.43  1730.8  1667.4    1756 1716.04    1802 1755.37
  1827.2 1793.59  1843.9 1810.53  1944.4 1892.54  1961.2  1902.7  1987.3 1910.68
#Mann= 7 ,-1 , 0
       0      .1       0  337.22     .06       0  437.54      .1       0
  522.48    .045       0  646.13     .06       0  738.47     .05       0
 1641.21      .1       0
Bank Sta=522.48,646.13
XS Rating Curve= 0 ,0
Exp/Cntr=0.3,0.1

Type RM Length L Ch R = 1 ,65592   ,380.2,380.1,381.7
XS GIS Cut Line= 4
2424828.06243294 661104.209946292425290.42764995660964.097693712
2425665.86390695 660831.262001382426618.80294594660416.933433712
#Sta/Elev= 30
       0 1775.66   327.2 1722.48   391.5 1707.97     433 1706.87   442.7 1709.15
   462.6 1707.19   479.3 1699.93   496.2 1687.26   555.6 1629.02   593.8 1612.32
  638.441608.254   670.2 1604.41   716.2 1604.81  726.061610.986   733.8 1615.06
   776.2  1619.3  1082.9 1620.84  1261.8 1617.13  1440.6 1620.25  1580.2 1619.45
    1602 1622.94    1615  1628.9    1650 1651.67  1658.7 1664.26  1671.8 1695.12
  1687.9 1715.09    1759 1774.39  1797.4  1798.3  1864.2  1833.1  1920.5 1856.74
#Mann= 7 ,-1 , 0
       0     .05       0  293.98     .06       0  494.48     .05       0
  638.44    .045       0  726.06     .06       0  797.28     .05       0
 1615.88      .1       0
Bank Sta=638.44,726.06
XS Rating Curve= 0 ,0
Exp/Cntr=0.3,0.1

Type RM Length L Ch R = 1 ,65212   ,543.9,554.6,560
XS GIS Cut Line= 3
2424872.98688376661547.6759228712425816.68808037661167.923401549
2426961.89477944660674.227866635
#Sta/Elev= 30
       0 1802.16   295.1 1742.01   355.5 1727.71   432.4 1703.41   561.5 1695.23
   595.3 1678.67   638.4 1682.44   657.3 1670.66     722 1651.16   752.1 1626.47
   769.4 1622.43  789.861611.239   821.1 1604.42   890.1 1604.64  917.511609.784
   979.6 1617.19  1624.1 1617.22  1789.7 1623.45    1808 1631.78  1842.7 1663.82
  1881.9 1691.27  1925.5 1697.23  1960.3 1712.55  1990.8 1715.24  2043.1 1742.37
  2121.8 1766.07  2178.1 1796.08  2208.6 1807.27  2232.3 1822.35  2264.3 1832.36
#Mann= 8 ,-1 , 0
       0      .1       0   20.55     .05       0  529.61     .06       0
  732.67     .05       0  789.86    .045       0  917.51     .06       0
 1038.79     .05       0 1755.64      .1       0
Bank Sta=789.86,917.51
XS Rating Curve= 0 ,0
Exp/Cntr=0.3,0.1

Type RM Length L Ch R = 1 ,64657   ,399.4,415,414.1
XS GIS Cut Line= 3
2425375.86809585661855.2986672072426135.20942494661602.785720795
 2427152.1197927661258.938639462
#Sta/Elev= 30
       0 1690.94   102.7 1670.68   201.2    1657   272.8 1650.55   323.4  1649.9
   344.2 1644.39   399.3 1635.04   420.4 1634.19   458.1  1620.2   487.8 1615.45
   559.5 1613.03  617.091605.885     629 1603.45   681.7 1601.75   752.3 1603.08
   764.4 1607.44     784 1612.07   884.2  1611.3   922.2 1613.88  1471.1 1614.12
  1522.4 1614.65  1547.1 1617.02  1576.7 1630.02  1614.7 1655.22    1640 1668.64
  1665.3 1677.87  1724.7 1691.08  1762.5 1702.05  1826.8 1730.64  1873.7 1755.53
#Mann= 11 ,-1 , 0
       0     .05       0  271.58     .06       0  372.18     .05       0
  573.39     .06       0  617.09    .045       0   764.4    .035       0
  875.27     .06       0  940.65     .05       0 1177.34     .05       0
 1378.72     .05       0 1510.81      .1       0
Bank Sta=617.09,764.4
XS Rating Curve= 0 ,0
Exp/Cntr=0.3,0.1

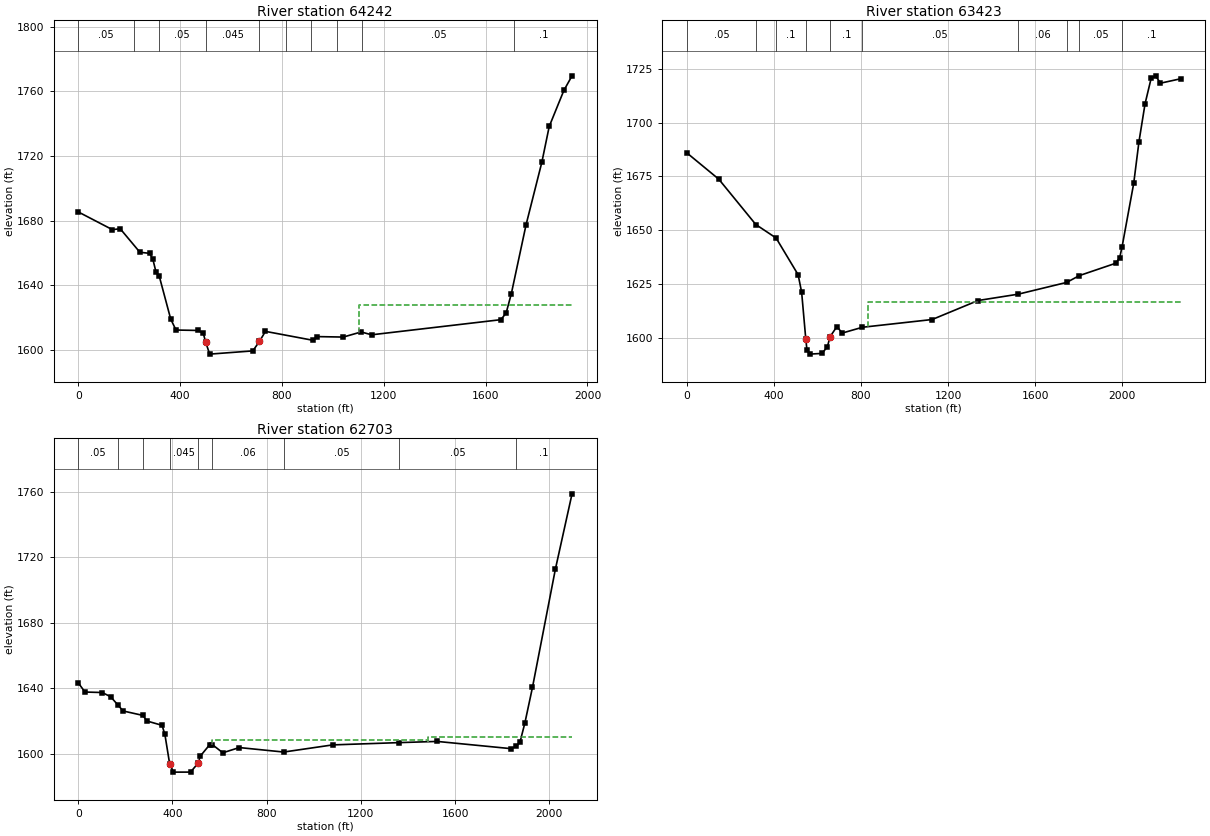
Type RM Length L Ch R = 1 ,64242   ,792,819.6,816.1
XS GIS Cut Line= 3
2425579.18625876662166.7645797132426442.25441453661941.970081791
2427457.76386645661684.911868885
#Sta/Elev= 30
       0  1685.5     134 1674.54   164.9 1675.08   242.2 1660.54   280.6 1659.88
     293 1656.25   305.4 1648.36   317.8 1646.01   363.3 1619.19     384 1612.46
   470.8  1612.2   491.4 1610.34  499.92 1605.25   516.2 1597.56   685.7 1599.56
  711.891605.468   735.3 1611.63   920.7 1606.15   937.8  1608.4  1040.9 1608.11
  1111.1 1611.27  1152.3 1609.51  1659.8 1618.86  1680.5 1622.95  1701.1 1635.03
  1758.9 1677.58  1820.8  1716.2  1849.8 1738.33  1907.4 1760.64  1939.4 1769.64
#Mann= 10 ,-1 , 0
       0     .05       0  217.52     .06       0  317.28     .05       0
  499.92    .045       0  711.89    .055       0  816.07     .05       0
  915.81      .1       0  1015.5     .06       0  1115.2     .05       0
 1713.37      .1       0
#XS Ineff= 2 , 0
                         1100.89          1628.1
Permanent Ineff=
       F       F
Bank Sta=499.92,711.89
XS Rating Curve= 0 ,0
Exp/Cntr=0.3,0.1

Type RM Length L Ch R = 1 ,63423   ,718,719.5,721.1
XS GIS Cut Line= 4
2425702.14631468662884.9491669682426485.49284512662758.700731799
 2427859.4271051662615.9444556242427950.13525704662643.452602714
#Sta/Elev= 30
       0 1685.92   146.5  1673.7   316.6 1652.61   409.8 1646.34   511.1 1629.25
   527.3  1621.1  546.251599.402   551.6 1594.36   563.8 1592.31   620.5 1592.64
   645.5 1595.68  657.891600.429   689.4 1605.12   713.7 1602.11   806.8 1604.81
  1127.2 1608.41  1338.1 1617.25  1522.1 1620.19  1745.2 1625.67  1803.5 1628.84
  1971.1  1634.6  1989.1 1637.19  2000.3 1642.37  2053.5 1671.76  2077.6 1691.11
  2105.7 1708.82  2133.9 1720.72    2154 1721.79  2176.6 1718.37  2269.6 1720.43
#Mann= 10 ,-1 , 0
       0     .05       0   316.6     .06       0   409.8      .1       0
  546.25    .045       0  657.89      .1       0   806.8     .05       0
  1522.1     .06       0  1745.2    .055       0  1803.5     .05       0
  2000.3      .1       0
#XS Ineff= 2 , 0
                          831.86         1616.74
Permanent Ineff=
       F       F
Bank Sta=546.25,657.89
XS Rating Curve= 0 ,0
Exp/Cntr=0.5,0.3

Type RM Length L Ch R = 1 ,62703   ,71.2,71.2,71.4
XS GIS Cut Line= 3
2425954.26326454663560.969140381 2426806.8740921663446.256115213
2428028.70465368663261.109831959
#Sta/Elev= 30
       0 1643.21    28.7 1637.59   101.9 1637.29   137.5 1634.71   169.5 1629.52
   190.2 1626.03   274.9 1623.29   291.1 1619.91   355.7 1617.25   367.8 1611.73
   387.9 1593.85   404.1 1588.65   476.7 1588.67     509 1594.15   518.1 1598.43
   557.5 1605.31   569.6 1605.43   613.7 1600.47   683.7 1603.66   872.3 1600.92
  1080.2 1605.29    1362 1606.68  1523.7 1607.41  1835.2 1603.02  1859.4 1604.33
    1875 1606.88  1895.9 1618.68  1928.2 1640.48  2025.3 1712.59  2096.1  1758.7
#Mann= 9 ,-1 , 0
       0     .05       0   169.5     .06       0   274.9     .05       0
   387.9    .045       0     509     .05       0   569.6     .06       0
   872.3     .05       0    1362     .05       0  1859.4      .1       0
#XS Ineff= 3 ,-1
       0     341  1608.3     568    1485  1608.3    1485    2400    1610
Permanent Ineff=
       F       F       F
Bank Sta=387.9,509
XS Rating Curve= 0 ,0
Exp/Cntr=0.8,0.5