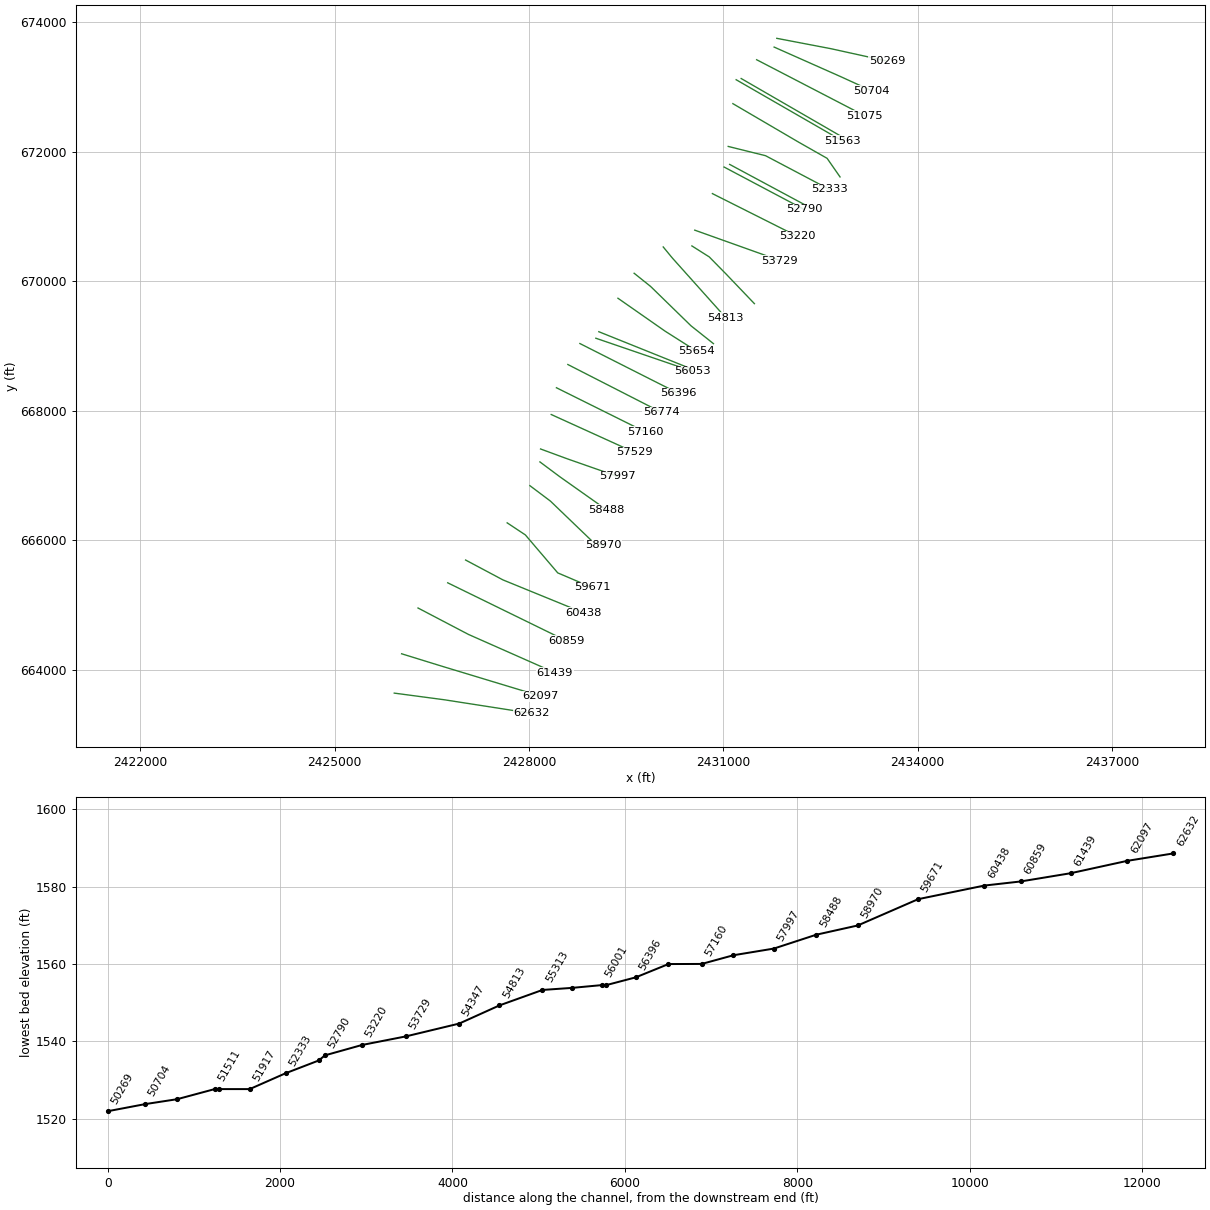
HEC-RAS study NFSBPOTOMC.prj: NFSBPOTOMC

--- NFSBPOTOMC.g01 (geometry) --- (continued)

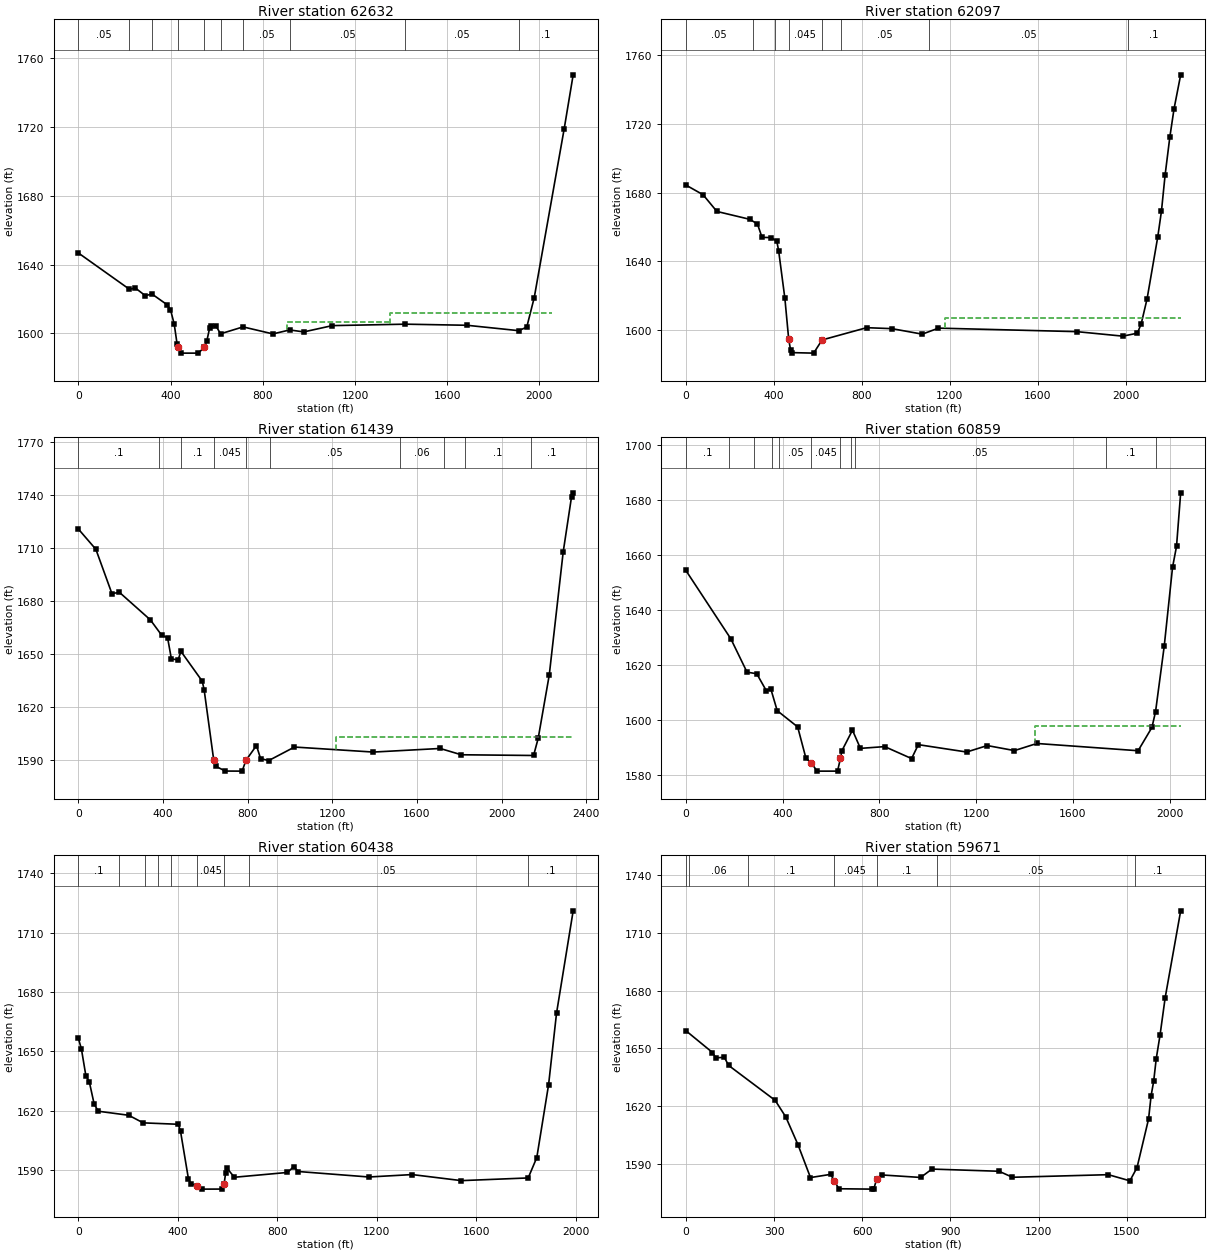
Type RM Length L Ch R = 1 ,62632   ,546.6,535.3,523.8
XS GIS Cut Line= 3
2425918.31418943663636.7832932172426687.38286129663534.610925376
2428041.58192453663323.822304964
#Sta/Elev= 30
       0 1646.77   221.7 1625.67   247.8 1626.36     291 1621.91   319.2 1622.94
   383.8 1616.82   399.9 1613.82   416.1 1605.41   428.2 1594.17   432.2 1592.07
   444.3 1588.59     521 1588.59   545.2 1591.87   557.3  1595.6   569.4 1602.96
   577.5 1604.57   597.6 1604.21   617.2 1599.82   714.5 1603.82     844 1599.75
   916.9 1602.05   978.2 1600.91  1101.4 1604.56  1418.8  1605.4  1685.8 1604.76
    1910 1601.63    1945 1603.68  1977.5 1620.87    2107 1718.57  2146.3 1750.16
#Mann= 10 ,-1 , 0
       0     .05       0   221.7     .06       0   319.2    .055       0
   432.2    .045       0   545.2    .055       0   617.2     .06       0
   714.5     .05       0   916.9     .05       0  1418.8     .05       0
    1910      .1       0
#XS Ineff= 2 ,-1
  907.08 1353.98  1606.8 1353.98  2053.1  1611.9
Permanent Ineff=
       F       F
Bank Sta=432.2,545.2
XS Rating Curve= 0 ,0
Exp/Cntr=0.5,0.3

Type RM Length L Ch R = 1 ,62097   ,664.6,657.3,637.4
XS GIS Cut Line= 3
2426031.77787328664244.5406078852426673.04430726 664046.54756555
2428182.27980587663589.111472547
#Sta/Elev= 30
       0 1684.41    78.5 1678.75   141.3 1669.03   290.3 1664.47   325.5 1661.75
   346.4 1653.94   388.2 1653.85   413.4 1651.69   421.7 1646.29   450.2 1618.45
   467.41594.885   476.2 1588.32   480.3 1586.97   580.8 1586.67   619.21594.327
   821.6 1601.46   936.2  1600.9  1074.2  1597.7    1148  1601.2  1776.4 1599.16
  1985.3 1596.54  2051.5 1598.26  2068.9 1603.72  2095.6 1618.24  2144.2 1654.29
  2160.9 1669.22  2177.6 1690.35    2199 1712.32  2218.2 1728.79  2248.2 1748.45
#Mann= 8 ,-1 , 0
       0     .05       0  303.89     .06       0  404.17      .1       0
   467.4    .045       0   619.2    .055       0  704.98     .05       0
 1105.82     .05       0  2007.7      .1       0
#XS Ineff= 1 ,-1
 1176.99 2248.17 1607.34
Permanent Ineff=
       F
Bank Sta=467.4,619.2
XS Rating Curve= 0 ,0
Exp/Cntr=0.3,0.1

Type RM Length L Ch R = 1 ,61439   ,582.3,579.9,580.3
XS GIS Cut Line= 3
2426285.13268152664951.8105188012427064.35750103664543.355298966
2428397.77740636663952.861073121
#Sta/Elev= 30
       0 1720.82    83.1 1709.26   158.9 1684.16   194.5 1684.85   340.5 1669.26
   394.7 1660.43   421.8 1659.19   439.9 1647.11   471.5 1646.56   485.1 1651.37
   585.6 1634.49   594.5  1629.7  639.851589.759   650.8 1586.15   694.5 1583.51
   774.1 1583.47  791.811589.509   841.8 1597.99   861.2 1590.58   899.9 1589.47
  1021.4 1597.13  1394.2 1594.28  1709.7 1596.32  1809.5 1592.75  2151.1 1592.34
  2172.9 1602.11  2225.1 1637.97    2291 1707.79  2330.4 1739.09  2338.1  1741.3
#Mann= 10 ,-1 , 0
       0      .1       0  382.37     .06       0  487.07      .1       0
  639.85    .045       0  791.81      .1       0  905.36     .05       0
 1521.35     .06       0 1726.68     .05       0 1829.34      .1       0
 2137.34      .1       0
#XS Ineff= 2 , 0
                         1216.81         1602.78
Permanent Ineff=
       F       F
Bank Sta=639.85,791.81
XS Rating Curve= 0 ,0
Exp/Cntr=0.3,0.1

Type RM Length L Ch R = 1 ,60859   ,424.6,421.5,419.9
XS GIS Cut Line= 2
2426743.29022977665341.1830996272428580.86627904664441.965081796
#Sta/Elev= 30
       0  1654.4   186.4 1629.45   253.2 1617.34   293.3 1616.78   333.2 1610.54
   351.2 1611.34   377.9 1603.34   462.5 1597.42   496.6 1586.06  519.44 1584.26
   542.7 1581.34   627.3 1581.34  639.311585.952   645.1 1588.71     689 1596.23
   721.9 1589.62   822.3 1590.26   933.4 1585.91   961.3 1590.97    1161 1588.29
  1246.3 1590.64  1358.8 1588.81  1451.2  1591.4  1869.8 1588.76  1926.9 1597.22
  1941.9 1602.95  1977.7 1626.71  2012.3 1655.57  2028.6 1663.08  2045.8 1682.59
#Mann= 11 ,-1 , 0
       0      .1       0  179.11     .06       0  282.89    .055       0
  354.41      .1       0  386.67     .05       0  519.44    .045       0
  639.31    .025       0  683.45    .055       0  698.01     .05       0
 1735.81      .1       0 1943.37      .1       0
#XS Ineff= 2 , 0
                         1442.48         1597.79
Permanent Ineff=
       F       F
Bank Sta=519.44,639.31
XS Rating Curve= 0 ,0
Exp/Cntr=0.3,0.1

Type RM Length L Ch R = 1 ,60438   ,782.8,766.9,744.6
XS GIS Cut Line= 3
2427019.75063485665692.8966350412427597.67730051665385.364441708
 2428834.2283051664880.116764545
#Sta/Elev= 30
       0 1656.68    12.5 1651.22    30.6 1637.58    44.2 1634.62    63.9 1623.29
    80.4 1619.68   202.8 1617.64     261  1613.8   402.1 1613.08   411.2 1609.53
   442.9 1585.58   453.2 1582.95  476.841582.056   497.3 1580.28   578.8 1580.31
   586.81583.003   592.4 1588.37   598.1 1590.86   627.7 1586.28   841.4 1588.72
     866  1591.6   884.8 1589.19  1168.8 1586.42  1342.9 1587.64  1540.8 1584.58
  1809.5 1585.94  1844.1 1596.25  1891.6 1633.18  1923.4  1669.2  1990.4 1721.05
#Mann= 9 ,-1 , 0
       0      .1       0  162.08    .055       0     267    .035       0
  319.17      .1       0  371.92     .05       0  476.84    .045       0
   586.8      .1       0  685.77     .05       0 1807.05      .1       0
Bank Sta=476.84,586.8
XS Rating Curve= 0 ,0
Exp/Cntr=0.3,0.1

Type RM Length L Ch R = 1 ,59671   ,691.2,701.1,696.6
XS GIS Cut Line= 4
2427661.56332761666267.5404988832427942.37346151666081.087787792
2428442.33473194 665494.496441292428971.19522277  665268.6425623
#Sta/Elev= 30
       0 1659.17    90.8 1647.79   102.2 1645.04   131.2 1645.27   145.6 1641.08
   303.9 1622.92     340 1614.31   381.5 1599.87     424 1582.78   492.4 1584.44
   504.8  1581.2   520.5 1576.96   634.3 1576.77   639.7 1577.02  648.571581.779
   665.8 1584.15   798.6 1582.84   837.1 1587.19  1065.3 1586.06  1110.9 1582.93
    1437 1584.28  1510.2 1581.09  1534.5 1587.98  1573.7 1613.22  1582.4 1625.39
  1591.1 1632.85  1599.8 1644.57  1612.8 1656.91  1630.2 1676.29  1682.9 1721.44
#Mann= 7 ,-1 , 0
       0      .1       0   10.01     .06       0  211.39      .1       0
   504.8    .045       0  648.57      .1       0   854.4     .05       0
  1525.9      .1       0
Bank Sta=504.8,648.57
XS Rating Curve= 0 ,0
Exp/Cntr=0.3,0.1

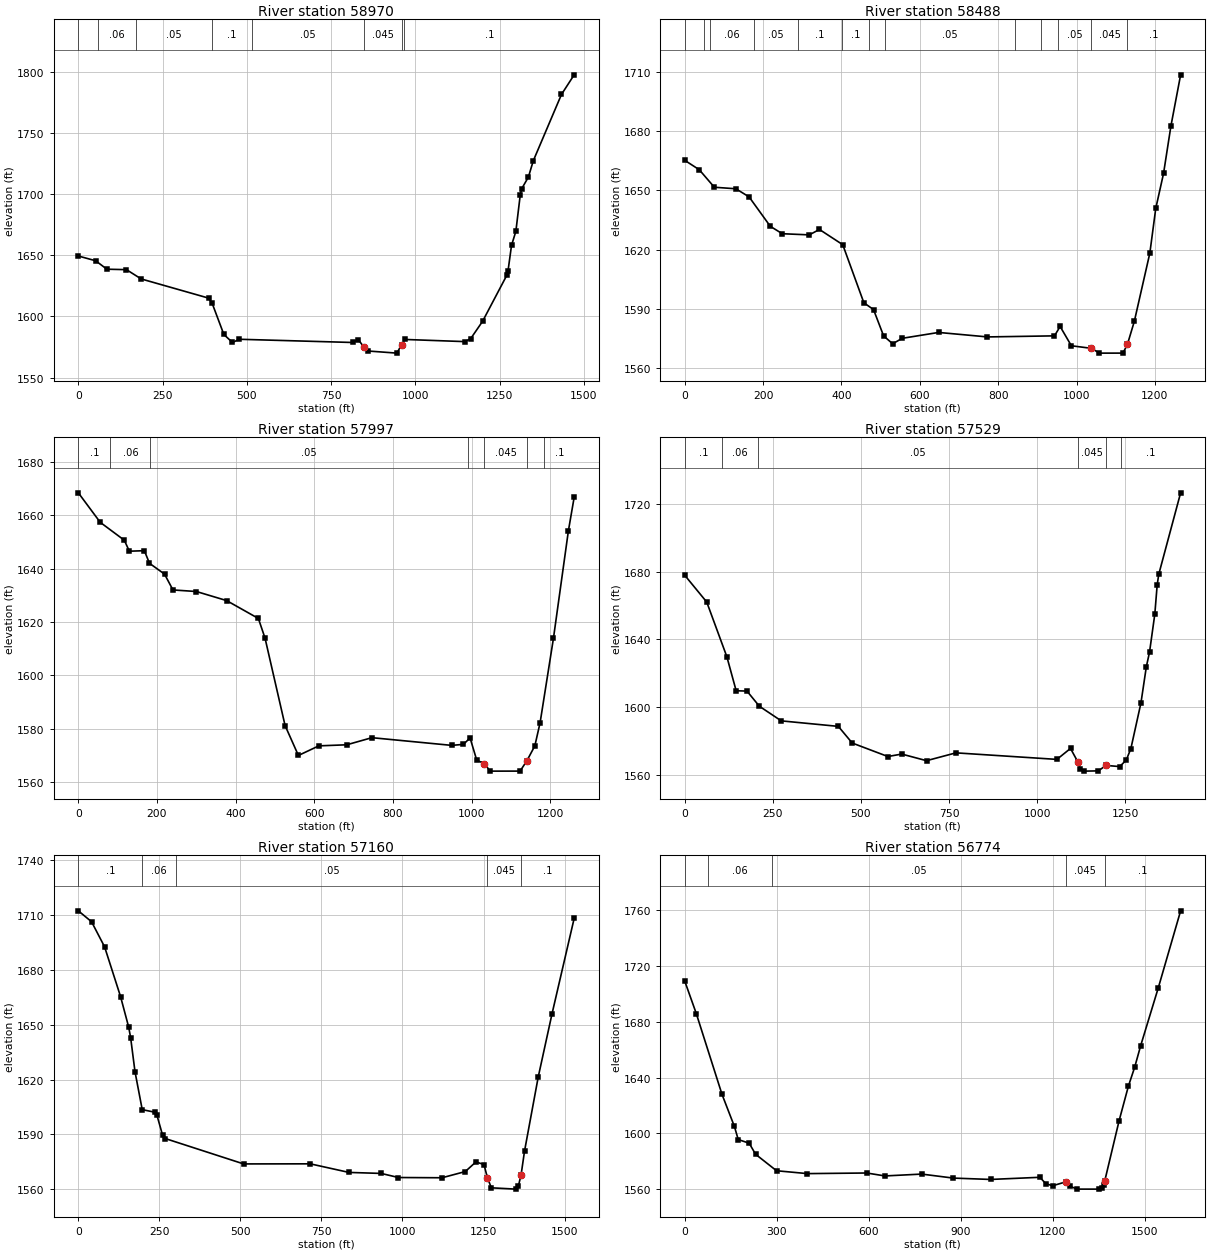
Type RM Length L Ch R = 1 ,58970   ,477.2,481.5,489.6
XS GIS Cut Line= 4
2428012.56164137666841.8290484552428328.92846268666603.862660885
2428968.24345702665989.1368562132429143.01377678665918.168166131
#Sta/Elev= 30
       0 1649.31    51.5 1645.42    84.7 1638.53   142.9 1638.16   186.5 1630.58
   386.4 1614.93   397.3 1610.57   431.8 1585.24   457.3 1578.68   478.1 1581.29
   814.6 1578.66   830.7 1581.04  847.321574.977     859 1571.72   945.5 1569.97
  959.181576.902   969.3 1581.14  1147.5 1579.37  1164.5 1581.88  1199.5  1595.9
    1272 1633.81  1275.2 1637.29  1285.5 1657.98  1298.4 1669.47  1311.4 1699.15
  1315.7 1704.25  1335.6 1713.82  1350.2 1727.17  1433.8 1781.33  1471.4 1797.33
#Mann= 8 ,-1 , 0
       0     .05       0   59.32     .06       0  171.54     .05       0
  395.97      .1       0  516.72     .05       0  847.32    .045       0
  959.18     .05       0  967.48      .1       0
Bank Sta=847.32,959.18
XS Rating Curve= 0 ,0
Exp/Cntr=0.3,0.1

Type RM Length L Ch R = 1 ,58488   ,481.9,491.9,506.5
XS GIS Cut Line= 3
2428167.23652884667208.938550457 2428474.7844702666979.511187792
2429194.86833185666470.263518631
#Sta/Elev= 30
       0 1665.24    36.9  1660.5    75.4 1651.62   130.5 1650.84   164.1 1646.73
   218.3 1631.82   248.9 1628.07   317.8 1627.49   343.7 1630.23   403.2 1622.52
   457.1 1593.09   481.8 1589.64   507.5 1576.31   530.6 1572.32   555.1 1575.09
     648 1578.06   772.7 1575.79   943.7 1576.33   958.1 1581.08   986.8 1571.31
 1038.181570.001  1058.5 1567.58  1118.5 1567.59 1129.971572.059  1147.5 1583.68
  1187.1 1618.24  1202.2 1640.87  1222.1 1658.61    1241 1682.73  1265.7 1708.57
#Mann= 13 ,-1 , 0
       0     .06       0   50.18     .05       0   65.28     .06       0
  177.26     .05       0  289.24      .1       0     401      .1       0
  471.43      .1       0  511.55     .05       0  843.21      .1       0
   909.6    .025       0  953.77     .05       0 1038.18    .045       0
 1129.97      .1       0
Bank Sta=1038.18,1129.97
XS Rating Curve= 0 ,0
Exp/Cntr=0.3,0.1

Type RM Length L Ch R = 1 ,57997   ,471.4,468,461.3
XS GIS Cut Line= 3
2428177.03178486667408.7655786282428583.12677318667259.060169384
2429364.51989543666985.195887715
#Sta/Elev= 30
       0 1668.51    55.7 1657.43   116.9 1650.71   129.7 1646.59   167.9 1646.78
   180.9 1642.05   219.2 1637.98   240.6 1632.04   300.2 1631.45     377 1628.05
   457.8 1621.33   474.8 1613.91   525.7 1581.13   559.6 1569.88   611.5 1573.49
   682.5 1573.89   746.5 1576.56   949.5 1573.67   979.2 1574.05   996.1 1576.48
  1013.1 1568.09 1032.811566.832    1047    1564  1123.3 1564.01 1140.811567.946
  1160.8 1573.48  1174.2 1582.19  1208.1 1613.84  1246.2  1654.3  1260.8 1666.81
#Mann= 7 ,-1 , 0
       0      .1       0   81.71     .06       0   182.9     .05       0
   990.7      .1       0 1032.81    .045       0 1140.81      .1       0
 1184.98      .1       0
Bank Sta=1032.81,1140.81
XS Rating Curve= 0 ,0
Exp/Cntr=0.3,0.1

Type RM Length L Ch R = 1 ,57529   ,369.3,368.9,369.7
XS GIS Cut Line= 2
2428342.06295085667940.9862989632429623.27364302667358.326046959
#Sta/Elev= 30
       0 1677.78    62.3 1662.01   119.4 1629.75   145.8 1609.69   176.5  1609.5
   211.7 1600.55   273.9 1591.93   435.8 1588.68   475.3 1578.85   576.4  1570.9
   615.9 1572.34   686.2 1568.44   769.7 1573.06  1056.3  1569.2  1094.9 1575.67
 1115.591567.759  1122.7 1563.52  1134.5 1562.28    1174 1562.43 1195.561565.646
  1234.5 1564.97  1253.1 1568.78  1266.3  1575.6  1294.9 1602.53  1310.2 1623.91
  1319.2 1632.43  1334.2 1654.86    1341 1672.26  1345.4 1678.37  1407.5 1726.45
#Mann= 6 ,-1 , 0
       0      .1       0  105.51     .06       0  208.45     .05       0
 1115.59    .045       0 1195.56      .1       0 1237.83      .1       0
Bank Sta=1115.59,1195.56
XS Rating Curve= 0 ,0
Exp/Cntr=0.3,0.1

Type RM Length L Ch R = 1 ,57160   ,386.7,385.3,384.5
XS GIS Cut Line= 2
2428422.19664887668354.6396711322429791.80841094667673.572135627
#Sta/Elev= 30
       0 1712.29    40.8 1706.32      81 1692.59   130.2 1665.41   155.4 1648.62
   161.4 1642.82   174.8 1624.29   197.1 1603.52   237.4 1602.06     242 1600.77
   259.7 1589.66   268.6 1587.68   509.9 1573.82   715.4 1573.87   834.9 1569.17
   934.3 1568.62   987.6 1566.38  1122.1 1566.25  1193.7 1569.64  1226.5 1574.91
  1251.4 1573.49 1262.021566.224  1274.2 1560.75  1349.7 1560.03  1357.8 1561.96
 1365.861567.821  1376.5 1580.85  1418.8 1621.43  1461.4 1656.02  1529.6 1708.15
#Mann= 5 ,-1 , 0
       0      .1       0  197.06     .06       0  301.04     .05       0
 1262.02    .045       0 1365.86      .1       0
Bank Sta=1262.02,1365.86
XS Rating Curve= 0 ,0
Exp/Cntr=0.3,0.1

Type RM Length L Ch R = 1 ,56774   ,378.3,378.6,379
XS GIS Cut Line= 2
2428598.70974728668713.4214338812430038.66520068667977.060373798
#Sta/Elev= 30
       0    1709    37.6 1685.75   121.3 1627.95   161.8 1604.92   174.3 1595.52
     210 1592.93   230.8    1585   299.2 1573.18   399.9 1571.12   593.4 1571.56
   652.9 1569.45   772.8 1570.78   875.8 1567.91   997.4 1566.94  1158.2 1568.48
  1177.1 1563.99  1199.6 1562.41 1241.941565.143    1258 1561.89  1280.1 1560.01
  1352.3    1560  1361.3 1560.74  1365.8 1562.62 1369.731565.806  1416.8 1609.18
    1447 1633.84  1467.4 1647.35  1487.1 1662.91  1544.7 1704.45  1617.3 1759.46
#Mann= 5 ,-1 , 0
       0      .1       0   75.02     .06       0  283.72     .05       0
 1241.94    .045       0 1369.73      .1       0
Bank Sta=1241.94,1369.73
XS Rating Curve= 0 ,0
Exp/Cntr=0.3,0.1

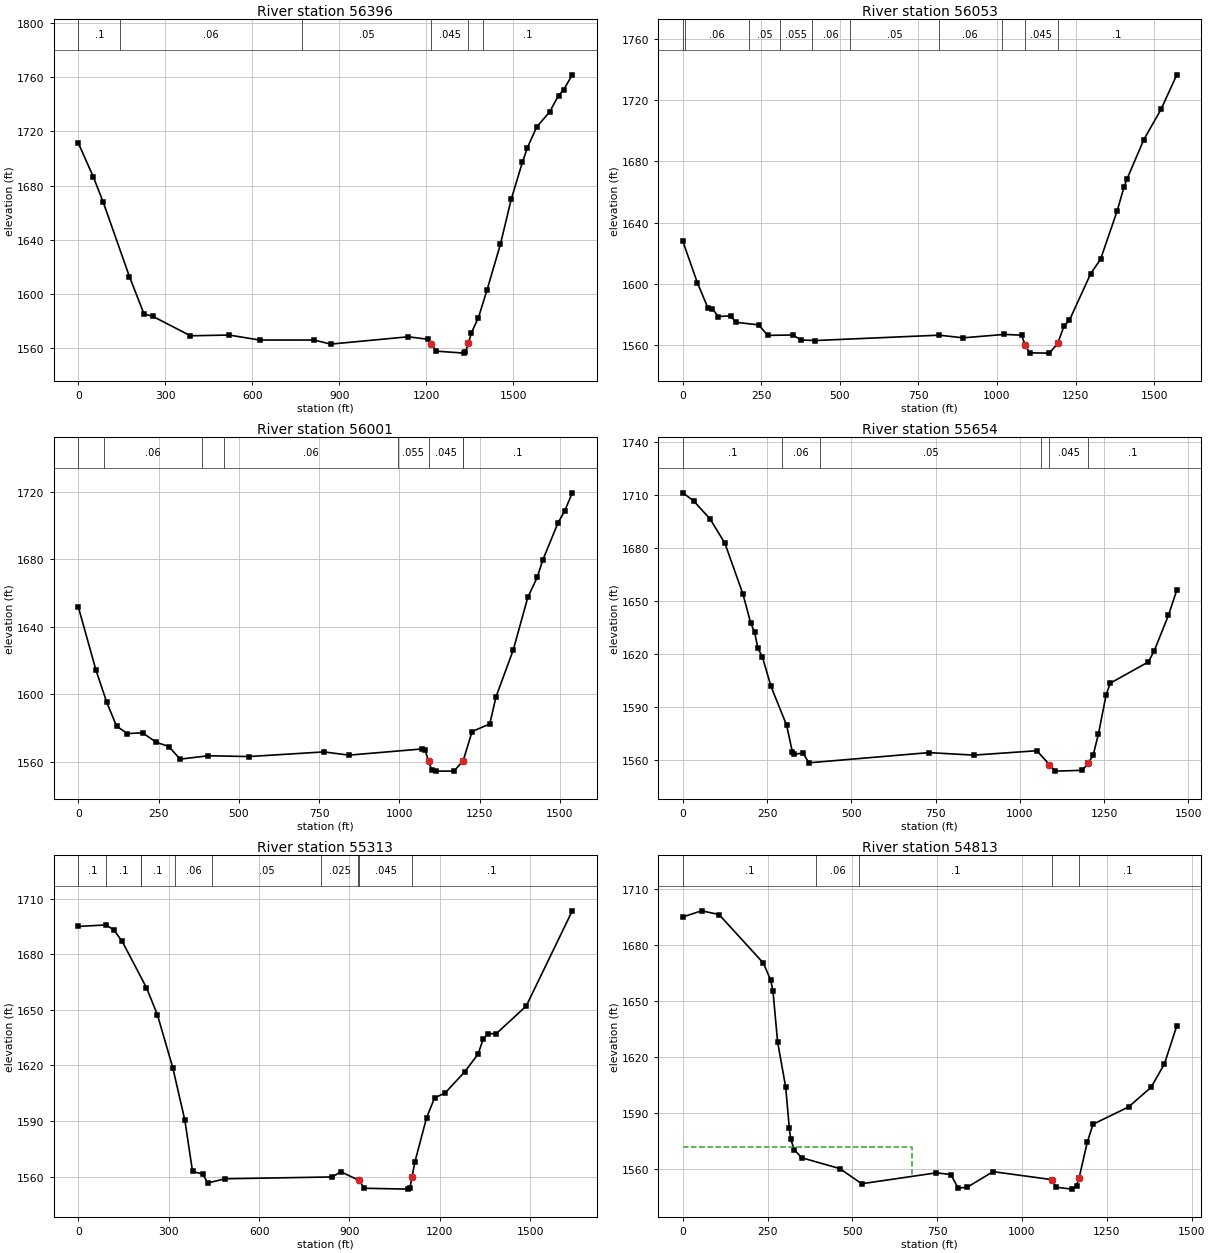
Type RM Length L Ch R = 1 ,56396   ,338.1,342.8,349.6
XS GIS Cut Line= 3
2428784.46298468669037.627150297 2429938.3425667668453.498725384
 2430304.2017431668269.549290121
#Sta/Elev= 30
       0 1711.61    51.9 1686.52    85.8 1668.05   176.4 1613.01   226.7 1585.43
   256.7 1583.72   386.9 1569.36   519.7  1569.9   625.7 1566.21   813.3 1566.22
   869.9 1563.21  1136.8 1568.61  1204.1 1566.83 1217.471563.631    1233 1558.05
  1329.6 1556.57  1334.1 1557.31 1344.991563.935  1355.1  1571.6  1379.3 1582.73
  1408.8 1603.02  1454.9 1636.67  1492.2 1669.84  1530.6 1697.12  1548.4 1708.15
  1580.3 1723.35  1625.1 1734.52  1655.3 1746.49  1673.1 1750.76  1702.8 1761.74
#Mann= 6 ,-1 , 0
       0      .1       0  145.39     .06       0  770.69     .05       0
 1217.47    .045       0 1344.99      .1       0  1395.9      .1       0
Bank Sta=1217.47,1344.99
XS Rating Curve= 0 ,0
Exp/Cntr=0.5,0.3

Type RM Length L Ch R = 1 ,56053   ,54.4,51.7,50
XS GIS Cut Line= 2
2429030.55337179669119.7319729632430517.91883537668610.015800789
#Sta/Elev= 30
       0 1627.89    46.7 1600.52    80.5    1584    93.2 1583.71   113.6 1578.52
     152 1578.97   169.3 1574.73   241.2 1573.05   270.8 1566.16   350.4 1566.43
   376.5 1563.15   422.1 1562.81   815.9 1566.31   892.4 1564.57  1023.5 1566.81
  1078.4  1566.3 1089.421559.962  1103.8 1554.74  1167.2 1554.56 1193.18 1560.92
  1213.2 1572.15  1230.7  1576.1  1298.1 1606.48  1329.8 1616.05  1382.9 1647.82
    1404  1663.1  1414.2 1668.66  1467.4 1694.28  1522.4 1714.17  1572.3 1736.67
#Mann= 10 ,-1 , 0
       0      .1       0    8.21     .06       0  209.73     .05       0
  310.49    .055       0  411.24     .06       0  533.44     .05       0
  814.28     .06       0  1015.8    .055       0 1089.42    .045       0
 1193.18      .1       0
#XS Ineff= 2 ,-1
       0 1069.42  1565.5 1213.18 1572.28  1565.5
Permanent Ineff=
       F       F
Bank Sta=1089.42,1193.18
XS Rating Curve= 0 ,0
Exp/Cntr=0.5,0.3

Type RM Length L Ch R = 1 ,56001   ,357,347.6,337.1
XS GIS Cut Line= 2
2429076.67631102 669220.310840042430504.31157911668646.257526204
#Sta/Elev= 30
       0 1651.93      55 1614.45    88.5 1595.44   119.5 1581.13   153.1  1576.8
   200.5 1577.22   243.7 1571.56   282.5 1569.13     317 1561.65   405.5 1563.66
   531.6 1563.19   765.3 1565.94   842.9 1564.03  1071.4 1567.69    1080 1567.33
  1091.11560.324  1100.4 1555.48  1114.5 1554.56  1170.6 1554.59 1199.011560.802
  1226.6 1577.96  1281.8 1582.54  1301.1 1598.53  1354.8 1626.26    1400 1657.34
  1429.8 1669.41  1446.5 1679.37  1493.9 1701.35  1515.6 1708.81  1538.7 1719.29
#Mann= 8 ,-1 , 0
       0      .1       0   79.93     .06       0  385.35     .05       0
  452.43     .06       0  996.18    .055       0  1091.1    .045       0
 1199.01     .05       0 1199.79      .1       0
Bank Sta=1091.1,1199.01
XS Rating Curve= 0 ,0
Exp/Cntr=0.5,0.3

Type RM Length L Ch R = 1 ,55654   ,394.2,340.6,337.8
XS GIS Cut Line= 3
2429372.17342344669737.2766696212430100.93804201669228.166795462
 2430587.7369372 668919.15986754
#Sta/Elev= 30
       0 1711.37    32.1 1706.86    81.2 1696.53   125.1  1682.8   178.8 1653.94
   201.8  1637.5     213 1632.71   222.7 1623.48   236.2 1618.56   261.7 1601.83
   308.1 1579.85   325.2 1564.74   330.1 1563.38   356.9 1564.06   374.1 1558.54
   730.6 1564.32   863.3  1562.9  1050.6 1565.39 1087.811557.499  1104.3 1553.84
  1184.9 1554.29 1203.131558.219    1218 1563.23  1233.2 1574.91  1255.9 1596.92
    1268 1603.61    1381 1615.61  1398.1 1621.67  1440.7 1641.97  1465.6 1656.27
#Mann= 6 ,-1 , 0
       0      .1       0  295.59     .06       0  405.84     .05       0
 1063.76      .1       0 1087.81    .045       0 1203.13      .1       0
Bank Sta=1087.81,1203.13
XS Rating Curve= 0 ,0
Exp/Cntr=0.3,0.1

Type RM Length L Ch R = 1 ,55313   ,530.5,499.8,497.6
XS GIS Cut Line= 4
2429622.03906545670123.2867243742429877.09301728669919.054193214
2430498.91132745669312.7230567932430846.28530461669036.190145299
#Sta/Elev= 30
       0 1694.99    93.1 1695.82   118.8 1692.95   145.9  1686.9   226.4 1661.96
   262.6 1647.38   313.5 1618.89   353.5 1590.69   379.3 1562.82   412.9 1561.47
   429.6 1556.63   487.4 1558.89     843 1559.88     871 1562.71  932.311557.983
   949.2 1553.78  1094.7 1553.31  1100.5 1553.85  1107.61559.961  1117.2 1568.05
  1155.9 1591.85  1182.3 1602.51  1217.5  1605.2    1282 1616.52  1326.6  1626.1
  1343.3 1634.12  1358.6 1637.13  1387.2 1637.18  1486.5 1652.07  1639.3 1703.42
#Mann= 10 ,-1 , 0
       0      .1       0   93.53      .1       0  206.84      .1       0
  207.61      .1       0  321.69     .06       0  442.71     .05       0
  806.75    .025       0  928.09      .1       0  932.31    .045       0
  1107.6      .1       0
Bank Sta=932.31,1107.6
XS Rating Curve= 0 ,0
Exp/Cntr=0.3,0.1

Type RM Length L Ch R = 1 ,54813   ,463.8,466.4,466.9
XS GIS Cut Line= 3
2430071.24157912670529.8777747152430208.49852243670362.808555052
 2431035.1179322669438.576807708
#Sta/Elev= 30
       0 1695.14    55.6 1698.43   106.9 1696.46   237.6 1670.44     259  1661.4
   265.9  1655.5   279.6 1628.15   303.6 1603.78   314.1  1581.9   318.1 1576.22
   328.8 1570.39   350.3 1566.14     463 1560.31   527.4  1552.2   747.6 1558.04
     790 1557.14   811.8  1549.9   837.6 1550.23   914.6 1558.68 1088.19 1554.39
  1101.2 1550.32  1146.9 1549.31  1160.6 1551.18 1168.191555.259  1192.2 1574.33
  1209.2 1584.08  1314.1 1593.35  1380.6 1603.91  1419.6 1616.34  1456.2 1636.77
#Mann= 5 ,-1 , 0
       0      .1       0  392.14     .06       0   519.9      .1       0
 1088.19    .045       0 1168.19      .1       0
#XS Ineff= 2 , 0
          676.81 1571.83
Permanent Ineff=
       F       F
Bank Sta=1088.19,1168.19
XS Rating Curve= 0 ,0
Exp/Cntr=0.3,0.1

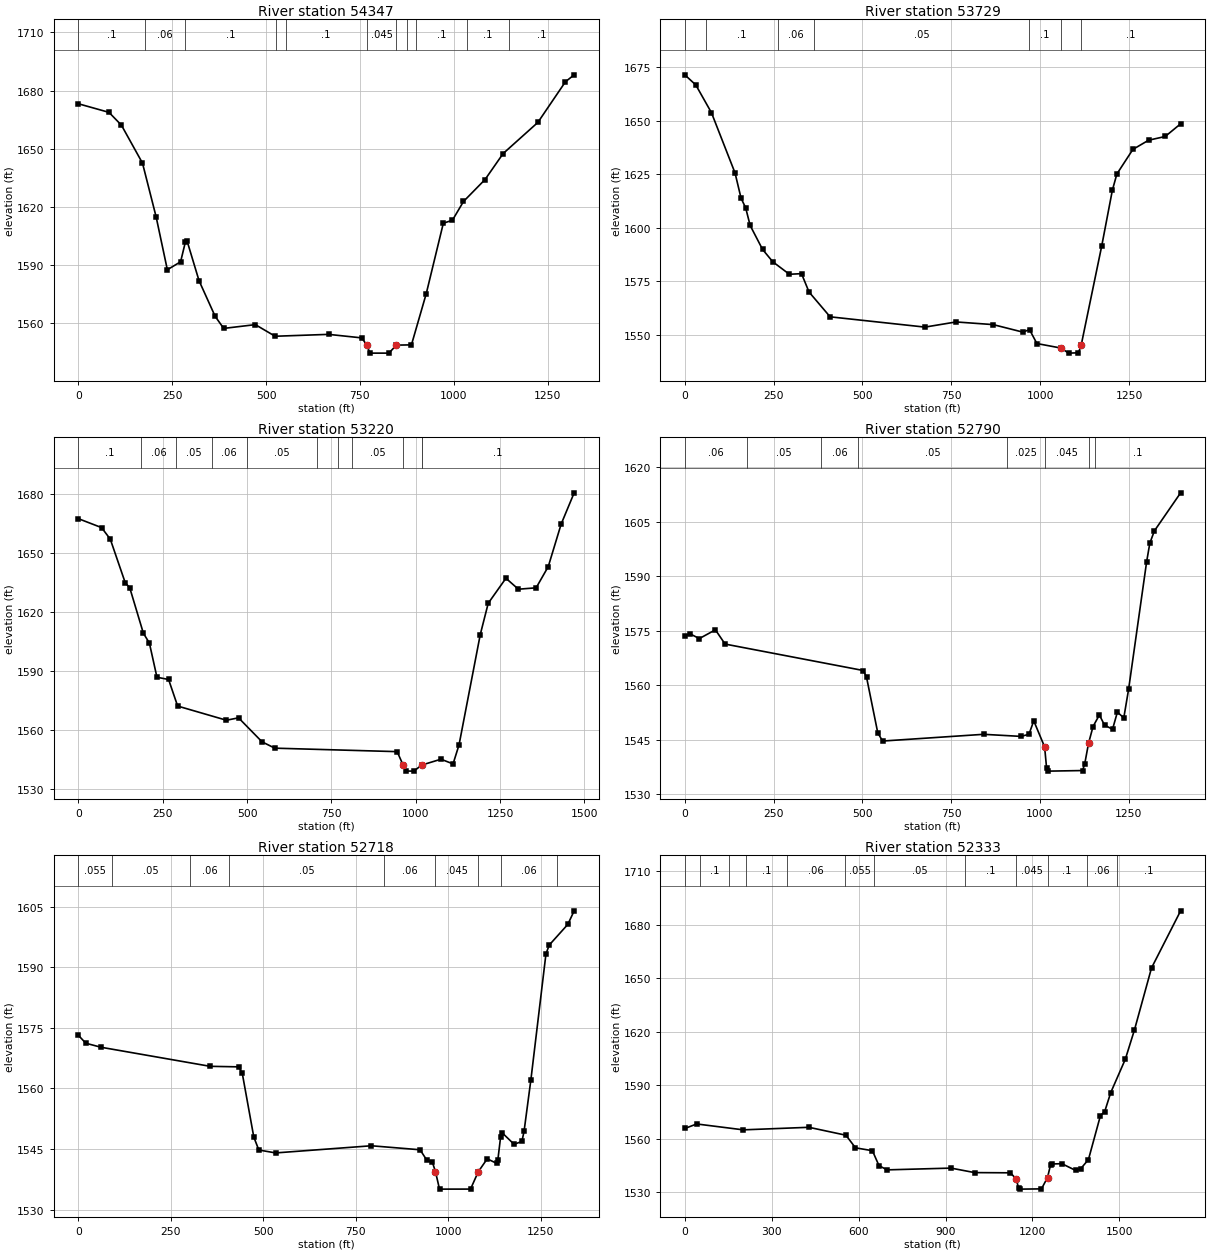
Type RM Length L Ch R = 1 ,54347   ,606.9,618.3,631.3
XS GIS Cut Line= 4
2430513.73117968670545.7025462092430781.24311185670376.395798206
2431041.61759111670111.4796613752431478.72400036669654.088187709
#Sta/Elev= 30
       0 1673.17    81.7 1668.73   114.8 1662.12   170.9 1642.56   207.2 1614.88
   237.1  1587.6   272.4 1591.71   285.2 1601.96   289.8 1602.35   321.5 1581.97
   364.4  1563.6   387.2 1557.36   471.5 1559.31   524.2 1553.32   666.6 1554.29
   755.2 1552.47  767.621548.936     777 1544.62   827.2 1544.62   847.21548.744
   887.3 1548.88   926.8 1575.34   972.2 1611.58   996.5 1613.14  1025.9 1622.79
  1083.4 1634.12  1131.5  1647.5    1224 1663.54  1297.5 1684.51  1320.7 1688.08
#Mann= 11 ,-1 , 0
       0      .1       0  176.88     .06       0  284.87      .1       0
  526.81     .05       0  552.54      .1       0  767.62    .045       0
   847.2      .1       0  875.72      .1       0  898.63      .1       0
 1036.06      .1       0 1147.64      .1       0
Bank Sta=767.62,847.2
XS Rating Curve= 0 ,0
Exp/Cntr=0.3,0.1

Type RM Length L Ch R = 1 ,53729   ,512.3,508.9,505.7
XS GIS Cut Line= 2
2430557.54244378670789.4858512882431871.65005177670320.207590371
#Sta/Elev= 30
       0 1671.35      31 1666.61      75 1653.66   141.4 1625.49   158.4 1613.66
   171.2 1609.26   183.9 1600.97   218.9 1589.75   247.6    1584   294.3 1578.15
   328.5 1578.45   349.6 1569.87     409 1558.27   675.9 1553.47   763.5 1555.88
   867.7 1554.64   951.3 1551.13   970.1  1552.3   990.9 1545.79 1058.781543.675
  1080.1 1541.31  1107.8 1541.46 1115.511545.021  1173.6  1591.6  1203.3 1617.43
    1216 1625.02  1261.1 1636.51  1305.2 1640.79    1352 1642.54  1395.4 1648.46
#Mann= 7 ,-1 , 0
       0     .05       0   60.12      .1       0   262.1     .06       0
  363.08     .05       0  969.02      .1       0 1058.78    .045       0
 1115.51      .1       0
Bank Sta=1058.78,1115.51
XS Rating Curve= 0 ,0
Exp/Cntr=0.3,0.1

Type RM Length L Ch R = 1 ,53220   ,428.8,429.9,435.7
XS GIS Cut Line= 2
 2430830.5730657671353.8361005492432143.42411453670693.549035296
#Sta/Elev= 30
       0 1667.63    68.9 1663.07    94.7 1657.19     139 1635.01   152.4 1632.43
   192.7 1609.33   210.6 1604.28     233 1586.89   267.5 1585.75   294.3 1572.22
     439    1565   474.8 1566.23   544.5    1554   582.3 1550.78   944.9 1549.01
  962.391542.254   971.8 1539.14   994.7 1539.09 1017.091542.142  1074.8 1545.16
  1110.6 1542.76  1128.3 1552.46  1191.2 1608.61  1214.8 1624.55  1267.3 1637.29
  1304.2 1631.71  1356.8 1632.42  1392.7 1643.21  1430.9 1664.84  1469.5 1680.78
#Mann= 11 ,-1 , 0
       0      .1       0   186.5     .06       0  290.63     .05       0
  394.76     .06       0  498.89     .05       0  707.15     .06       0
  770.72    .025       0  811.28     .05       0  962.39    .045       0
 1017.09     .05       0 1019.54      .1       0
Bank Sta=962.39,1017.09
XS Rating Curve= 0 ,0
Exp/Cntr=0.5,0.3

Type RM Length L Ch R = 1 ,52790   ,71.4,71.4,70
XS GIS Cut Line= 2
2431010.58714136671764.7627721282432244.09353259671110.976350039
#Sta/Elev= 30
       0 1573.45    13.8 1574.21    40.9 1572.85    86.2 1575.26   113.4 1571.34
   502.7 1564.07   511.7 1562.24   543.4 1546.92     557 1544.68   841.1 1546.53
   946.3 1545.96     969 1546.53   982.6 1550.23 1013.141543.072  1018.8 1537.14
  1023.3 1536.41  1119.9 1536.57  1125.9 1538.31 1136.791544.053  1149.5 1548.67
  1167.3 1551.86  1181.8 1549.06  1204.4 1547.92    1218 1552.62  1236.1 1551.07
  1249.7 1558.96  1300.4 1593.98  1309.3 1599.04  1322.1 1602.44  1396.1 1612.92
#Mann= 8 ,-1 , 0
       0     .06       0  174.49     .05       0  384.21     .06       0
  489.07     .05       0  908.52    .025       0 1013.14    .045       0
 1136.79    .055       0 1154.24      .1       0
#XS Ineff= 2 ,-1
       0     993 1544.82 1156.81 1396.06 1544.82
Permanent Ineff=
       F       F
Bank Sta=1013.14,1136.79
XS Rating Curve= 0 ,0
Exp/Cntr=0.5,0.3

Type RM Length L Ch R = 1 ,52718   ,385,385.5,385.6
XS GIS Cut Line= 2
2431096.74674594671805.2193841342432277.85658845671170.553986788
#Sta/Elev= 30
       0 1573.16    20.4 1571.19    61.3  1570.2   356.5 1565.48   433.7 1565.35
   443.3 1563.76   474.5 1547.97   488.1 1544.77   533.6 1544.05   792.4 1545.82
   924.1 1544.83   942.9 1542.18   957.3 1541.76  965.72 1539.43   976.7 1535.09
  1060.6  1535.1 1081.44 1539.38  1105.7 1542.59  1131.5 1541.46  1134.5 1542.36
    1142 1548.07  1145.8 1549.06  1178.4 1546.18  1199.5 1546.89  1205.4 1549.44
  1223.8 1562.16  1264.6 1593.35  1273.7 1595.52  1323.7 1600.61  1340.8 1603.96
#Mann= 9 ,-1 , 0
       0    .055       0   91.71     .05       0  301.84     .06       0
   406.9     .05       0  827.16     .06       0  965.72    .045       0
 1081.44    .055       0 1142.36     .06       0 1295.58      .1       0
Bank Sta=965.72,1081.44
XS Rating Curve= 0 ,0
Exp/Cntr=0.5,0.3

Type RM Length L Ch R = 1 ,52333   ,417.4,416,414.2
XS GIS Cut Line= 3
2431074.90558228672082.6679762152431650.17313251671940.032106623
 2432639.5891327671417.763466135
#Sta/Elev= 30
       0 1565.75      41 1568.29   201.8 1564.99   428.4 1566.42   556.2 1561.98
   589.2 1554.91   647.6 1553.31   670.2 1544.97     698 1542.57     919 1543.56
  1000.4 1541.04  1123.9 1540.92 1144.091537.443  1152.1 1532.38  1158.7 1531.78
  1231.1 1531.92 1251.981538.245  1262.7 1545.51    1266 1545.86  1301.5 1546.04
  1348.7 1542.29  1366.8 1543.25  1393.3 1548.35  1434.7 1572.95  1449.5 1575.26
  1470.2 1585.84  1520.6 1604.56  1552.2 1621.02    1611 1655.69  1711.5  1687.7
#Mann= 12 ,-1 , 0
       0    .055       0   53.52      .1       0  153.17     .05       0
  211.76      .1       0  352.48     .06       0  551.78    .055       0
  654.47     .05       0  968.87      .1       0 1144.09    .045       0
 1251.98      .1       0 1388.08     .06       0 1492.88      .1       0
Bank Sta=1144.09,1251.98
XS Rating Curve= 0 ,0
Exp/Cntr=0.3,0.1

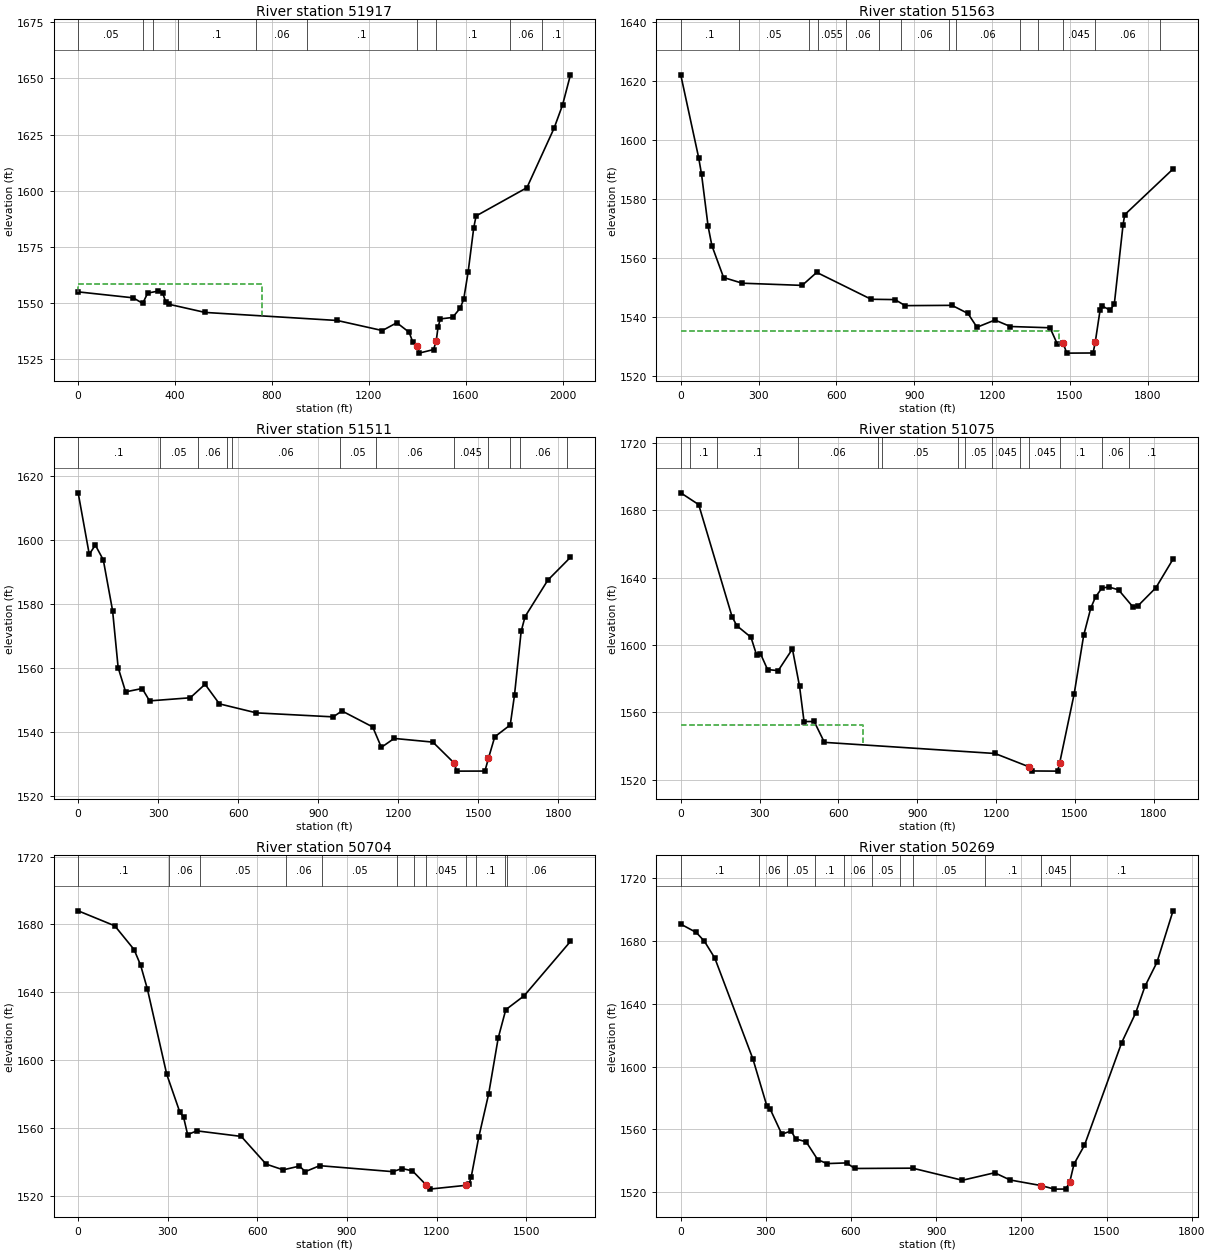
Type RM Length L Ch R = 1 ,51917   ,358.8,353.6,353
XS GIS Cut Line= 4
2431146.70793211672743.6056307112432163.35320851 672147.98575896
2432601.43730611671898.9593541322432801.40836287671611.363800704
#Sta/Elev= 30
       0 1554.96   227.2 1552.31   266.6 1549.84     287 1554.42     328 1555.26
   348.4 1554.56   361.6 1550.52   373.3 1549.48   523.9 1545.81  1069.7 1542.22
  1255.8 1537.74  1315.6 1541.21  1366.4 1536.99    1381 1532.77 1397.631531.074
  1407.6 1527.69  1467.4 1529.28 1478.221533.121  1485.8 1539.17  1495.1 1542.92
  1545.7 1543.57  1577.1 1547.69  1591.7 1551.66  1609.9 1563.68  1633.3 1583.55
  1642.8 1588.76  1852.8 1601.35  1964.8  1627.8  1999.8 1638.14  2032.5 1651.59
#Mann= 10 ,-1 , 0
       0     .05       0  266.18     .06       0   307.6    .055       0
  414.09      .1       0  733.57     .06       0  946.56      .1       0
 1397.63    .045       0 1478.22      .1       0 1781.18     .06       0
 1915.97      .1       0
#XS Ineff= 2 , 0
          757.49 1558.52
Permanent Ineff=
       F       F
Bank Sta=1397.63,1478.22
XS Rating Curve= 0 ,0
Exp/Cntr=0.5,0.3

Type RM Length L Ch R = 1 ,51563   ,52.9,52.8,52.4
XS GIS Cut Line= 2
2431197.16714877673113.3755604622432841.70126128672165.849568382
#Sta/Elev= 30
       0  1622.1    69.1 1593.98    80.3 1588.32   105.5  1570.7   120.1 1564.16
   165.2 1553.34   237.2 1551.41   468.1 1550.67   524.3 1555.08   734.1 1545.96
     826 1545.85   865.1  1543.8  1045.7  1543.9  1107.2 1541.15  1142.1 1536.47
  1211.3 1538.92  1270.9 1536.72  1423.7 1536.29  1451.4 1530.86 1474.421531.009
  1488.3 1527.69  1589.9 1527.74 1598.291531.525  1616.8 1542.35  1622.2 1543.79
  1654.9 1542.29  1671.5 1544.28  1705.3 1571.23  1711.6 1574.64    1898 1590.15
#Mann= 14 ,-1 , 0
       0      .1       0  223.93     .05       0  494.66     .06       0
  529.16    .055       0  635.36     .06       0  765.38      .1       0
  847.75     .06       0 1036.11    .055       0 1060.14     .06       0
 1306.83      .1       0 1378.74     .06       0 1474.42    .045       0
 1598.29     .06       0 1848.28      .1       0
#XS Ineff= 2 ,-1
       0    1457 1535.22 1606.29 1897.96 1535.22
Permanent Ineff=
       F       F
Bank Sta=1474.42,1598.29
XS Rating Curve= 0 ,0
Exp/Cntr=0.5,0.3

Type RM Length L Ch R = 1 ,51511   ,432.2,435.4,438.3
XS GIS Cut Line= 2
2431274.99802986673131.9946177152432872.27337861672208.013197958
#Sta/Elev= 30
       0 1614.69    41.6 1595.48    64.4 1598.35    94.3 1593.71   129.1 1577.83
   149.9 1560.04   177.9 1552.47     240 1553.52   267.7 1549.65   420.2 1550.62
   475.7 1554.84   529.4 1548.72   668.1  1545.9   956.3 1544.65   988.6 1546.51
  1104.1  1541.5  1136.5 1535.12  1184.5 1537.91  1329.7 1536.76 1409.911530.166
  1418.4 1527.69  1524.7 1527.71 1537.731531.642  1561.6 1538.42  1619.6 1542.12
  1635.6  1551.5  1660.5 1571.38  1675.2    1576  1760.3 1587.37  1845.3 1594.53
#Mann= 12 ,-1 , 0
       0      .1       0  306.79     .05       0  450.49     .06       0
  556.76     .05       0  576.31     .06       0  981.83     .05       0
 1115.35     .06       0 1409.91    .045       0 1537.73     .06       0
 1619.43      .1       0 1654.39     .06       0 1831.97      .1       0
Bank Sta=1409.91,1537.73
XS Rating Curve= 0 ,0
Exp/Cntr=0.5,0.5

Type RM Length L Ch R = 1 ,51075   ,368,371.3,374.5
XS GIS Cut Line= 2
2431513.38797301673422.3257299662433176.76555178672559.342547789
#Sta/Elev= 30
       0 1690.31    68.3 1683.31   195.3  1616.8   213.3 1611.44   267.4 1604.54
   288.4 1594.19   303.5 1594.82   330.5 1585.38     371 1584.75   425.1 1597.61
   452.2 1575.43   469.4 1554.48   507.9 1554.56   546.8 1542.16  1196.3 1535.55
 1326.531527.581  1335.7 1525.18  1434.5 1525.08  1442.4 1529.95  1497.6 1570.97
  1533.7 1605.67  1560.7 1621.84    1579 1628.53  1602.8 1633.68  1628.3 1634.45
  1666.4 1632.72  1721.4 1622.54  1739.2 1623.03  1808.6 1633.95  1873.9 1650.94
#Mann= 14 ,-1 , 0
       0    .055       0   35.31      .1       0  139.17      .1       0
  445.14     .06       0  751.11      .1       0  767.18     .05       0
 1057.08      .1       0 1080.84     .05       0 1185.39    .045       0
 1289.95      .1       0 1326.53    .045       0  1442.4      .1       0
 1603.61     .06       0 1708.16      .1       0
#XS Ineff= 2 , 0
          693.05 1552.56
Permanent Ineff=
       F       F
Bank Sta=1326.53,1442.4
XS Rating Curve= 0 ,0
Exp/Cntr=0.3,0.1

Type RM Length L Ch R = 1 ,50704   ,424.1,434.8,441.9
XS GIS Cut Line= 3
2431783.69550326673617.6783576312432811.11864528673161.131698549
 2433287.7686106 672943.11146529
#Sta/Elev= 30
       0 1688.05   122.6  1679.2   187.2  1665.2   209.1 1655.99   231.7 1641.97
   296.6 1591.59   340.4 1569.26   352.9 1566.32   366.6 1555.96   397.3  1558.2
   546.1 1554.92   629.3 1538.57   686.5 1535.19     741  1537.4   760.6 1534.13
   808.7 1537.65  1053.8 1534.12  1084.5 1535.97  1119.5 1534.56    11641526.515
  1176.7 1523.81 1299.011526.064  1308.6  1526.7  1315.8 1530.69  1341.2 1554.35
  1374.6 1580.08  1406.4 1612.91  1431.8 1629.69  1493.4 1637.93  1648.4 1669.99
#Mann= 12 ,-1 , 0
       0      .1       0  304.59     .06       0  407.29     .05       0
  694.99     .06       0   818.1     .05       0 1068.75    .025       0
  1126.2      .1       0    1164    .045       0 1299.01      .1       0
  1332.2      .1       0 1430.27      .1       0  1435.2     .06       0
Bank Sta=1164,1299.01
XS Rating Curve= 0 ,0
Exp/Cntr=0.3,0.1

Type RM Length L Ch R = 1 ,50269   ,641.7,678.4,716.9
XS GIS Cut Line= 3
 2431824.9191741673752.9041370452432660.90962809673592.772239462
2433523.42726001673402.683380798
#Sta/Elev= 30
       0 1690.63    54.8 1685.31    83.3 1679.73     120 1669.02   254.4 1604.74
   303.2 1575.03   315.5 1572.74   356.2 1556.88   388.8 1559.02   405.1 1553.89
   441.7 1552.11   482.4 1540.76     515 1538.22   584.3 1538.66   612.8 1535.11
   816.8 1535.31   992.3 1527.61    1106 1532.39  1160.3 1527.79 1270.821524.194
  1315.9 1521.97  1356.9 1522.02 1370.731526.671  1385.5 1537.93  1422.4 1549.92
  1553.5 1615.21  1602.8 1634.11  1635.4    1651  1677.7 1666.32  1734.4 1699.08
#Mann= 11 ,-1 , 0
       0      .1       0  275.62     .06       0  374.97     .05       0
  474.33      .1       0  573.69     .06       0  673.04     .05       0
   772.4      .1       0  817.43     .05       0 1070.73      .1       0
 1270.82    .045       0 1370.73      .1       0
Bank Sta=1270.82,1370.73
XS Rating Curve= 0 ,0
Exp/Cntr=0.3,0.1