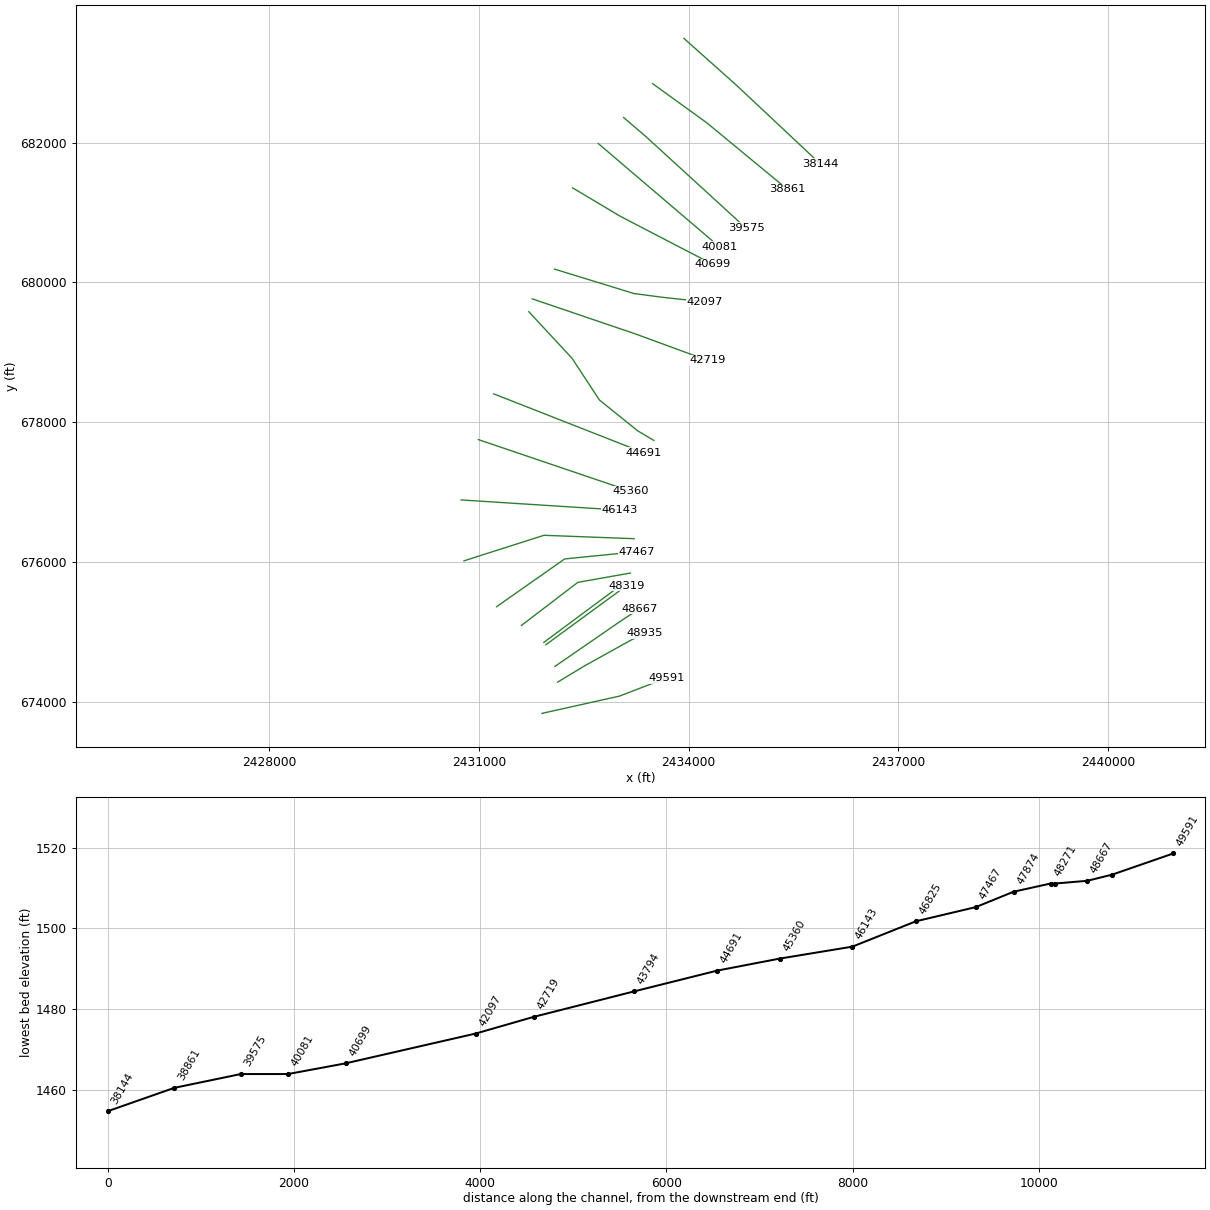
HEC-RAS study NFSBPOTOMC.prj: NFSBPOTOMC

--- NFSBPOTOMC.g01 (geometry) --- (continued)

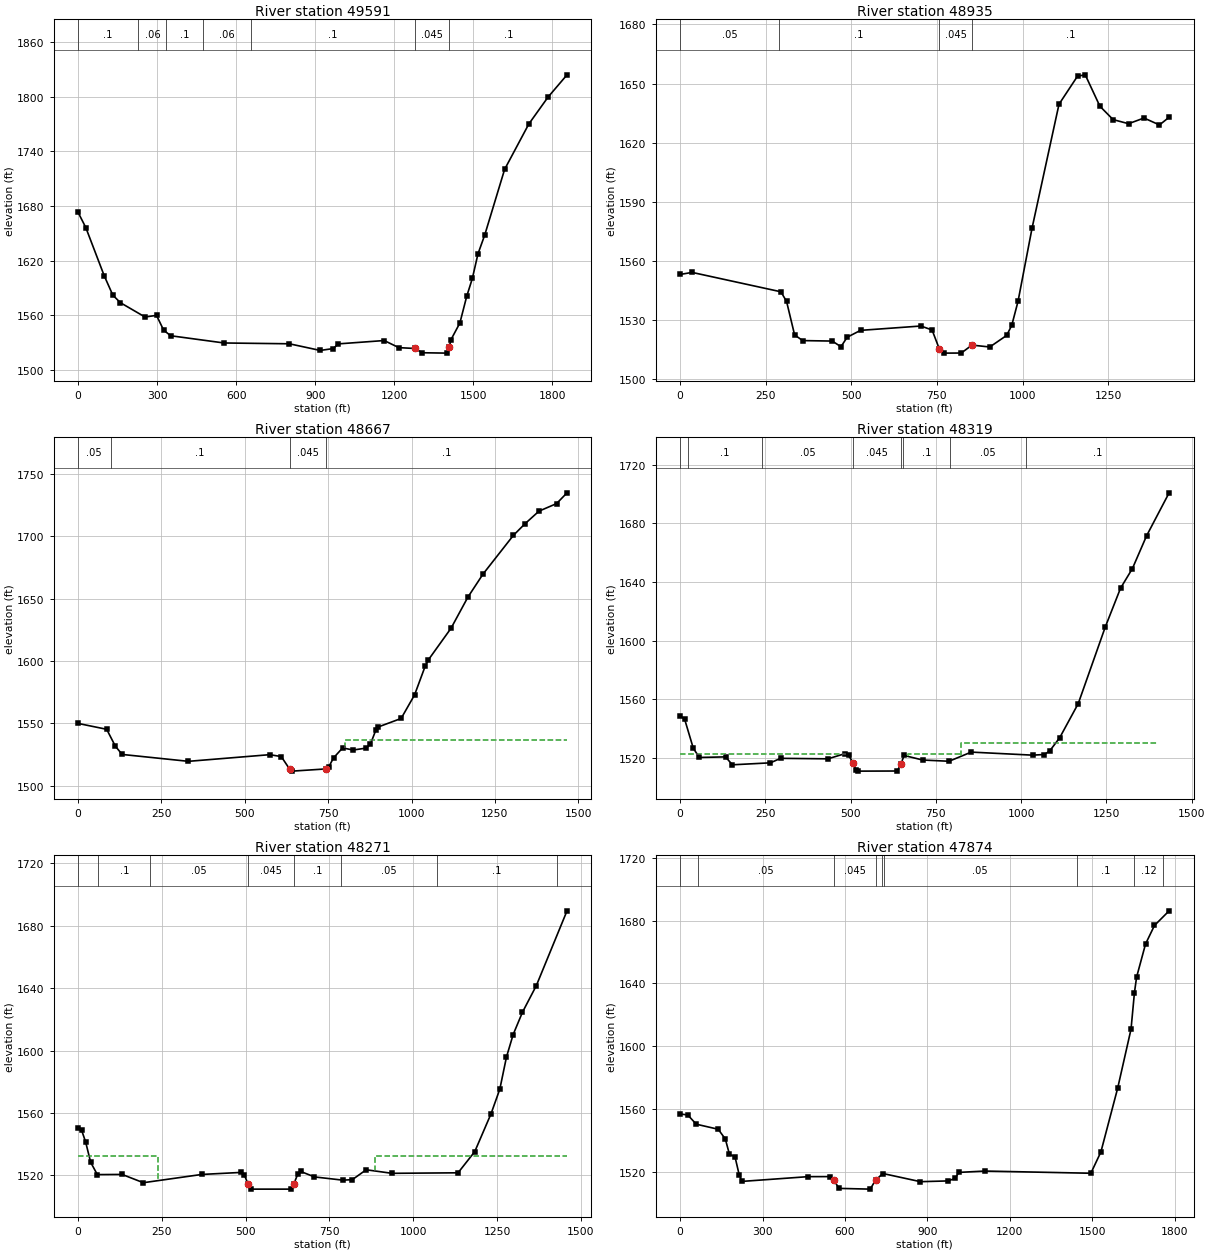
Type RM Length L Ch R = 1 ,49591   ,644.8,656.1,667.5
XS GIS Cut Line= 3
2431901.76974219673832.2763536272433013.31509128674080.273561046
2433681.94925269674338.483018383
#Sta/Elev= 30
       0 1673.35    29.7  1656.4    99.4 1603.61   132.1 1582.29   160.8 1573.99
   254.3 1558.26   297.9 1560.05   324.9 1543.88   351.5 1537.68   554.3 1529.73
   801.9 1528.85     919 1521.55   968.2 1523.57   988.1 1528.75  1161.8 1532.41
  1217.6 1524.61 1278.251523.698    1306    1519    1402 1518.59 1409.65 1525.62
  1414.8  1533.1  1449.1 1551.72  1474.9 1580.88  1496.3 1600.53  1517.7 1627.57
  1543.5 1648.42  1618.8 1720.34  1710.7 1770.21  1783.6  1799.7  1855.6 1824.15
#Mann= 7 ,-1 , 0
       0      .1       0  228.68     .06       0  335.64      .1       0
  475.83     .06       0  656.51      .1       0 1278.25    .045       0
 1409.65      .1       0
Bank Sta=1278.25,1409.65
XS Rating Curve= 0 ,0
Exp/Cntr=0.3,0.1

Type RM Length L Ch R = 1 ,48935   ,264.8,267.8,273.3
XS GIS Cut Line= 4
2432124.61969018 674278.620605292432515.80427527674514.989883214
2433143.91161487674863.6994876272433367.74614093674980.169727132
#Sta/Elev= 30
       0 1553.22    35.2 1554.25   294.4 1544.43   310.9 1539.53   334.3  1522.6
   357.7  1519.7   444.6 1519.45   469.6 1516.57   487.9  1521.4   526.8 1524.88
   702.9 1527.08   735.7 1525.08  756.39 1515.68     770 1513.34     821 1513.39
  852.181517.407   904.2 1516.45   953.4 1522.31   968.3 1527.39   986.6 1539.52
  1027.7 1576.77  1106.3  1639.5  1160.4 1653.73  1182.9  1654.4  1225.7 1638.48
  1264.3  1631.7  1309.4 1629.63  1354.5 1632.51  1399.6    1629  1427.8  1632.9
#Mann= 4 ,-1 , 0
       0     .05       0   289.7      .1       0  756.39    .045       0
  852.18      .1       0
Bank Sta=756.39,852.18
XS Rating Curve= 0 ,0
Exp/Cntr=0.3,0.1

Type RM Length L Ch R = 1 ,48667   ,348.2,347.8,348.2
XS GIS Cut Line= 3
2432086.26084301674503.7156275512433013.51226935675143.737969548
2433296.97987828675330.621125966
#Sta/Elev= 30
       0 1550.02      86 1545.31   111.9 1531.83   132.3 1525.17   331.1 1519.65
   574.9 1524.98   609.4 1523.47  635.261513.113   642.2  1511.8  743.13 1513.56
     752 1515.25   766.1  1522.4   793.4 1530.39     825 1528.72   864.7 1530.26
   876.8 1533.45   892.8 1544.54   899.7 1547.13   968.8 1553.98  1009.1 1572.85
  1040.7 1595.69  1050.4  1600.9  1118.5 1626.28  1168.8 1651.09  1214.4 1669.67
  1305.4 1700.67  1340.6 1710.05  1382.1 1720.05  1434.8  1726.1  1466.2 1734.73
#Mann= 4 ,-1 , 0
       0     .05       0   97.59      .1       0  635.26    .045       0
  743.13      .1       0
#XS Ineff= 2 , 0
                          801.42         1536.62
Permanent Ineff=
       F       F
Bank Sta=635.26,743.13
XS Rating Curve= 0 ,0
Exp/Cntr=0.5,0.3

Type RM Length L Ch R = 1 ,48319   ,47.8,48.4,49
XS GIS Cut Line= 2
 2431957.1256026674814.2143503732433113.66561237675661.893429294
#Sta/Elev= 30
       0 1548.66    13.1 1546.69    38.8 1526.65    56.6 1520.44   133.3 1520.83
   153.3 1515.43   264.9 1516.78   294.6 1519.84   433.5  1519.5   483.1 1523.01
   493.9 1521.81  507.271516.958   515.4  1511.7   522.2 1511.12     637  1511.2
  647.061515.829     657  1521.8   711.2 1518.69   788.6 1517.85   853.7 1524.09
  1033.6 1522.01  1068.3 1522.45  1083.8 1524.91  1112.9 1533.82  1167.5 1557.19
  1246.5 1609.23  1291.4 1635.78  1326.2 1649.18  1367.9 1671.56  1433.9 1700.82
#Mann= 8 ,-1 , 0
       0     .05       0    24.1      .1       0  240.51     .05       0
  507.27    .045       0  647.06    .055       0  653.82      .1       0
  791.59     .05       0 1015.06      .1       0
#XS Ineff= 3 ,-1
       0  485.27  1522.8  669.06     823  1522.8     823    1400    1530
Permanent Ineff=
       F       F       F
Bank Sta=507.27,647.06
XS Rating Curve= 0 ,0
Exp/Cntr=0.5,0.3

Type RM Length L Ch R = 1 ,48271   ,398.2,396.4,398.1
XS GIS Cut Line= 2
2431928.35827169674848.4754367172433099.73617828675718.097057045
#Sta/Elev= 30
       0 1550.19    10.8 1548.91    22.9 1541.28    37.8 1528.33    57.7 1520.44
   131.6 1520.54     195 1515.24   369.4 1520.54   486.6 1521.84   496.2 1520.22
  507.611514.269   516.1 1511.12   634.8 1511.12  643.511514.199   655.3 1520.61
   663.9  1522.5   705.4 1518.95   790.1 1516.88   818.3 1517.19   859.8 1523.53
   936.8 1521.26  1133.8 1521.59  1183.7 1535.21  1232.1  1559.4  1258.4 1575.25
  1278.3 1595.89  1298.2 1610.27    1326 1624.61  1367.3 1641.65  1458.9 1689.63
#Mann= 8 ,-1 , 0
       0     .05       0   60.79      .1       0   215.3     .05       0
  507.61    .045       0  643.51      .1       0  785.12     .05       0
 1070.03      .1       0 1430.16     .12       0
#XS Ineff= 2 ,-1
       0  237.88 1532.19  886.37 1458.89 1532.19
Permanent Ineff=
       F       F
Bank Sta=507.61,643.51
XS Rating Curve= 0 ,0
Exp/Cntr=0.5,0.3

Type RM Length L Ch R = 1 ,47874   ,405.6,406.8,403.9
XS GIS Cut Line= 3
 2431607.9947392675090.6658972052432414.08991176675707.029821962
2433167.20750001675840.724764541
#Sta/Elev= 30
       0 1556.93    27.8 1556.29    58.9 1550.41   138.7 1547.19   164.6    1541
   179.7 1531.23   199.8 1529.71   214.9 1518.34     225    1514   466.7 1517.04
   547.3 1517.06   559.31514.865   578.5 1509.56   691.8 1509.09  711.121514.736
   737.9 1519.03   874.6 1513.83   975.2 1514.31  1000.5 1515.88  1014.5 1519.74
  1109.6 1520.59  1494.8 1519.19  1531.3 1532.75  1592.3 1573.27    1641 1610.89
  1653.4 1634.14  1661.3 1644.04  1693.8 1665.08  1726.3 1676.87  1779.6 1686.19
#Mann= 9 ,-1 , 0
       0     .06       0    66.8     .05       0   559.3    .045       0
  711.12    .025       0  735.29      .1       0  742.11     .05       0
 1442.66      .1       0 1653.09     .12       0  1758.3      .1       0
Bank Sta=559.3,711.12
XS Rating Curve= 0 ,0
Exp/Cntr=0.3,0.1

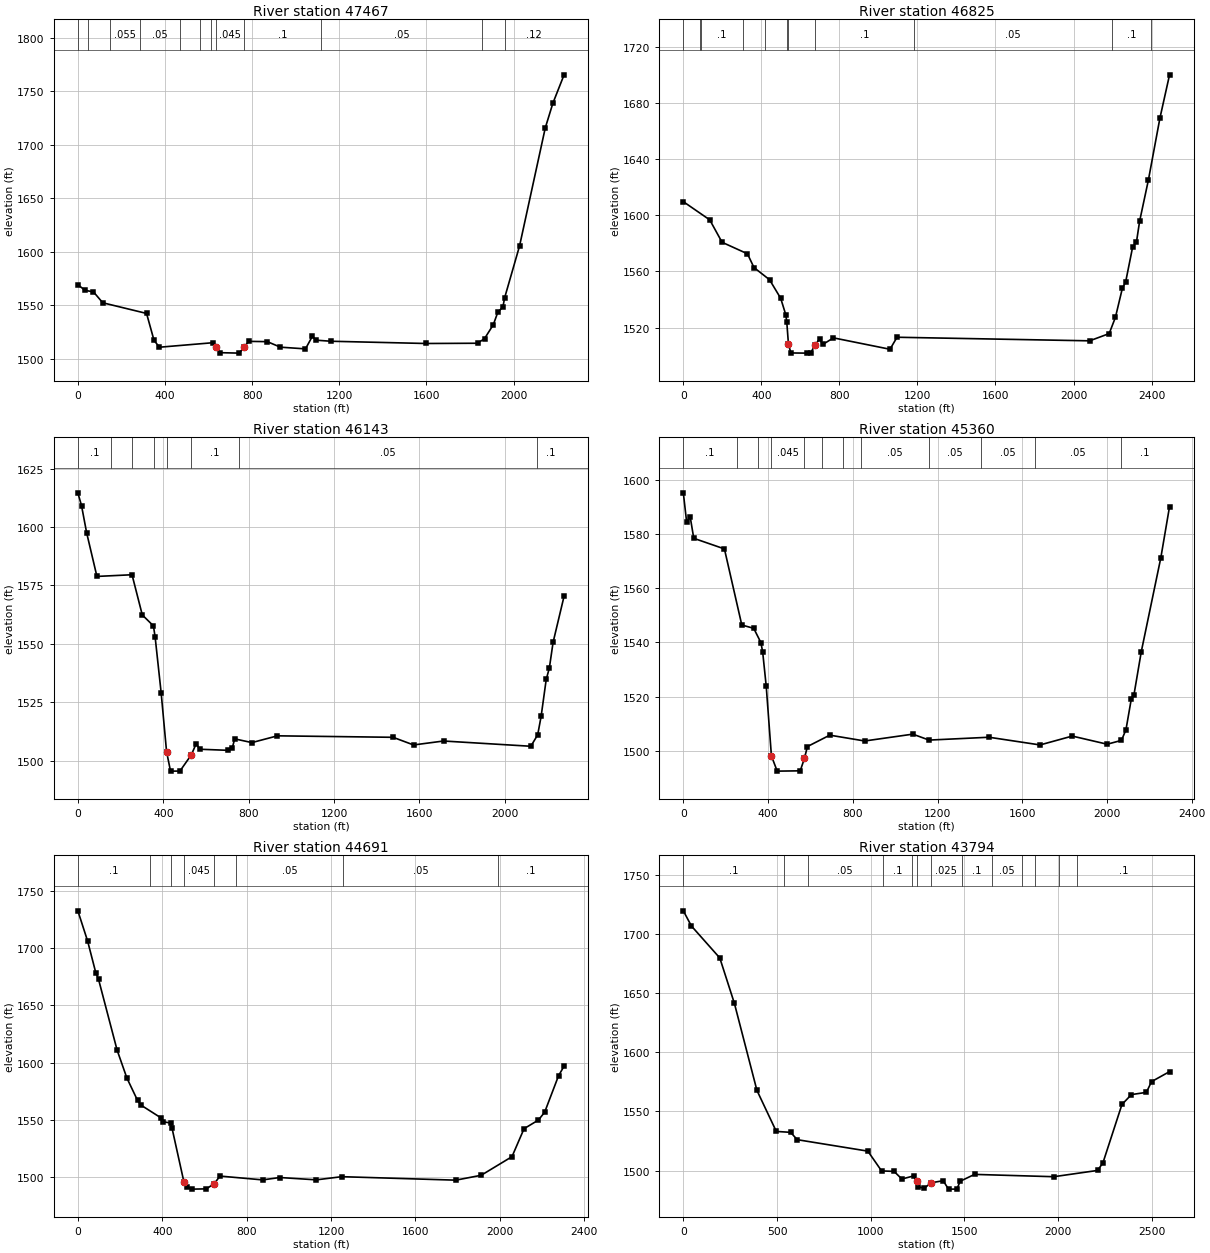
Type RM Length L Ch R = 1 ,47467   ,663.1,642.4,619.8
XS GIS Cut Line= 3
2431252.07944053675358.3818972112432226.36587778676042.571473718
2433262.11413437676146.103090793
#Sta/Elev= 30
       0 1569.32    32.6 1564.01    71.7 1562.54   114.3 1552.35   315.3 1542.39
   349.7 1517.12   374.7  1510.8   622.5 1515.05  635.211511.326   651.2  1505.7
   741.3 1505.27  763.061511.199   785.3 1516.27   869.4    1516   929.7 1510.83
  1044.6 1509.25  1076.2 1520.96  1093.4 1517.37  1161.7 1516.38  1596.9 1514.28
  1834.1 1514.51  1866.3 1518.82  1906.5  1531.8  1927.5 1543.56  1950.7 1548.44
  1958.7 1557.06  2027.1  1605.5    2145 1715.78  2179.8 1738.85  2231.4 1765.52
#Mann= 12 ,-1 , 0
       0      .1       0   48.19     .05       0  146.32    .055       0
  285.06     .05       0  470.11    .025       0  562.54     .05       0
  610.75      .1       0  635.21    .045       0  763.06      .1       0
  1117.5     .05       0 1855.88      .1       0 1958.66     .12       0
Bank Sta=635.21,763.06
XS Rating Curve= 0 ,0
Exp/Cntr=0.3,0.1

Type RM Length L Ch R = 1 ,46825   ,700.2,682.5,655
XS GIS Cut Line= 3
2430785.70996645676014.9747441262431930.08300579676380.701702967
2433220.04630512  676332.0731913
#Sta/Elev= 30
       0 1609.75   135.5 1596.76   198.5  1580.8   328.6 1572.59   362.2 1562.78
     442 1554.08     499 1540.87   525.3 1529.08   530.2 1524.05  538.831508.233
   551.3 1501.88     634 1501.76     652 1501.76  674.541507.353   698.2 1511.84
     715 1507.96   769.6 1512.64  1059.3 1504.52  1095.5 1513.08  2082.7 1510.53
  2182.8 1515.69  2214.8 1527.23  2250.8  1548.2  2266.8  1552.2  2302.8 1577.19
  2322.9 1581.13  2338.9 1595.83  2384.2 1625.39  2442.9  1669.3  2492.3 1700.18
#Mann= 11 ,-1 , 0
       0    .035       0   83.32     .06       0   92.71      .1       0
  306.12     .06       0  417.52     .05       0  528.92      .1       0
  538.83    .045       0  674.54      .1       0 1183.61     .05       0
 2198.44      .1       0 2398.58     .12       0
Bank Sta=538.83,674.54
XS Rating Curve= 0 ,0
Exp/Cntr=0.3,0.1

Type RM Length L Ch R = 1 ,46143   ,792.4,782.5,762.3
XS GIS Cut Line= 2
2430745.59128028676886.8014125382433018.11265385676741.177031875
#Sta/Elev= 30
       0 1614.68    17.2  1609.2    41.2 1597.55    89.3 1578.87   253.7 1579.59
   301.8 1562.37   353.9  1557.7   361.9 1552.95     390 1529.14  415.491503.818
     434 1495.47   478.1 1495.49  531.341502.433   554.3 1507.23   570.3 1504.85
   702.6 1504.38   722.6 1505.24   734.7 1509.29     815 1507.69   934.9 1510.59
  1476.2 1509.96  1572.4 1506.68  1712.7 1508.37  2121.5 1506.12  2153.6 1511.01
  2169.6 1518.87  2193.6 1534.74  2208.4 1539.71  2225.7 1550.62  2277.2 1570.39
#Mann= 8 ,-1 , 0
       0      .1       0  154.82    .055       0  254.61    .035       0
  354.39      .1       0  415.49    .045       0  531.34      .1       0
  753.52     .05       0 2150.46      .1       0
Bank Sta=415.49,531.34
XS Rating Curve= 0 ,0
Exp/Cntr=0.3,0.1

Type RM Length L Ch R = 1 ,45360   ,673,668.9,665.1
XS GIS Cut Line= 2
2430992.09308386677750.2340688712433165.65402544677012.680097789
#Sta/Elev= 30
       0 1595.16    15.5 1584.46    32.4 1586.28    49.3 1578.38     194 1574.47
     276  1546.4   332.3 1545.18   366.1 1539.92   374.5 1536.51   391.4 1523.77
  415.871498.107   443.1  1492.5   551.9 1492.61  571.821497.222   585.7 1501.56
   691.3 1505.77   856.1 1503.62  1083.3 1506.14  1160.2 1503.95  1443.2    1505
    1684 1502.16    1836 1505.43  2000.8 1502.43  2068.3 1503.84  2089.5 1507.76
  2114.6 1519.04  2127.5 1520.75  2161.9 1536.58  2254.2 1571.24  2295.3 1590.09
#Mann= 12 ,-1 , 0
       0      .1       0  251.06    .055       0  351.77      .1       0
  415.87    .045       0  571.82    .025       0  653.89     .05       0
  754.59     .05       0  838.35     .05       0 1157.42     .05       0
 1404.99     .05       0 1660.96     .05       0 2063.79      .1       0
Bank Sta=415.87,571.82
XS Rating Curve= 0 ,0
Exp/Cntr=0.3,0.1

Type RM Length L Ch R = 1 ,44691   ,942.2,897,846.8
XS GIS Cut Line= 2
2431211.58083385678404.879085049 2433356.4476071677562.684247121
#Sta/Elev= 30
       0 1732.34    46.4 1705.89      85 1678.31    97.9 1672.68     186 1610.83
   232.3  1586.5   282.7 1567.01   299.9 1562.74   394.5 1551.64     403 1548.35
   439.1 1547.24     446 1542.99  503.191495.348   519.1 1491.13   541.7 1489.53
   609.3 1489.76  646.961494.422   673.6 1500.91   875.8 1497.59   957.4 1499.66
  1130.3 1497.63  1250.6 1500.39  1791.1 1497.35  1911.4 1501.61  2057.5 1517.86
  2114.6 1542.26  2182.5 1549.78  2212.2  1556.6  2278.1 1588.44  2304.3 1596.83
#Mann= 8 ,-1 , 0
       0      .1       0  342.09     .06       0  443.71      .1       0
  503.19    .045       0  646.96      .1       0  748.58     .05       0
 1256.69     .05       0 1991.93      .1       0
Bank Sta=503.19,646.96
XS Rating Curve= 0 ,0
Exp/Cntr=0.3,0.1

Type RM Length L Ch R = 1 ,43794   ,1047.8,1075.2,1107.9
XS GIS Cut Line= 5
2431713.48271719 679580.62443696 2432331.9476876678913.461401209
2432723.56468654678316.4281464672433273.29291779677873.870960712
2433501.19042787677738.647805959
#Sta/Elev= 30
       0  1719.5      43 1706.71   194.6 1679.68   272.5 1641.32   392.7 1567.79
   496.1  1533.1   572.6 1532.33   607.8 1526.13   984.6 1516.45    1058 1499.73
  1124.5 1499.34  1166.3 1492.88  1228.5  1495.5 1244.791490.864  1252.4 1486.41
  1285.9 1485.07 1320.581489.648  1386.4 1491.47  1415.1 1484.36  1459.6 1484.35
  1477.3 1491.01  1553.8  1496.8    1977 1494.84  2210.3 1500.14  2238.9  1506.5
  2340.5  1555.9  2391.1 1564.24  2470.7  1566.1  2498.6  1575.2  2594.5 1583.65
#Mann= 13 ,-1 , 0
       0      .1       0  538.18     .06       0  664.15     .05       0
 1064.23      .1       0 1221.64    .025       0 1244.79    .045       0
 1320.58    .025       0 1484.53      .1       0 1646.14     .05       0
 1807.27     .05       0 1874.64     .05       0 2002.32     .05       0
 2103.15      .1       0
Bank Sta=1244.79,1320.58
XS Rating Curve= 0 ,0
Exp/Cntr=0.3,0.1

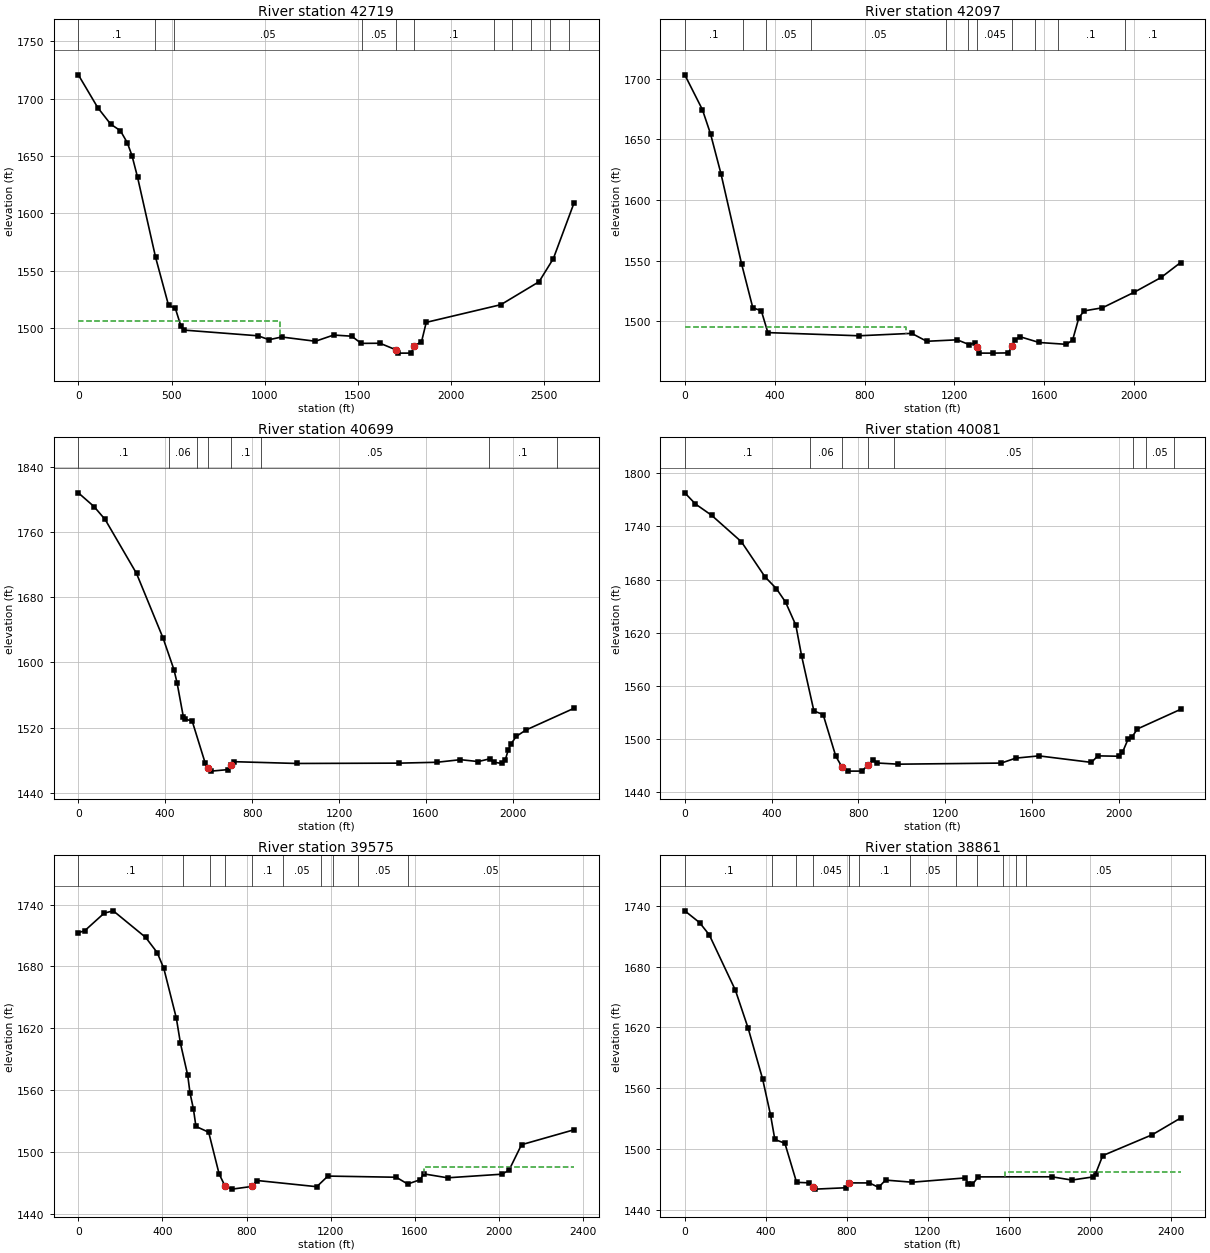
Type RM Length L Ch R = 1 ,42719   ,621.9,622.4,632.2
XS GIS Cut Line= 3
2431762.25624168679764.4587149622433239.25099111679262.208735213
2434271.50876909678882.999191791
#Sta/Elev= 30
       0 1720.84   104.3 1692.18   173.7 1677.77   225.5 1672.12   262.5 1661.65
   287.8 1650.37   317.4  1631.7   414.6 1561.51     484 1519.72   520.2 1517.21
   549.8 1501.88   566.7 1498.15   963.8 1493.17    1023 1489.75  1090.6 1492.12
  1272.2 1488.41  1369.4 1493.83  1466.6 1492.82  1517.3 1486.56  1618.3 1486.67
 1704.021480.918  1717.2 1478.05  1786.6 1478.06 1799.991484.388  1840.8  1487.8
  1866.3 1504.89  2266.6 1520.31  2471.4 1540.33  2548.2 1560.51  2659.8 1609.38
#Mann= 11 ,-1 , 0
       0      .1       0  411.33     .06       0  512.04     .05       0
 1519.22     .05       0 1704.02    .045       0 1799.99      .1       0
 2227.17      .1       0 2328.33      .1       0 2429.49      .1       0
 2530.66     .12       0 2631.82      .1       0
#XS Ineff= 2 , 0
         1083.19 1505.88
Permanent Ineff=
       F       F
Bank Sta=1704.02,1799.99
XS Rating Curve= 0 ,0
Exp/Cntr=0.3,0.1

Type RM Length L Ch R = 1 ,42097   ,1367.7,1397.5,1356
XS GIS Cut Line= 4
2432081.28709969680189.9171816262433219.50627995679840.069128051
2433637.44343618679785.3074265422434228.81331643 679721.06017971
#Sta/Elev= 30
       0 1703.14    78.4 1674.44   114.5 1654.54   160.8 1621.83   252.6 1547.55
   302.8 1511.22   340.5 1508.85   369.8 1490.82   775.7 1488.21    1010  1490.2
    1077 1483.68  1212.5 1484.88  1266.7 1480.88  1290.9 1482.36 1302.11 1479.34
    1311 1473.94  1371.5 1473.92  1440.1 1474.12 1457.191479.855  1468.4 1484.68
  1492.6 1487.41  1577.3 1482.68  1698.1 1481.17  1726.2 1484.63  1754.4 1503.25
    1778 1508.72    1859 1511.26  2000.4 1524.06  2120.6 1536.28  2207.1 1548.55
#Mann= 11 ,-1 , 0
       0      .1       0  260.55     .06       0  360.81     .05       0
  561.33     .05       0  1162.9     .05       0 1262.51      .1       0
 1302.11    .045       0 1457.19      .1       0 1560.59    .045       0
    1660      .1       0 1958.36      .1       0
#XS Ineff= 2 , 0
          983.61  1495.6
Permanent Ineff=
       F       F
Bank Sta=1302.11,1457.19
XS Rating Curve= 0 ,0
Exp/Cntr=0.3,0.1

Type RM Length L Ch R = 1 ,40699   ,622.2,617.8,604.8
XS GIS Cut Line= 3
 2432340.8531816681352.0733218792433029.84064877680941.278867871
2434343.05521393 680259.28252846
#Sta/Elev= 30
       0 1808.37    72.1 1791.52   123.3 1775.64   267.7 1709.39   390.3 1629.72
     440 1591.23   454.5 1574.87   483.6 1532.68   489.5 1530.44   523.8 1528.16
   584.3 1476.01  598.62 1469.99     612 1466.53   686.8 1468.35  702.391474.565
   714.7 1478.14    1005 1475.94    1478 1476.35  1650.1 1477.41  1758.7 1480.59
  1840.1 1478.28  1893.9 1481.69  1914.1  1477.4    1948 1476.01  1964.5 1480.03
    1979 1492.87  1991.2 1499.95  2015.6 1509.21  2059.5 1516.96  2281.9  1543.8
#Mann= 8 ,-1 , 0
       0      .1       0  415.66     .06       0  545.32      .1       0
  598.62    .045       0  702.39      .1       0  842.06     .05       0
 1887.73      .1       0 2201.43     .05       0
Bank Sta=598.62,702.39
XS Rating Curve= 0 ,0
Exp/Cntr=0.3,0.1

Type RM Length L Ch R = 1 ,40081   ,508.4,506.6,504.1
XS GIS Cut Line= 2
2432705.62049669681988.2301860452434443.25448862680505.714778379
#Sta/Elev= 30
       0 1777.83    48.8 1765.28   123.8 1752.43   260.9 1722.59   369.5 1683.03
   421.7  1669.8   464.2 1654.54   511.5 1628.49   538.2 1593.76   594.7 1531.76
   637.3 1527.68   695.5 1480.72  722.771469.057   753.6 1463.88   816.5 1463.92
  842.571470.531     869 1476.78   884.8 1473.07   983.4 1471.72  1457.9 1472.96
  1524.3 1478.53  1631.5 1481.08  1873.3 1473.73  1902.7 1481.09    2002 1480.67
  2016.2 1485.12    2042 1499.94  2060.5 1502.53  2085.1 1511.47  2284.1 1533.58
#Mann= 8 ,-1 , 0
       0      .1       0  578.43     .06       0  722.77    .045       0
  842.57      .1       0   963.3     .05       0 2065.98      .1       0
 2125.14     .05       0 2251.93      .1       0
Bank Sta=722.77,842.57
XS Rating Curve= 0 ,0
Exp/Cntr=0.3,0.1

Type RM Length L Ch R = 1 ,39575   ,705.5,714,719.8
XS GIS Cut Line= 3
2433069.46819419682358.7215710432433381.08043185682092.891722128
2434819.11364502680777.430770382
#Sta/Elev= 30
       0 1712.75    30.6  1714.7     123 1731.74   166.1 1733.99   320.2 1708.22
     375 1693.49   406.6 1678.08   466.1 1629.92   485.8 1605.34   520.3 1574.39
   531.1 1557.36   547.4 1541.73   559.4 1524.75     620 1519.11   669.8 1478.53
  697.14 1467.12   731.7 1463.88  824.94 1466.47     851 1472.24  1134.2 1466.24
  1187.1 1476.55  1512.3 1475.41  1566.6 1468.82  1626.2 1473.04  1642.4  1478.7
  1756.3 1474.87  2014.7 1478.38  2048.6 1482.22  2108.1 1506.99  2358.5 1521.53
#Mann= 10 ,-1 , 0
       0      .1       0  498.22     .06       0  627.03      .1       0
  697.14    .045       0  824.94      .1       0  973.21     .05       0
 1155.53     .05       0  1210.7      .1       0 1329.45     .05       0
 1566.94     .05       0
#XS Ineff= 2 , 0
                         1643.58         1485.05
Permanent Ineff=
       F       F
Bank Sta=697.14,824.94
XS Rating Curve= 0 ,0
Exp/Cntr=0.3,0.1

Type RM Length L Ch R = 1 ,38861   ,722.2,716.1,702.4
XS GIS Cut Line= 3
2433483.54151303682844.6182370482434258.28701076  682284.1498698
2435409.14921036681333.880444884
#Sta/Elev= 30
       0 1734.97    73.1 1723.32     121 1711.22   249.9 1656.63   312.9 1619.14
   384.1 1569.25   423.6 1533.51   444.7 1509.43   494.3  1505.7     552 1467.15
   611.2 1466.69   633.51462.845   645.2 1460.46   794.2 1461.81  812.79 1466.61
   911.6 1466.57   956.8 1462.23   991.5 1469.37  1122.8 1467.29  1385.4 1471.52
  1400.7 1465.51  1420.6 1465.11    1449 1472.53  1813.3 1472.62  1911.3  1469.4
    2015 1472.47  2028.6 1475.57  2063.9 1493.51  2308.9 1514.15  2448.7 1530.58
#Mann= 12 ,-1 , 0
       0      .1       0  431.32     .06       0  548.97      .1       0
   633.5    .045       0  812.79    .025       0  860.27      .1       0
 1109.94     .05       0 1340.09     .05       0 1443.68     .05       0
 1570.24     .05       0 1634.65     .05       0 1685.31     .05       0
#XS Ineff= 2 , 0
                         1579.99         1477.51
Permanent Ineff=
       F       F
Bank Sta=633.5,812.79
XS Rating Curve= 0 ,0
Exp/Cntr=0.3,0.1

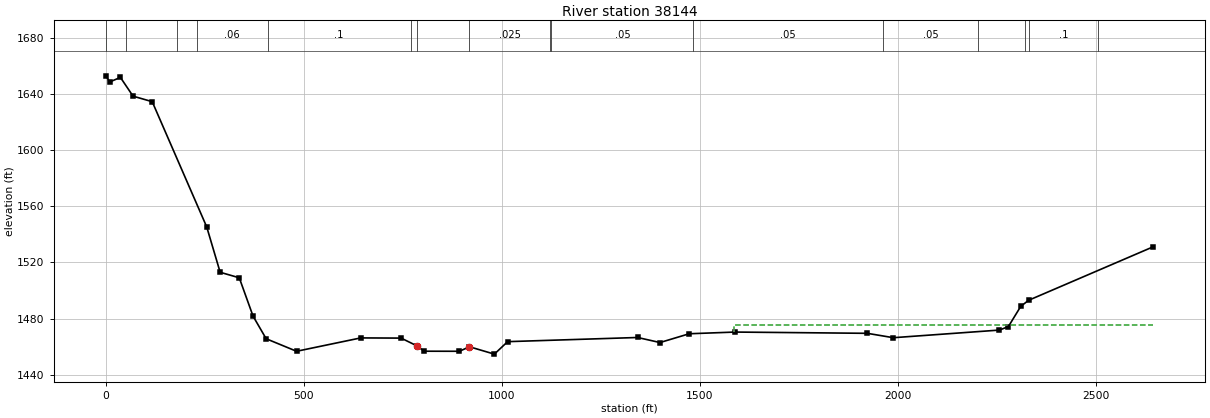
Type RM Length L Ch R = 1 ,38144   ,608.4,624.9,633.2
XS GIS Cut Line= 3
2433931.46253318683492.5355763732434681.93576977682822.289213464
2435877.23095137681700.843621716
#Sta/Elev= 30
       0 1652.75     9.8 1648.39    36.6 1651.64    68.6 1638.28     117 1634.35
   254.7 1545.19   288.6 1512.92   336.9    1509   371.7 1481.71   404.8 1465.61
   481.7 1456.69   643.7  1466.2   745.7 1466.07  786.591460.426   803.5 1456.74
     893 1456.69  918.361459.893   981.3 1454.66  1014.8 1463.54  1343.1  1466.5
  1399.7 1462.91  1473.5 1469.16  1589.3 1470.37  1923.3 1469.47  1989.1 1466.35
  2257.1 1471.78  2279.8 1474.28  2310.9 1488.62  2330.7 1492.97  2645.2 1531.02
#Mann= 16 ,-1 , 0
       0      .1       0   50.23     .06       0  180.45      .1       0
  229.62     .06       0  409.02      .1       0  769.62    .025       0
  786.59    .045       0  918.36    .025       0 1122.24      .1       0
 1125.02     .05       0 1484.26     .05       0 1963.24     .05       0
 2202.74      .1       0 2322.48      .1       0 2332.52      .1       0
 2505.41      .1       0
#XS Ineff= 2 , 0
                         1585.64         1475.44
Permanent Ineff=
       F       F
Bank Sta=786.59,918.36
XS Rating Curve= 0 ,0
Exp/Cntr=0.3,0.1