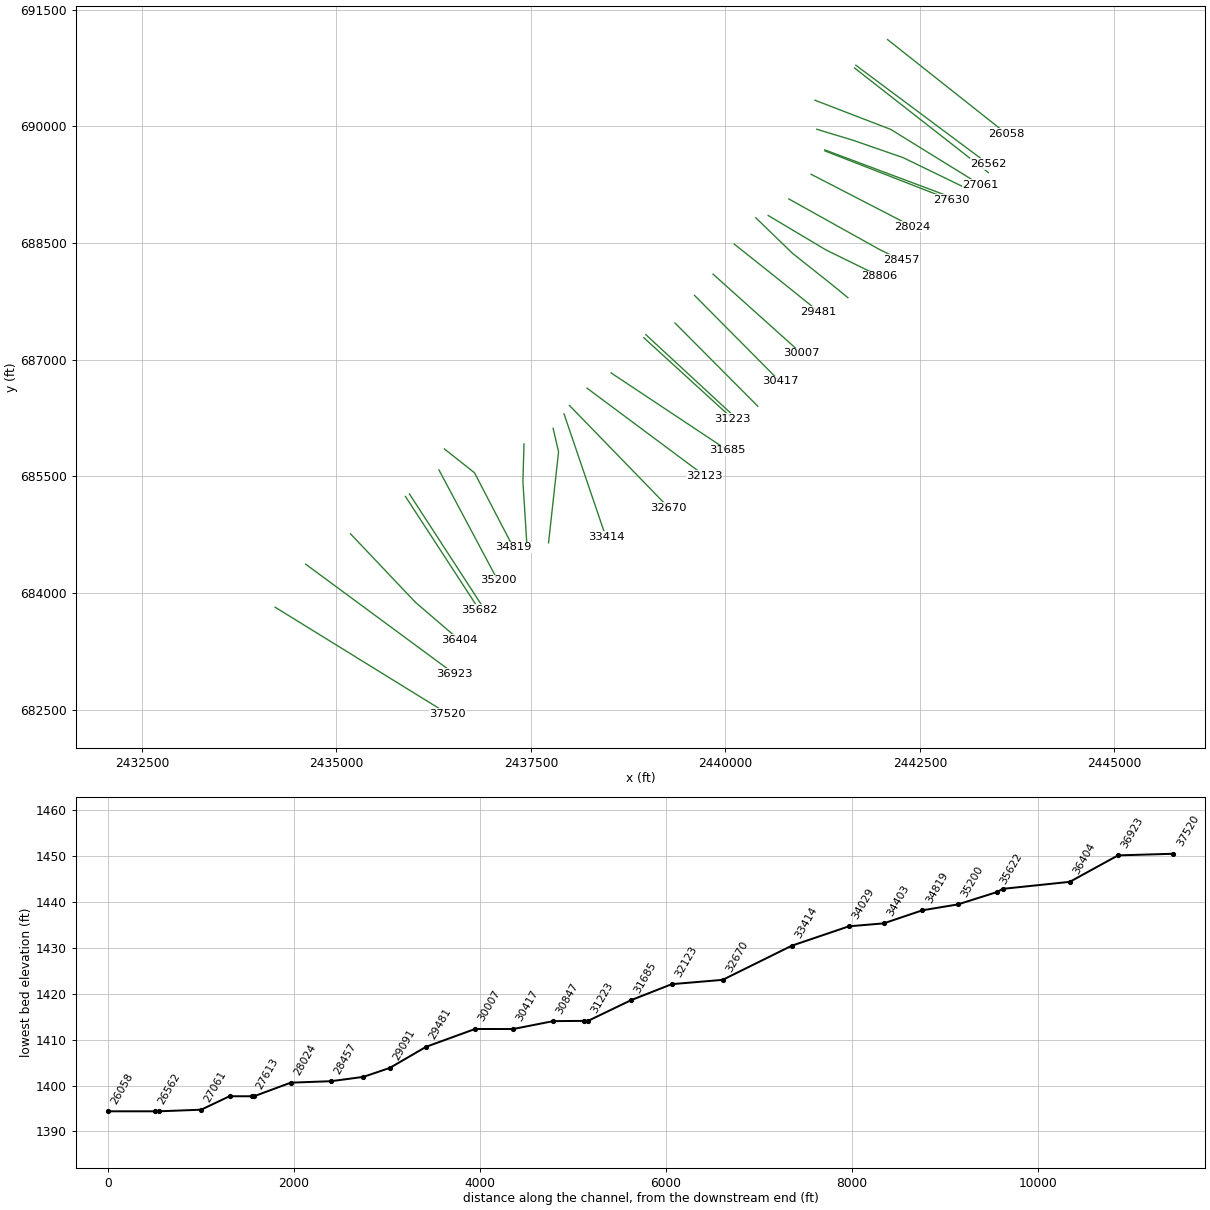
HEC-RAS study NFSBPOTOMC.prj: NFSBPOTOMC

--- NFSBPOTOMC.g01 (geometry) --- (continued)

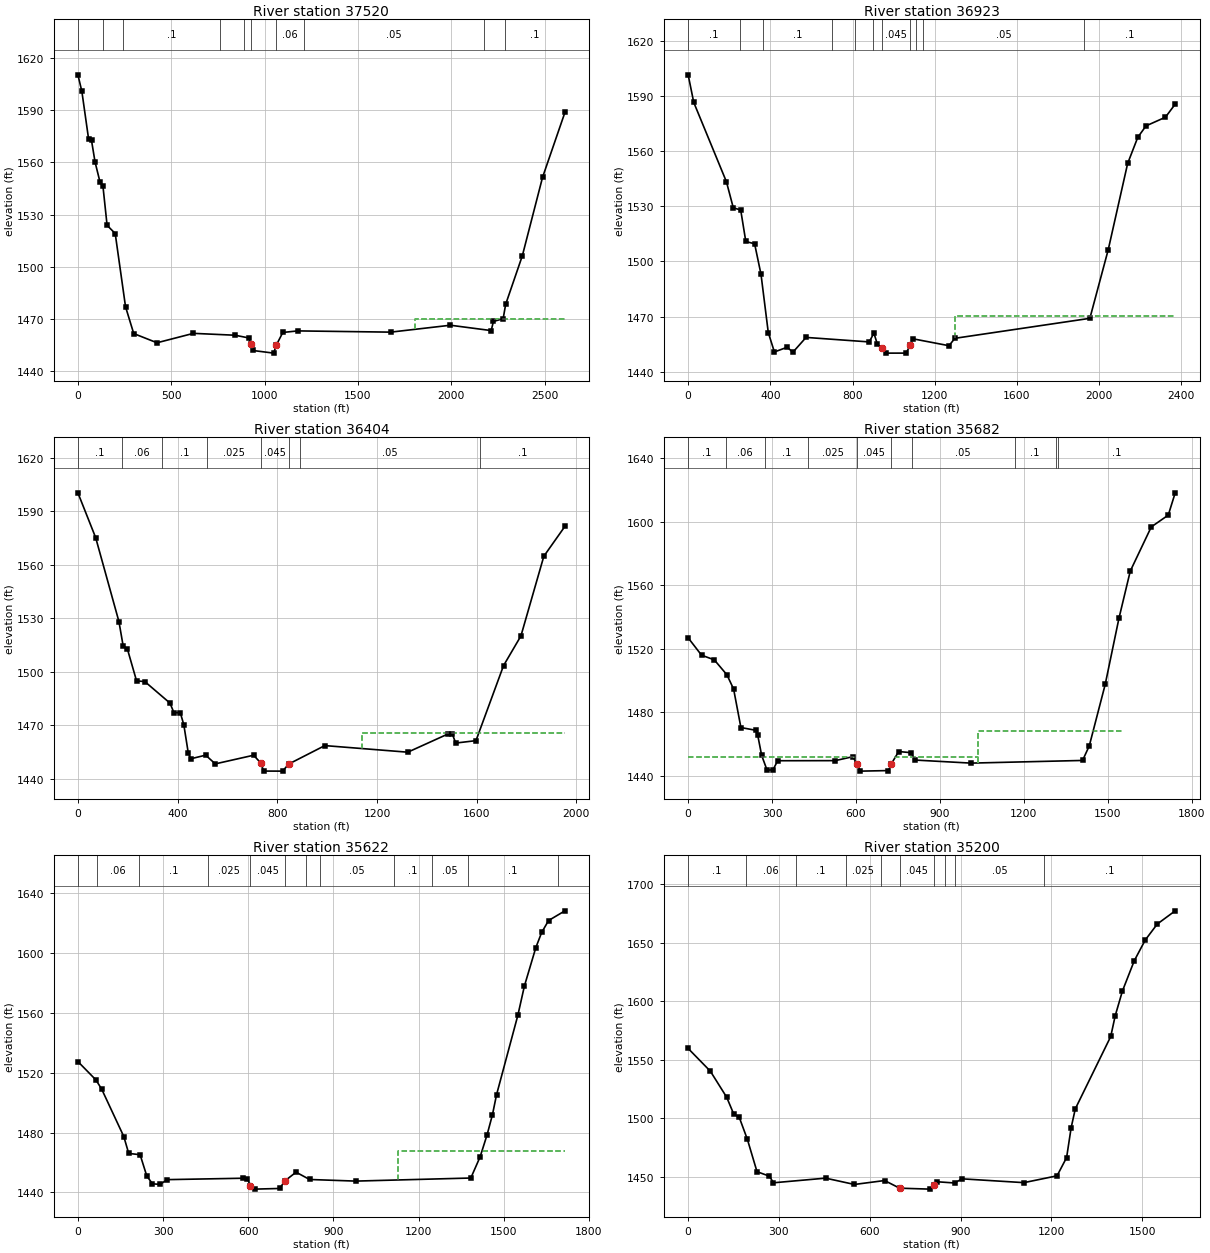
Type RM Length L Ch R = 1 ,37520   ,601.9,596.1,590.8
XS GIS Cut Line= 2
2434212.66374245683820.0227822962436432.91356704682449.465155959
#Sta/Elev= 30
       0 1610.13    21.2 1600.67    57.6 1573.09      73 1572.48    91.8 1560.18
   118.6 1548.56   134.1 1546.39   156.4 1523.81   199.9 1519.11   255.2 1477.12
   299.1 1461.73   423.8 1456.45     619 1461.85   842.3 1460.77     916 1459.21
  927.011455.611   937.9 1452.02  1048.7 1450.51 1062.86 1455.08  1097.7 1462.36
  1177.6 1463.26  1675.9 1462.55  1995.6 1466.51  2214.2 1463.44  2225.9 1468.66
  2278.2 1470.27  2291.7 1478.53    2381 1506.37  2489.1 1551.29  2609.2 1588.61
#Mann= 10 ,-1 , 0
       0      .1       0  135.88     .06       0  243.36      .1       0
  763.49    .025       0  888.25      .1       0  927.01    .045       0
 1062.86     .06       0 1210.69     .05       0 2178.02    .055       0
 2285.51      .1       0
#XS Ineff= 2 , 0
                          1807.8         1469.85
Permanent Ineff=
       F       F
Bank Sta=927.01,1062.86
XS Rating Curve= 0 ,0
Exp/Cntr=0.3,0.1

Type RM Length L Ch R = 1 ,36923   ,527.5,519,507.9
XS GIS Cut Line= 2
2434604.81584528684373.2808621232436513.12173995682966.434594467
#Sta/Elev= 30
       0 1601.39    27.2 1586.41   186.3 1543.28   219.7 1529.13   255.8 1527.94
   280.6 1510.82   323.5 1509.57   354.6 1492.99     390 1461.33   419.8 1450.79
   482.6 1453.39   509.4 1450.59   573.9  1458.7   881.3 1456.25   904.2 1461.02
   921.3 1454.92  943.541452.888   961.2 1450.16  1061.5 1450.17 1079.471454.321
    1093 1457.97  1269.6 1454.19  1298.3 1458.21  1955.4 1469.07  2044.9  1506.4
  2139.3 1553.23  2188.6 1567.42  2228.7 1573.64  2323.2 1578.35  2370.8 1585.46
#Mann= 11 ,-1 , 0
       0      .1       0  252.12     .06       0  363.77      .1       0
  698.73     .05       0  810.38    .025       0  898.37     .05       0
  943.54    .045       0 1079.47    .025       0 1109.13     .06       0
 1145.34     .05       0 1926.91      .1       0
#XS Ineff= 2 , 0
                         1298.76         1470.53
Permanent Ineff=
       F       F
Bank Sta=943.54,1079.47
XS Rating Curve= 0 ,0
Exp/Cntr=0.5,0.3

Type RM Length L Ch R = 1 ,36404   ,735.5,722.2,713.1
XS GIS Cut Line= 3
 2435181.9203341684762.840450466 2436013.8674891683885.552834958
2436579.05172619683399.832677796
#Sta/Elev= 30
       0 1600.34    71.3 1575.23   164.7 1528.17   181.8 1514.39   198.4 1512.94
   235.4 1494.96   268.6 1494.57   369.3 1482.53   385.3 1477.18   410.8 1477.15
     425  1470.4     443 1454.46   453.3 1451.31   512.7 1453.34   551.2 1448.45
   705.1  1453.3   734.21448.873   745.3 1444.42   821.3 1444.39  845.931448.355
   990.8  1458.7  1323.6    1455  1484.5 1465.18  1501.6 1465.42  1516.1 1460.12
  1597.3 1461.47  1707.9 1503.51  1777.7 1520.16  1869.6  1564.8  1954.3 1581.56
#Mann= 8 ,-1 , 0
       0      .1       0  178.26     .06       0   337.8      .1       0
  518.18    .025       0   734.2    .045       0  845.93     .06       0
  892.79     .05       0 1612.77      .1       0
#XS Ineff= 1 ,-1
 1139.82 1954.26 1465.71
Permanent Ineff=
       F
Bank Sta=734.2,845.93
XS Rating Curve= 0 ,0
Exp/Cntr=0.5,0.3

Type RM Length L Ch R = 1 ,35682   ,60.3,60.1,59.9
XS GIS Cut Line= 2
2435887.78440794685243.028466463 2436838.4996981683784.264979795
#Sta/Elev= 30
       0 1526.85    47.9 1515.91    93.3    1513   138.6 1503.56   162.5 1494.57
   188.6 1470.32   242.2 1468.58   248.4 1465.76   262.8 1452.75   281.9 1443.56
   302.9 1443.59   320.1 1449.41   525.6 1449.47     589 1451.97  603.041447.316
   616.1 1442.86     716 1443.21  726.841447.617   752.7 1455.21   796.6 1454.48
   811.8 1449.83  1011.1 1447.91    1410 1449.59    1434 1458.77  1490.9 1497.47
    1540 1539.09  1580.5 1568.88  1655.7 1596.75  1716.4 1604.18  1741.2 1618.22
#Mann= 10 ,-1 , 0
       0      .1       0  133.98     .06       0  274.38      .1       0
   429.1    .025       0  603.04    .045       0  726.84     .06       0
  798.77     .05       0 1166.91      .1       0 1314.47     .05       0
 1323.16      .1       0
#XS Ineff= 3 ,-1
       0  592.04    1452  737.84    1035    1452    1035    1550    1468
Permanent Ineff=
       F       F       F
Bank Sta=603.04,726.84
XS Rating Curve= 0 ,0
Exp/Cntr=0.5,0.3

Type RM Length L Ch R = 1 ,35622   ,427.4,421.8,417
XS GIS Cut Line= 2
2435939.35517094685275.1140322092436874.11183161683836.928260297
#Sta/Elev= 30
       0 1527.51    63.3 1515.26    83.6 1509.12   161.6 1477.37     179 1466.05
   219.1  1465.2   242.6 1450.97   262.7 1445.72   288.9 1445.35   315.1 1448.52
   580.9 1449.46   596.6 1449.23  607.741444.415   622.8 1442.17   711.1 1442.62
  727.691447.477   768.3 1453.51     816 1448.62   978.2 1447.54  1383.8  1449.6
  1416.5 1463.75    1441 1478.45  1459.9 1491.86  1474.4  1505.3  1549.5 1558.48
  1572.6 1578.09  1612.7 1603.69  1633.3 1613.86  1657.7 1621.85  1715.3 1628.33
#Mann= 12 ,-1 , 0
       0      .1       0   66.06     .06       0  213.82      .1       0
  458.22    .025       0  607.74    .045       0  727.69     .06       0
  804.88      .1       0  851.07     .05       0 1112.98      .1       0
 1248.17     .05       0 1374.88      .1       0 1691.47      .1       0
#XS Ineff= 1 ,-1
 1127.79 1715.27 1467.36
Permanent Ineff=
       F
Bank Sta=607.74,727.69
XS Rating Curve= 0 ,0
Exp/Cntr=0.3,0.1

Type RM Length L Ch R = 1 ,35200   ,381.6,381,380.6
XS GIS Cut Line= 2
2436318.96267945685583.7006853822437075.46051028684163.472882792
#Sta/Elev= 30
       0 1559.67    73.4 1540.22   127.2 1518.03   150.5 1503.67   168.6 1500.96
   195.8 1481.89   227.5 1454.35   268.3 1450.58   281.9 1444.89   454.1 1448.85
   549.3 1443.46     649 1446.81  698.761440.277   798.8 1439.47  810.561443.015
   821.2 1445.79   880.1 1444.72   905.3 1448.26  1109.3 1445.01  1218.7 1450.84
  1250.3 1466.43  1265.4 1492.09    1279 1508.05  1396.1  1569.9  1410.9 1587.63
  1434.6 1608.68  1473.8  1634.6  1510.1 1652.33  1549.9    1666  1609.1 1677.28
#Mann= 10 ,-1 , 0
       0      .1       0  192.19     .06       0  356.26      .1       0
  520.33    .025       0  636.83      .1       0  698.76    .045       0
  810.56    .025       0  848.48      .1       0  880.69     .05       0
 1176.62      .1       0
Bank Sta=698.76,810.56
XS Rating Curve= 0 ,0
Exp/Cntr=0.3,0.1

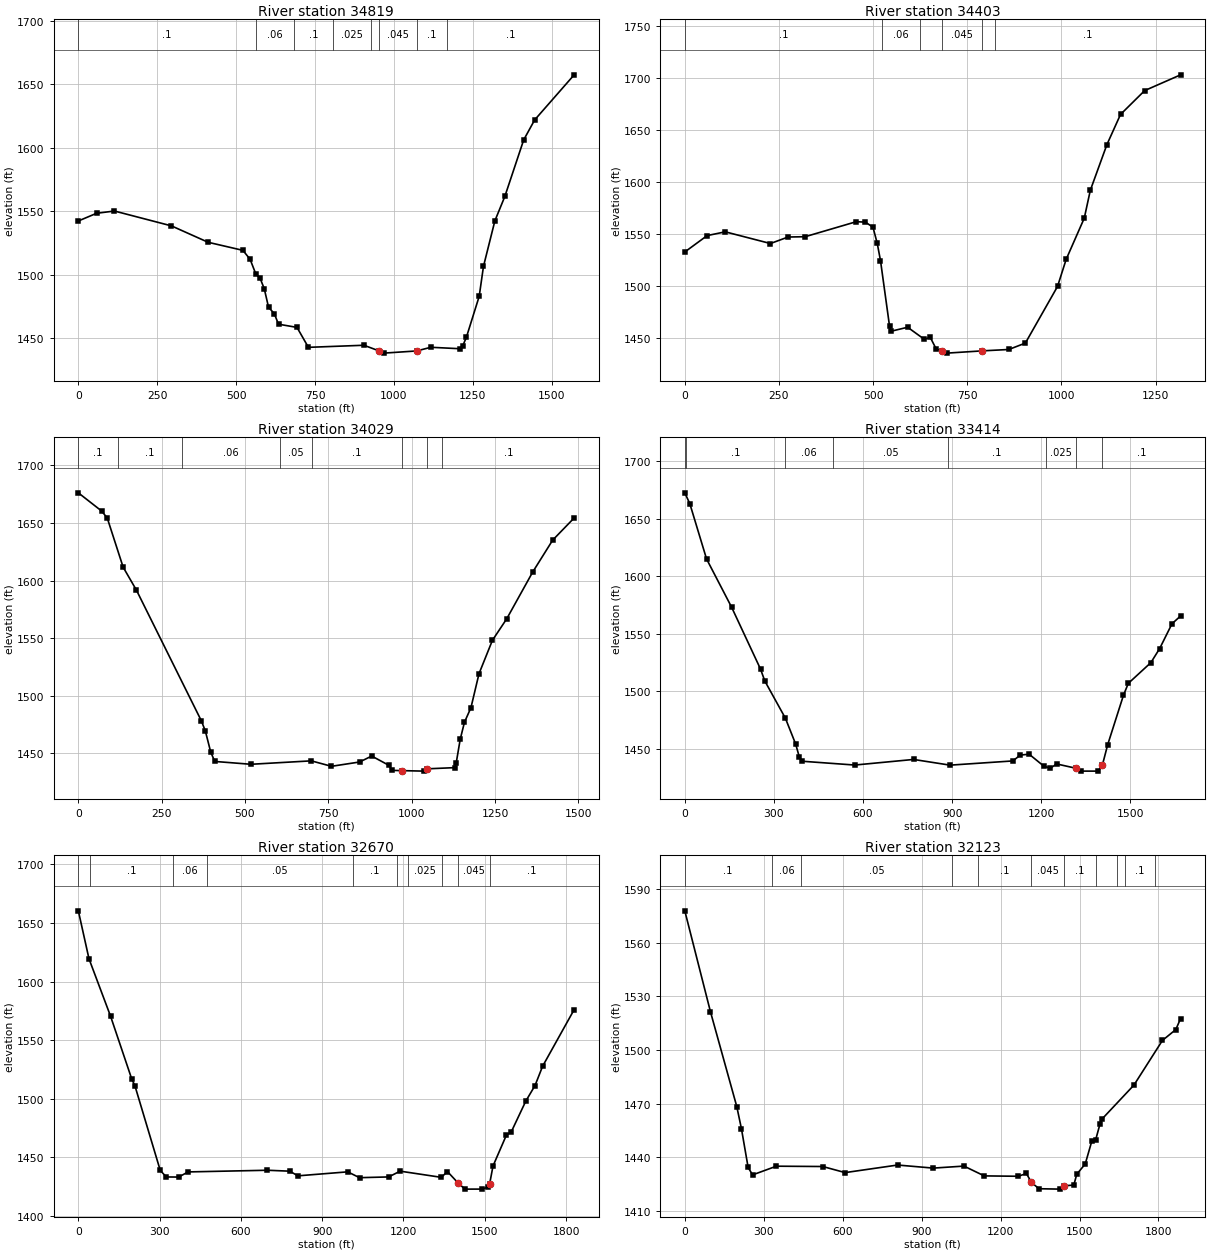
Type RM Length L Ch R = 1 ,34819   ,440.9,416.4,393
XS GIS Cut Line= 3
2436388.39397103685853.9455517082436775.31937829685547.657778457
2437272.55854127  684592.0428918
#Sta/Elev= 30
       0 1542.23      58  1548.3   114.5 1550.06   294.9 1538.38   411.1 1525.46
   521.4  1519.1   544.2 1512.02     562 1500.64   575.5 1497.33     589 1488.89
   602.6 1474.28   620.6 1469.33   634.1 1460.97   692.7 1458.45   728.8 1442.75
   904.7 1444.39  952.311439.981   967.8 1438.19    1072 1439.91  1116.6 1442.79
  1208.4 1441.66  1217.3  1443.7  1229.2 1450.59  1269.9 1482.94  1283.4 1506.46
  1319.5  1542.3  1351.1 1561.54  1410.8 1606.05  1445.5 1621.76  1570.7 1657.29
#Mann= 8 ,-1 , 0
       0      .1       0  563.21     .06       0  684.27      .1       0
  805.33    .025       0  926.39      .1       0  952.31    .045       0
    1072      .1       0 1168.51      .1       0
Bank Sta=952.31,1072
XS Rating Curve= 0 ,0
Exp/Cntr=0.3,0.1

Type RM Length L Ch R = 1 ,34403   ,385.8,373.9,364.9
XS GIS Cut Line= 3
 2437411.7665962685918.2065780462437397.91098085685431.822708294
2437450.34132218684603.592737466
#Sta/Elev= 30
       0 1532.66    59.3 1548.43   107.4 1552.05   227.4  1540.8   274.2 1547.06
   319.4 1547.35   455.5 1561.82   479.5 1561.37   499.6 1556.52   510.9 1541.07
   519.6 1524.41   543.6 1461.37   547.6  1456.4   591.7 1460.24   635.8 1448.68
   651.8 1450.47   667.9 1439.03  682.081437.785   695.9 1435.34  789.811437.516
   860.3 1438.84   904.3 1445.01   989.6 1499.45  1012.6 1525.57  1060.7 1565.26
  1076.7 1591.98  1120.8 1636.01  1156.9    1665    1221 1687.94  1316.5 1703.12
#Mann= 6 ,-1 , 0
       0      .1       0  524.78     .06       0  624.67    .025       0
  682.08    .045       0  789.81    .025       0  824.45      .1       0
Bank Sta=682.08,789.81
XS Rating Curve= 0 ,0
Exp/Cntr=0.3,0.1

Type RM Length L Ch R = 1 ,34029   ,586.8,615,627.2
XS GIS Cut Line= 3
2437786.15987629686119.5795348732437856.15448695 685816.85901171
2437727.44411445684647.130380049
#Sta/Elev= 30
       0 1676.08    70.5 1660.15    86.9 1654.11   134.4 1611.61   174.5 1591.56
     369 1478.36   381.1 1469.45   397.1 1451.27   409.3  1443.1   517.9 1440.64
     699 1443.61   759.4 1438.88   843.9 1442.62   880.1 1447.78   932.4 1439.64
   940.5 1435.34  971.181435.136    1037  1434.7  1044.71436.668  1129.6 1437.73
  1133.6  1441.7  1145.7 1462.37  1158.4 1477.07  1177.9 1489.78    1202 1519.16
  1242.3 1548.19  1285.3 1566.87    1363 1607.32  1423.1 1635.07  1487.5 1654.29
#Mann= 8 ,-1 , 0
       0      .1       0  118.71      .1       0  311.13     .06       0
  604.04     .05       0  701.68      .1       0  971.18    .045       0
  1044.7    .025       0 1092.23      .1       0
Bank Sta=971.18,1044.7
XS Rating Curve= 0 ,0
Exp/Cntr=0.3,0.1

Type RM Length L Ch R = 1 ,33414   ,722.5,743.5,769.3
XS GIS Cut Line= 2
2437926.42534378686304.1533127132438464.12275919684724.127273291
#Sta/Elev= 30
       0  1672.6      17  1663.1    73.2 1615.08   157.7 1573.02   254.9 1519.25
   269.2 1508.96   338.6 1476.51   373.2    1454   385.8  1442.5   395.3 1439.07
   572.1 1435.76   770.1 1440.63   892.9 1435.67  1104.1 1439.34  1129.5 1444.43
  1159.1 1445.21  1209.8 1434.53  1230.9 1433.16    1252  1436.7 1317.641432.907
  1332.3 1430.49  1391.4 1430.47 1405.481435.579  1423.4 1453.39  1476.6 1496.48
  1492.9 1506.84  1568.9 1524.88  1598.5 1537.15  1639.9 1558.67    1669 1565.51
#Mann= 8 ,-1 , 0
       0      .1       0    5.68      .1       0  335.95     .06       0
  498.24     .05       0  886.41      .1       0 1216.67    .025       0
 1317.64    .045       0 1405.48      .1       0
Bank Sta=1317.64,1405.48
XS Rating Curve= 0 ,0
Exp/Cntr=0.3,0.1

Type RM Length L Ch R = 1 ,32670   ,540.3,547.1,558
XS GIS Cut Line= 2
 2437996.5567652686412.2233065522439271.33800828 685099.32271713
#Sta/Elev= 30
       0 1660.25    39.3 1619.39   118.9 1570.46     197 1516.98     209 1511.01
   302.3 1439.01   324.7  1433.4   370.2 1433.32   405.1  1437.7   697.9 1439.12
   780.4 1438.33   810.3 1434.36   994.3 1437.76  1037.8 1432.79  1145.3 1433.42
  1187.7 1438.35  1339.9 1433.07  1362.2 1438.04 1402.441428.062  1427.2 1423.03
  1490.4 1423.06  1512.8 1424.82 1518.311427.819  1530.5 1442.75  1579.7 1468.96
  1597.9 1471.84  1651.6 1498.11  1685.6 1511.35  1713.5 1527.75    1830 1576.06
#Mann= 10 ,-1 , 0
       0      .1       0   41.61      .1       0  350.57     .06       0
  474.33     .05       0 1013.78      .1       0  1175.8     .05       0
 1216.92    .025       0 1340.69      .1       0 1402.44    .045       0
 1518.31      .1       0
Bank Sta=1402.44,1518.31
XS Rating Curve= 0 ,0
Exp/Cntr=0.3,0.1

Type RM Length L Ch R = 1 ,32123   ,425.8,438.1,452.2
XS GIS Cut Line= 2
2438222.15834811686634.6359194672439733.51621777685509.597159043
#Sta/Elev= 30
       0 1577.91    97.4 1521.46   197.5 1468.33   215.2 1455.93   240.7  1434.2
   257.7 1430.07   347.9 1434.93   524.3 1434.75   609.2 1431.34   808.6 1435.58
   944.1 1433.86  1060.8 1434.99    1138  1429.5  1267.3 1429.29  1298.1 1430.85
 1317.291425.812    1346 1422.31  1426.4 1422.09 1441.041423.953  1478.1 1424.35
  1489.6 1430.46  1521.6 1436.17  1546.8 1449.08  1561.1 1449.64  1578.2  1458.8
  1587.2 1461.61  1706.8 1480.36    1815 1505.36  1865.7 1511.42  1884.1 1517.62
#Mann= 11 ,-1 , 0
       0      .1       0  330.02     .06       0  441.94     .05       0
 1016.39    .025       0 1113.46      .1       0 1317.29    .045       0
 1441.04      .1       0 1561.14      .1       0 1643.13      .1       0
 1673.06      .1       0 1784.98      .1       0
Bank Sta=1317.29,1441.04
XS Rating Curve= 0 ,0
Exp/Cntr=0.3,0.1

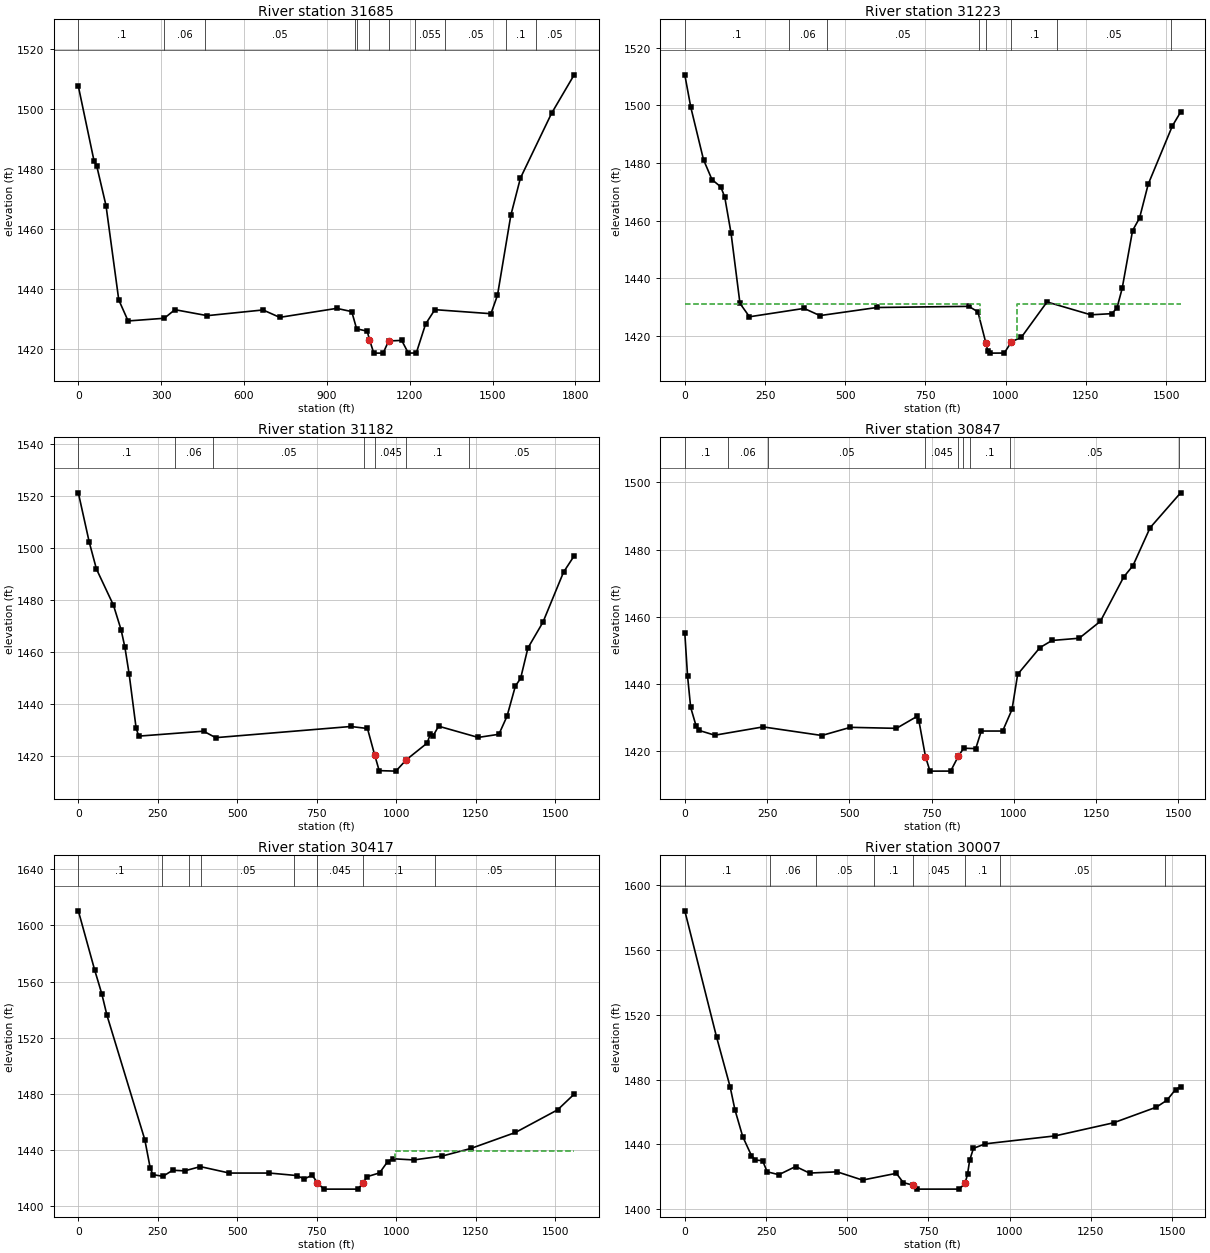
Type RM Length L Ch R = 1 ,31685   ,468.1,462.5,455.8
XS GIS Cut Line= 2
2438531.52813619686830.6187952162440026.87127411685837.278918371
#Sta/Elev= 30
       0 1507.63    56.7 1482.79    66.3 1481.16   100.2 1467.82   146.4 1436.35
   180.2 1429.33   311.2 1430.23   349.6 1433.09   466.7  1431.1   668.7    1433
   729.2 1430.53   935.5 1433.53   989.9 1432.45  1007.5 1426.73  1045.9 1425.92
    10541423.123  1069.7  1418.6  1103.6 1418.61  1123.51422.646  1170.7 1422.85
  1194.8 1418.62  1223.6 1418.64  1257.2 1428.28  1290.8  1433.1  1493.9 1431.75
  1517.6 1437.91    1566 1464.62  1600.6 1476.97  1713.4 1498.59  1795.2 1511.43
#Mann= 11 ,-1 , 0
       0      .1       0  311.43     .06       0  456.85     .05       0
 1002.07    .025       0 1009.99     .05       0    1054    .045       0
  1123.5     .05       0 1220.16    .055       0  1329.2     .05       0
 1547.29      .1       0 1656.34     .05       0
Bank Sta=1054,1123.5
XS Rating Curve= 0 ,0
Exp/Cntr=0.5,0.3

Type RM Length L Ch R = 1 ,31223   ,43.1,41,40.3
XS GIS Cut Line= 2
2438952.22873837687282.7645444572440093.27927777686241.168858632
#Sta/Elev= 30
       0 1510.55    18.7 1499.31    58.3 1481.14    84.6 1474.26   112.1  1471.7
   124.4 1468.23   144.2  1455.6   171.9 1431.33   201.5 1426.69   371.7 1429.59
   421.1  1427.1   599.1 1429.91   885.1  1430.3   913.3  1428.4  938.161417.592
   944.5 1414.69   951.2 1414.09   995.5 1414.12    10181418.051  1048.7 1419.57
  1128.6 1431.82  1265.3 1427.37  1330.3 1427.77  1346.6 1429.72  1362.8  1436.5
  1395.3 1456.58    1417 1460.91    1444 1472.64  1519.3 1492.84    1545 1497.65
#Mann= 8 ,-1 , 0
       0      .1       0  324.76     .06       0  443.42     .05       0
  918.09    .025       0  938.16    .045       0    1018      .1       0
 1161.03     .05       0 1513.92      .1       0
#XS Ineff= 2 ,-1
       0  920.16 1431.15    1036 1544.97 1431.15
Permanent Ineff=
       F       F
Bank Sta=938.16,1018
XS Rating Curve= 0 ,0
Exp/Cntr=0.5,0.3

Type RM Length L Ch R = 1 ,31182   ,335.3,334.6,331.3
XS GIS Cut Line= 2
2438977.63616785 687322.24084346 2440122.4242326686264.210807294
#Sta/Elev= 30
       0 1521.28    34.3 1502.29    56.9 1491.93   110.4 1478.01   134.6 1468.45
   146.4 1461.79   159.5 1451.68   181.7 1430.64     190 1427.57   393.7 1429.47
   431.8 1426.98   856.6 1431.28     909 1430.51   931.31420.474   945.8 1414.28
   998.3 1414.09 1031.231418.479  1096.3 1424.86  1107.1 1428.43  1115.6 1427.74
  1132.6  1431.4  1257.1 1427.07  1322.2 1428.28  1347.7 1435.22  1374.1  1446.9
  1390.4 1449.77  1413.4 1461.52  1460.6 1471.43  1525.4 1490.72  1558.8    1497
#Mann= 7 ,-1 , 0
       0      .1       0  303.57     .06       0  422.72     .05       0
  899.32    .025       0   931.3    .045       0 1031.23      .1       0
 1227.26     .05       0
Bank Sta=931.3,1031.23
XS Rating Curve= 0 ,0
Exp/Cntr=0.5,0.3

Type RM Length L Ch R = 1 ,30847   ,430.9,430.3,427.5
XS GIS Cut Line= 2
2439352.87032554687471.5387732092440416.21399936686403.512694046
#Sta/Elev= 30
       0 1455.22     8.3 1442.43    17.8 1433.04    34.8 1427.33    44.2 1426.13
    91.2 1424.73     238  1427.2   416.5 1424.64   503.3 1427.07   643.3 1426.77
   705.7 1430.32   711.7 1428.97  731.571418.339   745.3 1414.03   808.1 1414.04
  831.511418.485   847.6 1420.85   884.3 1420.74   901.2 1425.97   966.1 1425.97
   994.6 1432.39  1011.8 1442.86  1079.4 1450.81  1116.2 1452.94  1198.9 1453.61
  1263.3 1458.66    1334 1471.83  1362.3 1475.24  1414.3 1486.51  1507.1 1496.91
#Mann= 9 ,-1 , 0
       0      .1       0  129.85     .06       0  252.49     .05       0
  731.57    .045       0  831.51      .1       0  844.19    .025       0
  865.65      .1       0  988.28     .05       0 1503.31      .1       0
Bank Sta=731.57,831.51
XS Rating Curve= 0 ,0
Exp/Cntr=0.3,0.1

Type RM Length L Ch R = 1 ,30417   ,409.4,409.3,415.9
XS GIS Cut Line= 2
2439603.23563844687827.1765133742440701.92635444 686720.65346396
#Sta/Elev= 30
       0 1610.39    51.1 1568.48    73.7 1551.38    90.1 1535.97     209 1447.55
   226.1 1427.28   234.6  1422.6   266.1 1421.44   296.8 1425.75   334.2 1425.31
   383.7 1428.33     475 1423.75   601.1 1423.75   686.2 1421.99   710.6 1419.55
   735.3 1422.24  751.681416.957     772 1412.31   879.2 1412.31  895.621416.773
   907.8 1421.16   947.4 1423.87   972.8 1431.92   989.8 1433.92  1054.9 1433.09
  1144.7 1435.88  1234.9 1441.29  1374.5 1452.62  1507.4 1468.77  1559.3 1479.91
#Mann= 9 ,-1 , 0
       0      .1       0  263.12     .06       0   348.7    .055       0
  385.88     .05       0  677.65      .1       0  751.68    .045       0
  895.62      .1       0 1122.39     .05       0 1500.04      .1       0
#XS Ineff= 2 , 0
                          994.91         1439.26
Permanent Ineff=
       F       F
Bank Sta=751.68,895.62
XS Rating Curve= 0 ,0
Exp/Cntr=0.3,0.1

Type RM Length L Ch R = 1 ,30007   ,516,526.4,536.9
XS GIS Cut Line= 2
2439841.91265452688100.1520172952440978.25979128 687081.05038096
#Sta/Elev= 30
       0 1584.27    97.8 1506.29   139.7 1475.39   154.4 1461.31   178.4 1444.73
   205.3 1432.99   217.6 1430.25   239.4 1429.92   253.6 1423.03   289.5 1421.24
   341.4  1426.3   383.9 1422.24   468.9 1423.01   547.1 1417.91   651.2 1422.08
   672.7 1416.35  703.261414.716   715.3 1412.32   844.7 1412.33  863.091415.957
   870.6 1421.77   876.9  1430.1   888.6 1437.54   925.3 1440.32  1140.2 1445.22
  1319.9  1453.3  1451.8 1462.97  1484.1 1467.23  1510.9 1473.87  1526.4 1475.56
#Mann= 8 ,-1 , 0
       0      .1       0   260.9     .06       0  404.34     .05       0
  583.17      .1       0  703.26    .045       0  863.09      .1       0
  968.84     .05       0 1477.29      .1       0
Bank Sta=703.26,863.09
XS Rating Curve= 0 ,0
Exp/Cntr=0.3,0.1

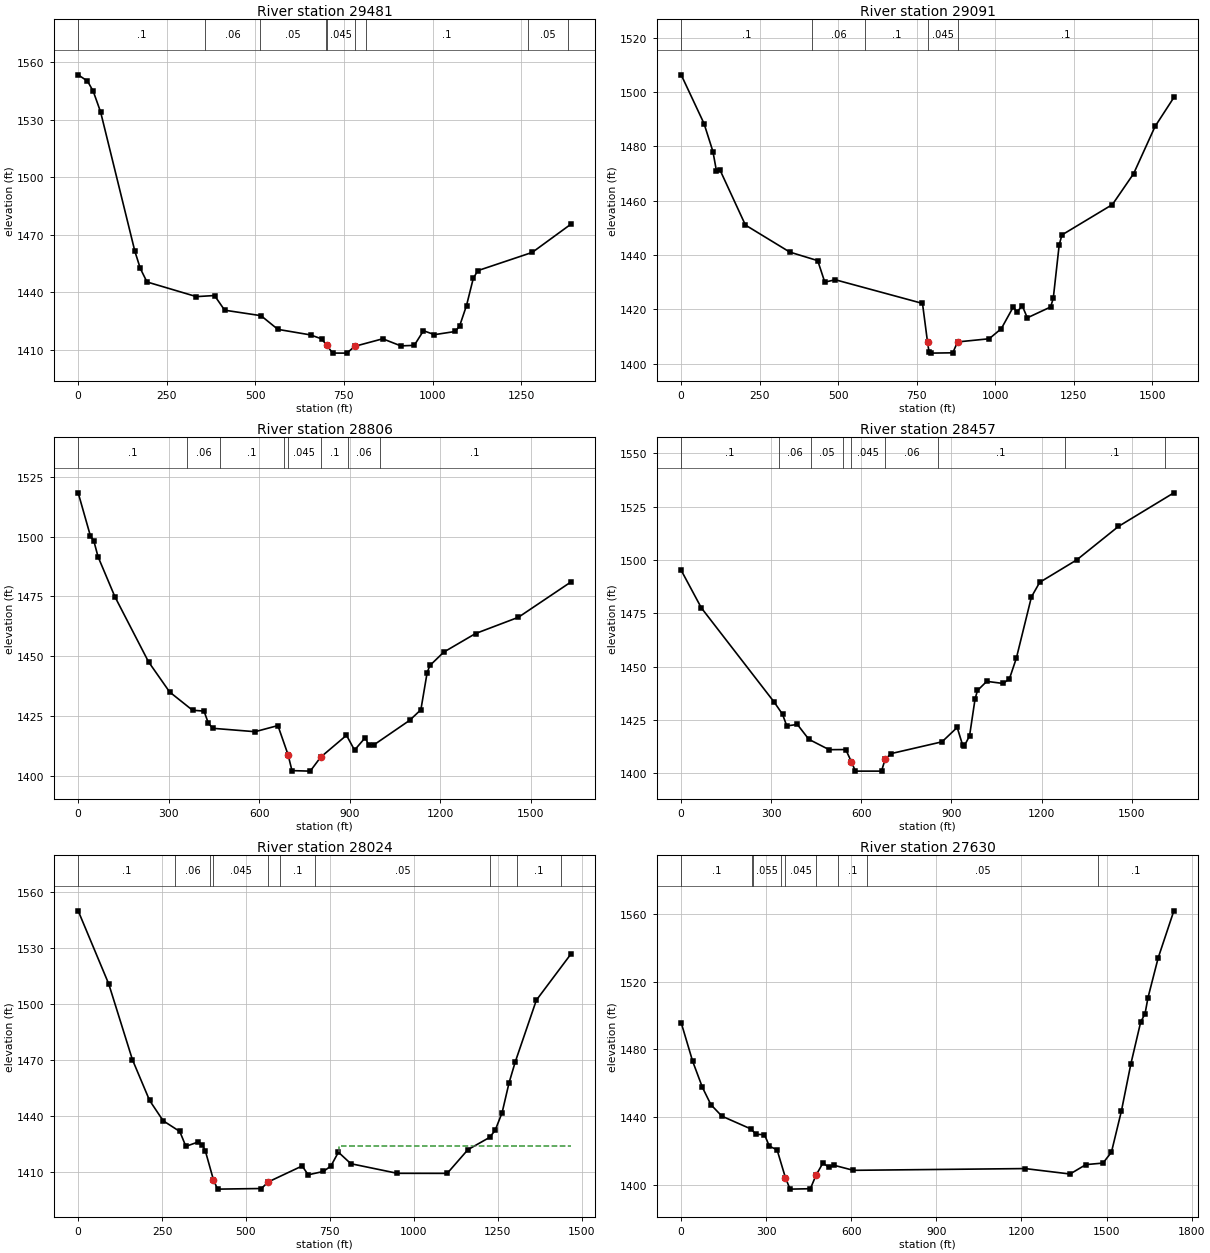
Type RM Length L Ch R = 1 ,29481   ,385.5,390.2,389
XS GIS Cut Line= 3
2440113.48625836688486.5173862872440605.96197945688095.114953876
2441199.64779994687618.530605212
#Sta/Elev= 30
       0 1553.25    26.3 1549.98    42.5  1544.7    63.3 1533.92   160.1 1461.36
   175.3  1452.5   194.2 1445.47   333.7 1437.84   384.8 1438.41   413.4 1430.78
   515.9 1427.93   563.6  1420.8   655.7 1417.92   686.7 1415.88  700.821412.736
     718 1408.47   758.3 1408.44  780.541411.984   859.5  1415.9   910.6 1412.21
   948.5 1412.48   974.5 1420.11  1005.4 1418.05  1063.9  1419.7  1076.5 1422.59
  1095.9 1433.18    1115 1447.32  1127.8 1451.36  1281.4 1460.85  1390.4 1475.51
#Mann= 9 ,-1 , 0
       0      .1       0  356.86     .06       0  513.24     .05       0
   698.6    .025       0  700.82    .045       0  780.54    .025       0
  812.76      .1       0 1269.41     .05       0 1383.57      .1       0
Bank Sta=700.82,780.54
XS Rating Curve= 0 ,0
Exp/Cntr=0.3,0.1

Type RM Length L Ch R = 1 ,29091   ,282.6,285.1,296
XS GIS Cut Line= 4
2440390.16976011688825.2171682122440861.99788469688368.370312884
2441350.06318152 687981.237228872441574.39278537687798.204130381
#Sta/Elev= 30
       0 1506.29    72.8 1488.35   101.1 1478.06   112.4 1470.87   124.1 1471.14
   204.6 1450.99     346 1441.03   434.9 1437.89   457.4 1429.97   490.8 1430.85
   768.6 1422.14  784.551407.977   789.3 1404.32   794.3 1403.84   865.1 1403.96
  880.391407.962     981 1409.13  1019.6 1412.84  1058.2 1420.93  1068.3 1418.95
  1086.6  1421.2  1102.5 1416.84  1176.5 1420.82  1185.1    1424    1204 1443.69
  1212.7 1447.35  1373.5 1458.54  1441.1 1469.92  1509.3 1487.27  1569.2 1497.95
#Mann= 5 ,-1 , 0
       0      .1       0  417.39     .06       0  586.42      .1       0
  784.55    .045       0  880.39      .1       0
Bank Sta=784.55,880.39
XS Rating Curve= 0 ,0
Exp/Cntr=0.3,0.1

Type RM Length L Ch R = 1 ,28806   ,342.3,348.2,339.6
XS GIS Cut Line= 3
 2440550.3151091688853.8450637162441295.39760843688410.087421045
 2441982.3145417688073.909287632
#Sta/Elev= 30
       0 1518.27    40.4 1500.29    51.7 1498.24    65.7 1491.58   121.5 1474.86
     233  1447.6     303 1434.97   378.9 1427.34   416.8 1426.99   431.4 1421.87
     446 1419.79     586 1418.37   661.6 1420.93  695.371408.689   708.2 1402.09
   768.7 1401.88  803.281407.719   888.8 1416.87   915.5 1410.67   951.1 1415.91
   961.8 1412.84   979.8 1412.88  1098.1 1423.13  1135.2 1427.56    1156  1443.1
  1165.1 1446.06  1211.2 1451.67  1316.3 1459.42  1458.2 1466.22    1632 1480.96
#Mann= 8 ,-1 , 0
       0      .1       0  361.46     .06       0  468.26      .1       0
  681.84    .025       0  695.37    .045       0  803.28      .1       0
  894.63     .06       0  998.41      .1       0
Bank Sta=695.37,803.28
XS Rating Curve= 0 ,0
Exp/Cntr=0.3,0.1

Type RM Length L Ch R = 1 ,28457   ,434.7,433.1,434.7
XS GIS Cut Line= 3
2440816.01011577689066.4860426342441981.12458345688416.807880044
2442256.75920278688282.350471795
#Sta/Elev= 30
       0 1495.15    67.2  1477.5     310 1433.26   337.5 1427.62   351.6 1422.15
   386.9 1422.83   425.1 1415.87   492.7    1411   548.1 1411.06  567.151405.198
   580.2 1400.94   667.2 1400.94  678.991406.458   699.3 1409.17   868.7 1414.69
   919.1 1421.44   937.4 1413.12   942.6 1412.69   960.3 1417.44   978.6 1434.71
   986.7 1438.76  1017.6 1443.05    1072 1442.06  1093.1 1444.23  1116.1 1453.88
  1166.4 1482.65  1193.9 1489.49  1317.5 1500.04    1456  1515.7  1640.7 1531.48
#Mann= 9 ,-1 , 0
       0      .1       0  326.08     .06       0  431.73     .05       0
  537.38      .1       0  567.15    .045       0  678.99     .06       0
  854.31      .1       0  1276.9      .1       0 1610.17      .1       0
Bank Sta=567.15,678.99
XS Rating Curve= 0 ,0
Exp/Cntr=0.3,0.1

Type RM Length L Ch R = 1 ,28024   ,387.5,394.2,405
XS GIS Cut Line= 2
 2441101.7234551689383.6277967992442406.12537387688710.150797293
#Sta/Elev= 30
       0 1549.76    91.2 1510.51   161.6 1470.01   212.7 1448.18   253.2 1437.26
   302.8 1431.51   320.8 1423.55   356.8 1425.83   370.3 1424.32   379.3 1420.85
   402.91405.687   415.3 1400.62   545.9 1400.95  566.46 1404.49   667.4 1413.03
   685.4 1408.29   730.4 1410.08   752.9 1412.97   775.4 1420.41   812.5 1414.24
     951 1409.09  1099.6 1409.06  1161.2 1421.76  1225.6 1428.31  1242.3 1432.06
  1263.1 1441.56  1283.8 1457.55  1302.1 1468.67  1365.2 1501.88    1468 1526.56
#Mann= 10 ,-1 , 0
       0      .1       0  288.15     .06       0  392.64      .1       0
   402.9    .045       0  566.46    .025       0  601.61      .1       0
  706.09     .05       0 1228.52      .1       0 1306.91      .1       0
 1437.49      .1       0
#XS Ineff= 2 , 0
                          775.93         1423.73
Permanent Ineff=
       F       F
Bank Sta=402.9,566.46
XS Rating Curve= 0 ,0
Exp/Cntr=0.5,0.3

Type RM Length L Ch R = 1 ,27630   ,16.7,17.5,18.2
XS GIS Cut Line= 2
2441281.05282086689683.1449142992442899.79006895689052.349587962
#Sta/Elev= 30
       0  1495.8    40.5 1473.03    74.8 1457.69   104.8 1447.46   143.5 1440.69
   246.5  1433.1   263.7 1429.95   293.7 1429.81   310.9 1422.99   338.2 1420.83
  367.431404.488   383.9 1397.66   455.6  1397.9  475.261405.788   499.8 1413.05
   521.3 1410.52   538.4 1411.76   607.1 1408.75  1212.5 1409.78  1371.3 1406.58
  1427.1 1412.12  1487.4 1413.02  1517.2 1419.45  1552.3 1443.69  1585.9 1471.67
  1620.2  1496.1  1635.7 1501.12    1646  1510.5    1682    1534  1737.3 1561.76
#Mann= 9 ,-1 , 0
       0      .1       0  249.65     .06       0  254.49    .055       0
  351.22      .1       0  367.43    .045       0  475.26    .055       0
  554.35      .1       0  655.91     .05       0 1468.43      .1       0
#XS Ineff= 2 , 0
          362.43 1404.13  480.26         1404.13
Permanent Ineff=
       F       F
Bank Sta=367.43,475.26
XS Rating Curve= 0 ,0
Exp/Cntr=0.5,0.3

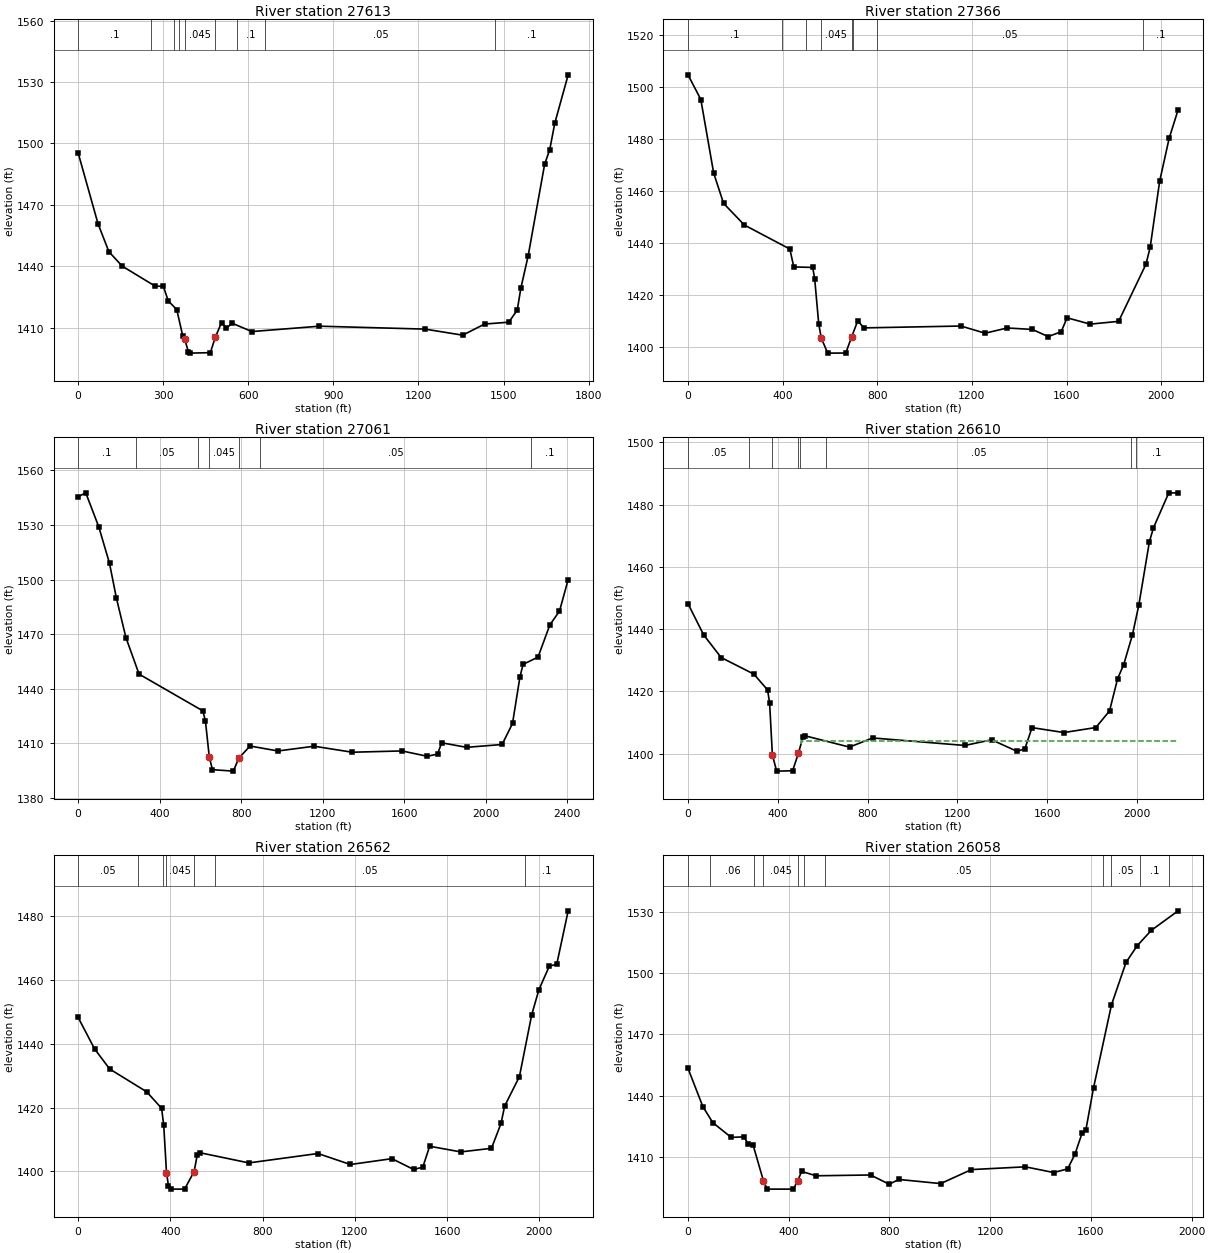
Type RM Length L Ch R = 1 ,27613   ,245.1,246.6,249
XS GIS Cut Line= 2
2441276.91634619 689697.40275979 2442894.8205907689091.336058542
#Sta/Elev= 30
       0 1495.56    70.3 1460.86   108.7 1447.18   155.7 1440.12   271.1 1430.42
     301  1430.2     318 1423.13   347.9 1418.93   369.3 1405.93  375.931404.557
   388.7 1398.39   394.9 1397.66   466.4 1397.89  483.911405.462     506 1412.61
   523.1 1409.89   543.1 1412.26   612.8 1408.19     851 1410.81  1223.6 1409.38
    1356 1406.42  1432.9 1411.85  1518.3 1412.76  1548.2 1418.66    1561 1429.41
  1586.7 1445.18  1644.8  1489.9  1662.7 1496.97  1680.6 1509.96  1727.7 1533.52
#Mann= 9 ,-1 , 0
       0      .1       0  255.47     .06       0  336.95    .055       0
  356.75      .1       0  375.93    .045       0  483.91    .055       0
  559.33      .1       0  660.62     .05       0 1470.92      .1       0
Bank Sta=375.93,483.91
XS Rating Curve= 0 ,0
Exp/Cntr=0.5,0.3

Type RM Length L Ch R = 1 ,27366   ,310.6,304.7,302.8
XS GIS Cut Line= 4
2441174.86602536689962.1256555472441637.24436569 689821.99896729
2442283.28605261689598.0197564662443097.03212851689203.116018713
#Sta/Elev= 30
       0 1504.77    54.2 1495.27   108.5 1466.94   150.3 1455.31   238.1 1446.97
   430.4 1437.72   447.1 1430.84   527.1 1430.64   535.5 1426.15   552.5 1408.92
  563.121403.502   590.3 1397.66   666.8  1397.7  691.071403.787   717.6 1410.15
     743 1407.37  1153.6 1408.09  1255.7 1405.32  1348.6 1407.34  1455.3 1406.78
    1522 1404.03  1577.2 1405.89    1602 1411.26  1699.8 1408.82  1819.9 1409.89
  1935.5 1431.89  1953.3 1438.41  1993.3 1463.79  2033.3 1480.28  2071.4 1491.32
#Mann= 8 ,-1 , 0
       0      .1       0  397.12     .06       0  497.42      .1       0
  563.12    .045       0  691.07    .025       0  699.06      .1       0
  799.88     .05       0 1924.44      .1       0
Bank Sta=563.12,691.07
XS Rating Curve= 0 ,0
Exp/Cntr=0.3,0.1

Type RM Length L Ch R = 1 ,27061   ,466.8,451.6,430.4
XS GIS Cut Line= 3
2441151.48713511690335.0520750432442125.51996395689960.096788213
2443283.00518176 689245.18220754
#Sta/Elev= 30
       0 1545.54    37.8 1547.71   102.1 1528.87   154.3 1508.96   188.3 1489.78
   234.8 1468.15   299.2 1448.06   612.3 1427.85     625 1422.14  643.821402.468
   659.3 1395.53   762.1 1394.73  787.781401.748   843.6 1408.53   980.6 1405.81
    1158 1408.42  1344.8 1405.12    1589 1405.83  1712.8  1402.9  1763.3 1404.09
  1783.7  1410.3  1905.8 1407.81  2080.1 1409.37  2131.2 1420.92  2167.3 1446.31
  2182.9 1453.41  2256.3 1457.41  2314.5 1475.15  2361.6 1482.67  2404.2 1500.01
#Mann= 7 ,-1 , 0
       0      .1       0  283.76     .05       0  588.19     .06       0
  643.82    .045       0  787.78      .1       0  892.62     .05       0
  2222.7      .1       0
Bank Sta=643.82,787.78
XS Rating Curve= 0 ,0
Exp/Cntr=0.5,0.3

Type RM Length L Ch R = 1 ,26610   ,46.7,48.1,49.6
XS GIS Cut Line= 2
2441659.55436045690749.8665341292443379.38655069689405.607083544
#Sta/Elev= 30
       0 1448.18    69.8 1438.15   147.7 1430.88   293.4 1425.55   354.4 1420.48
   363.4 1416.35   375.81399.591   394.8 1394.38     466  1394.5  491.741400.141
   511.7 1405.23     523  1405.7   719.3  1402.1   822.2 1405.04  1232.7 1402.63
  1352.3 1404.45  1466.3 1400.72  1500.4 1401.58  1532.2 1408.36  1674.4 1406.78
  1816.5 1408.39  1877.4 1413.73  1913.6 1424.14  1940.4 1428.58  1979.4 1438.17
  2007.7 1447.68  2055.1 1468.14  2073.2  1472.6  2141.4 1483.81  2182.9 1483.76
#Mann= 8 ,-1 , 0
       0     .05       0  273.71     .06       0   375.8    .045       0
  491.74    .025       0  500.38      .1       0  613.72     .05       0
 1973.77      .1       0 1993.57      .1       0
#XS Ineff= 2 ,-1
       0   362.8  1404.2  503.74 2182.86  1404.2
Permanent Ineff=
       F       F
Bank Sta=375.8,491.74
XS Rating Curve= 0 ,0
Exp/Cntr=0.5,0.3

Type RM Length L Ch R = 1 ,26562   ,503.3,503.8,501
XS GIS Cut Line= 2
2441676.35288328 690784.863183292443380.22644404689515.007455289
#Sta/Elev= 30
       0 1448.32    71.7 1438.39   137.2 1432.08   297.5 1424.93   362.2 1419.76
   371.5 1414.43  383.461399.573   392.1  1395.4   403.3 1394.39   461.9 1394.38
  503.291399.911   516.8  1405.1   526.8 1405.83   740.6 1402.61    1040 1405.56
  1180.8 1402.11  1360.9 1403.94  1454.7 1400.56  1494.6 1401.26  1524.5 1407.84
  1659.2 1406.06  1792.5 1407.19  1833.8 1414.99  1849.6 1420.46  1913.6 1429.68
  1966.8 1449.06    1998 1456.95  2043.4 1464.39  2075.5 1464.95    2125 1481.73
#Mann= 7 ,-1 , 0
       0     .05       0  257.98     .06       0  369.94      .1       0
  383.46    .045       0  503.29      .1       0  593.84     .05       0
 1937.28      .1       0
Bank Sta=383.46,503.29
XS Rating Curve= 0 ,0
Exp/Cntr=0.5,0.3

Type RM Length L Ch R = 1 ,26058   ,539.5,517.8,493.8
XS GIS Cut Line= 2
2442084.37437695691114.7647544592443610.09737536689906.602800712
#Sta/Elev= 30
       0 1453.37    59.1 1434.67    98.4 1426.88   171.4 1419.66   222.4 1419.92
   237.7 1416.65   257.9 1416.14  299.711398.368   314.3 1394.38   418.6 1394.38
  435.591398.558   451.5 1403.01   508.4  1400.9   724.8 1401.29   798.8 1396.78
   837.4 1399.11  1003.1 1397.08  1125.5 1403.93  1339.8 1405.28  1452.1 1402.48
  1507.5 1404.27  1536.4 1411.44  1564.3 1421.58  1579.6 1423.16  1610.2 1443.86
  1681.5 1484.45  1739.5 1505.23  1784.1 1513.39  1839.8 1520.83  1946.1 1530.36
#Mann= 11 ,-1 , 0
       0      .1       0   88.78     .06       0  263.18     .05       0
  299.71    .045       0  435.59    .025       0     461      .1       0
  543.72     .05       0  1647.9      .1       0 1681.07     .05       0
 1794.81      .1       0 1908.54     .05       0
Bank Sta=299.71,435.59
XS Rating Curve= 0 ,0
Exp/Cntr=0.3,0.1