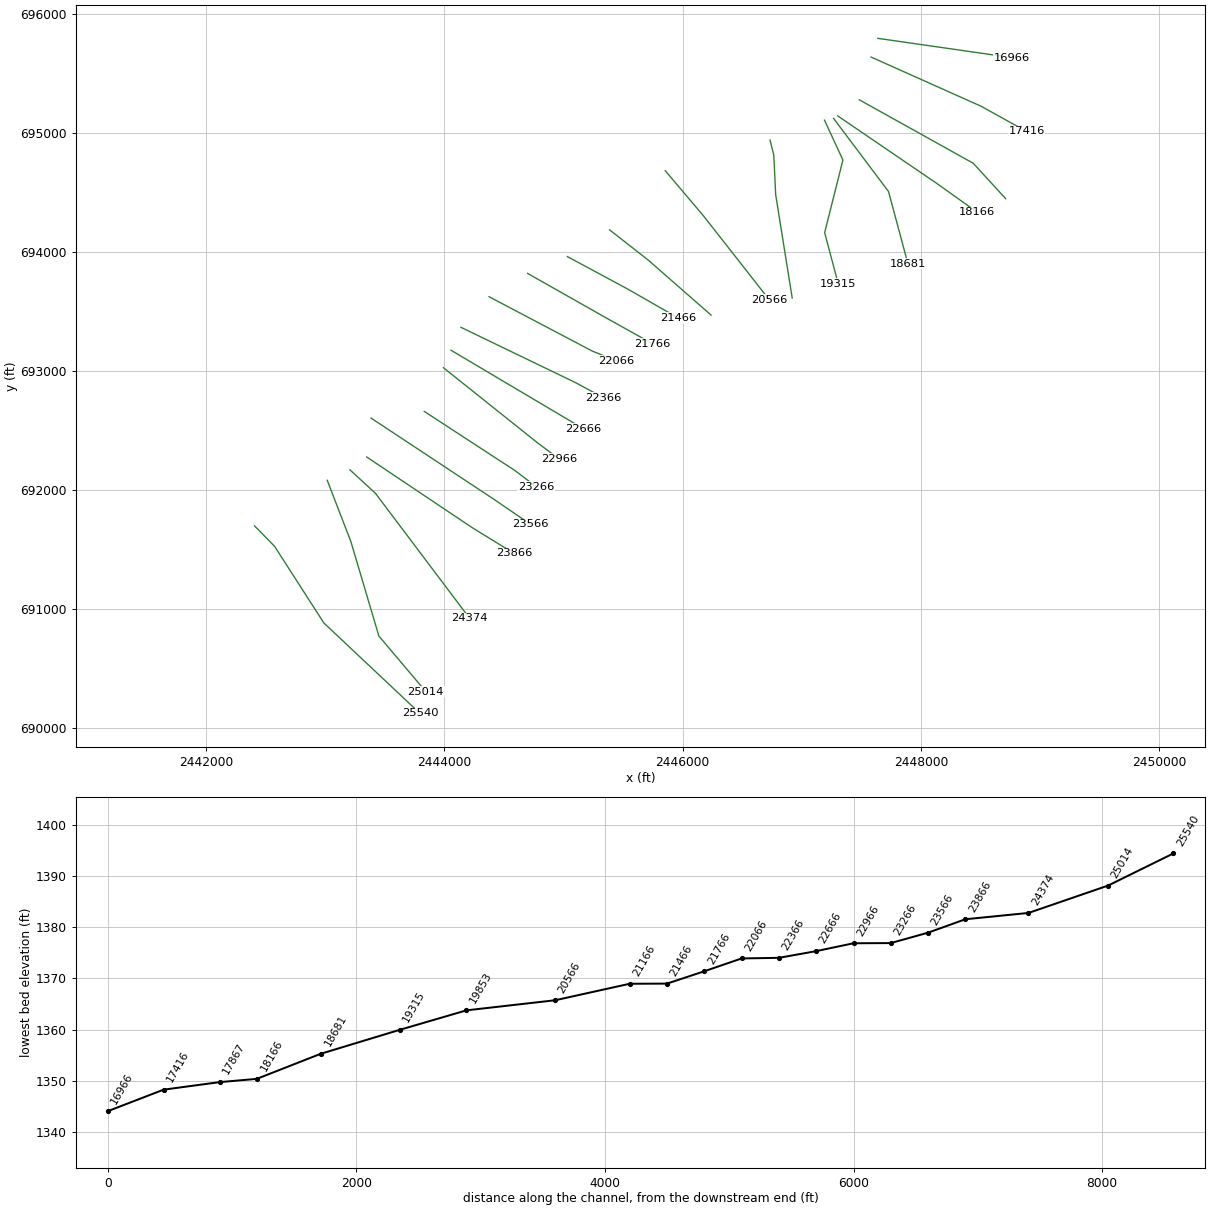
HEC-RAS study NFSBPOTOMC.prj: NFSBPOTOMC

--- NFSBPOTOMC.g01 (geometry) --- (continued)

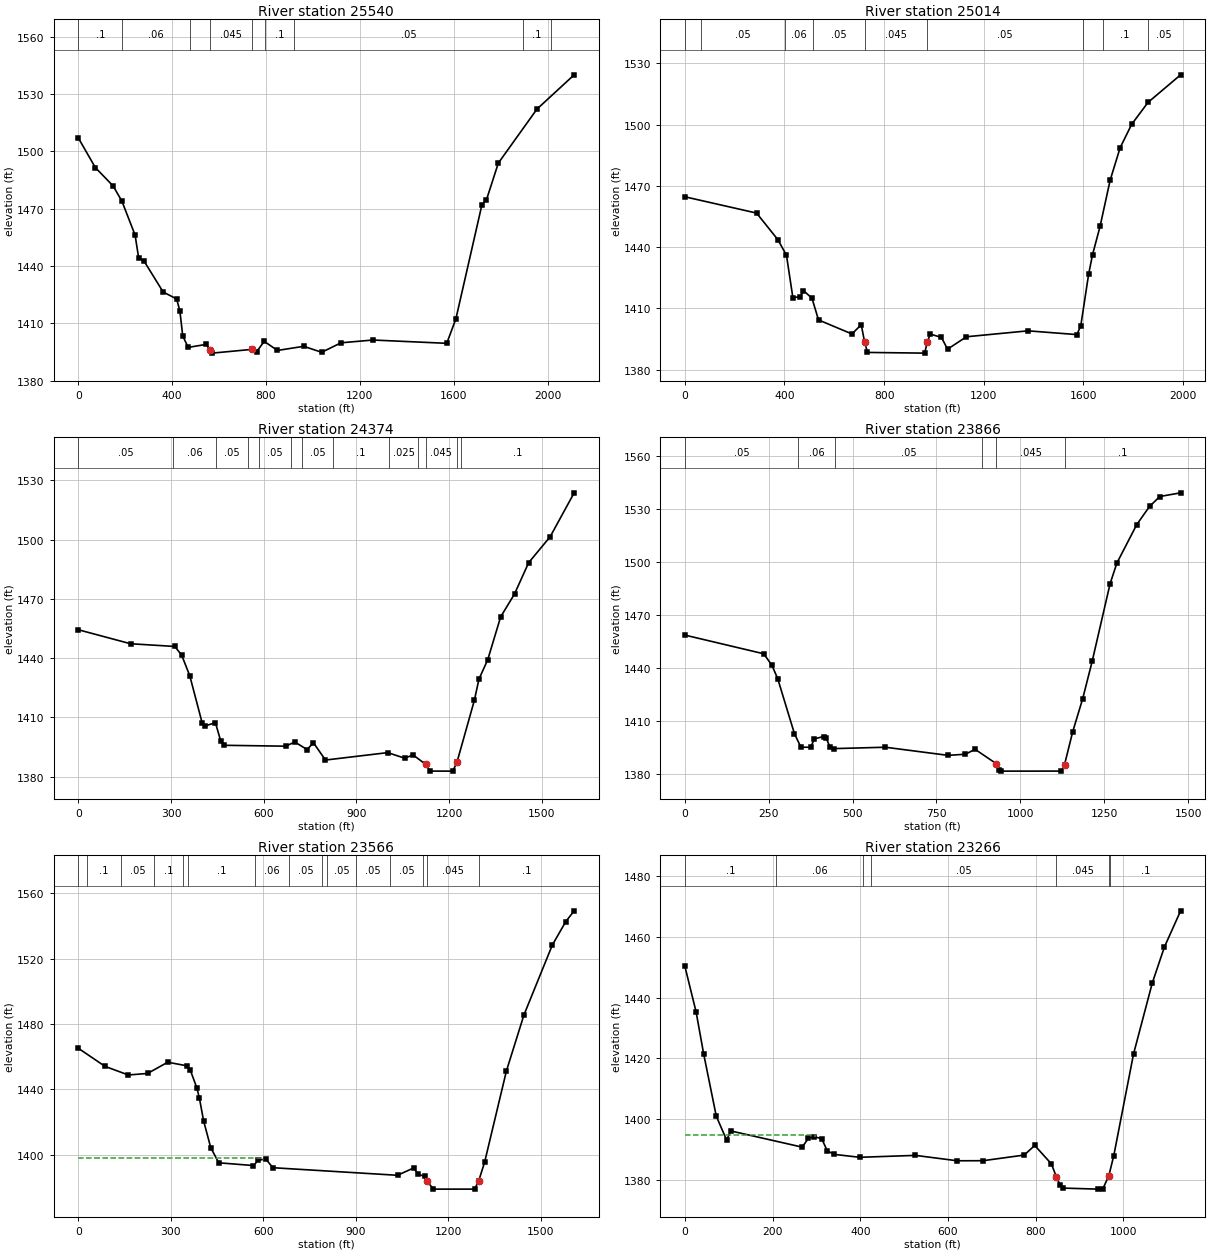
Type RM Length L Ch R = 1 ,25540   ,536.7,526.1,492.6
XS GIS Cut Line= 4
2442405.70411485 691696.571989792442573.40948811691525.647462875
2442987.49264944690881.2146966312443794.09930393690121.571858957
#Sta/Elev= 30
       0 1506.98    72.6 1491.48   148.1  1481.9   185.8  1473.9   241.9 1456.16
   256.9 1444.39   278.9  1442.8   361.6 1426.37     419 1422.73   432.9 1416.46
     445 1403.41   468.2 1397.37   545.3 1398.96  562.621396.053   570.8 1394.38
  742.151396.366   760.6 1395.23   792.4 1400.54   848.7 1395.78   960.7 1397.94
  1037.4 1394.82  1119.7 1399.78  1255.6 1401.24  1570.4 1399.51  1609.3 1412.28
  1720.6 1472.16  1739.5 1474.54  1790.2 1493.83    1955  1522.1  2113.5 1540.03
#Mann= 9 ,-1 , 0
       0      .1       0  187.93     .06       0  474.58      .1       0
  562.62    .045       0  742.15    .025       0  795.06      .1       0
  920.45     .05       0 1896.07      .1       0 2015.97     .05       0
Bank Sta=562.62,742.15
XS Rating Curve= 0 ,0
Exp/Cntr=0.3,0.1

Type RM Length L Ch R = 1 ,25014   ,687.6,639.9,670.1
XS GIS Cut Line= 4
2443015.91057161692079.7185332182443215.25269261 691562.04404363
2443449.38148943690771.4639318732443843.23536053690304.675167292
#Sta/Elev= 30
       0  1464.7   288.1 1456.71   373.8 1443.64   408.1 1436.02   433.8 1415.24
   463.8 1415.81   476.3 1418.73   510.4    1415   536.7 1404.36   670.7 1397.49
   708.2    1402  722.021393.318   733.2 1388.44   962.7  1388.1  972.961393.338
   984.9 1397.44    1030  1395.8  1054.5 1390.04  1130.5 1396.12  1377.6 1399.02
  1573.6 1397.18  1589.3  1401.5  1620.7 1426.71  1636.4  1436.3  1666.7 1450.21
  1707.1  1472.8  1747.3 1488.75  1793.5 1500.18    1859 1510.92    1990 1524.44
#Mann= 9 ,-1 , 0
       0     .06       0   64.37     .05       0  401.89     .06       0
  514.39     .05       0  722.02    .045       0  972.96     .05       0
 1596.54      .1       0 1676.66      .1       0 1858.29     .05       0
Bank Sta=722.02,972.96
XS Rating Curve= 0 ,0
Exp/Cntr=0.3,0.1

Type RM Length L Ch R = 1 ,24374   ,509.6,507.7,532.5
XS GIS Cut Line= 3
2443206.40330085692167.6960475442443420.54230827691970.606874794
2444210.99479562690920.740864292
#Sta/Elev= 30
       0 1454.33     169 1447.25   312.4 1445.87   334.6 1441.46   360.8 1431.04
   400.9 1407.14   409.5 1405.59   443.8  1407.3   460.9 1398.06   470.9 1395.84
   671.2 1395.39   700.9 1397.51   740.9 1393.64   760.9 1397.18   800.1 1388.37
  1001.7 1392.13  1056.7  1389.3  1083.6 1390.97 1124.661386.179  1139.3 1382.78
  1212.2 1382.76 1225.731387.232  1282.1 1418.59  1297.1 1429.39  1325.5 1439.19
  1367.2 1460.85  1412.1 1472.43  1457.8 1488.28  1527.4  1501.4  1605.2 1523.65
#Mann= 13 ,-1 , 0
       0     .05       0  305.52     .06       0  445.45     .05       0
  549.68     .05       0  585.38     .05       0  687.32     .05       0
  725.31     .05       0  824.95      .1       0 1005.16    .025       0
 1100.22     .05       0 1124.66    .045       0 1225.73    .025       0
 1237.86      .1       0
Bank Sta=1124.66,1225.73
XS Rating Curve= 0 ,0
Exp/Cntr=0.3,0.1

Type RM Length L Ch R = 1 ,23866   ,303.8,300,297
XS GIS Cut Line= 3
2443347.25505328692275.7010808742444234.58300301691680.956535459
2444583.40021878691466.441544548
#Sta/Elev= 30
       0 1458.51   235.3 1447.92   259.7 1441.38     277 1433.79   326.8  1402.7
   346.2 1395.03     375 1395.06   386.5 1399.79   413.5 1401.12   421.1 1400.32
   432.7 1395.16   444.2 1394.27   597.8 1395.05   784.3 1390.46   836.3 1391.08
   865.1 1393.88   928.71385.693   935.4 1382.21   942.6 1381.53  1122.2 1381.55
 1131.82 1385.28  1156.1 1403.85  1185.8 1422.49    1214  1443.6  1267.6 1487.66
  1287.9 1499.32    1347 1521.03  1385.2 1531.33  1415.8 1536.91  1477.7 1538.99
#Mann= 6 ,-1 , 0
       0     .05       0  338.59     .06       0  447.84     .05       0
  884.84      .1       0   928.7    .045       0 1131.82      .1       0
Bank Sta=928.7,1131.82
XS Rating Curve= 0 ,0
Exp/Cntr=0.3,0.1

Type RM Length L Ch R = 1 ,23566   ,304.2,300,296.5
XS GIS Cut Line= 3
 2443383.6519621 692602.712237882444406.76572952691925.976058543
2444721.09318486691710.988299549
#Sta/Elev= 30
       0 1465.14    86.7 1454.04     162 1448.79   224.4 1449.72   289.7 1456.59
   353.8 1454.35   363.4 1451.57     384 1441.01   392.2 1434.93   406.2 1420.64
   429.3 1404.28   455.3 1395.02   567.9 1393.34     584  1396.7   608.3 1397.24
   630.5 1392.02  1034.8 1387.38  1087.3 1391.89  1101.9 1387.91  1123.5 1386.78
 1130.78 1383.81    1151 1378.91  1284.8 1378.91 1298.081383.989  1317.2  1395.4
    1388 1451.35  1444.7 1485.54  1536.8 1528.38  1580.4 1542.71  1607.5 1549.28
#Mann= 15 ,-1 , 0
       0     .06       0   28.81      .1       0  137.76     .05       0
   246.7      .1       0  338.88     .05       0  355.65      .1       0
  572.73     .06       0  682.49     .05       0  791.44     .05       0
  806.58     .05       0  900.39     .05       0 1009.33     .05       0
 1118.28    .025       0 1130.78    .045       0 1298.08      .1       0
#XS Ineff= 2 , 0
           598.3 1397.94
Permanent Ineff=
       F       F
Bank Sta=1130.78,1298.08
XS Rating Curve= 0 ,0
Exp/Cntr=0.3,0.1

Type RM Length L Ch R = 1 ,23266   ,306.1,300,300.8
XS GIS Cut Line= 3
2443830.71701285692658.538897872 2444593.3624692 692160.88274096
2444768.07373393692027.752101704
#Sta/Elev= 30
       0 1450.41    25.8 1435.25      43 1421.45    71.7 1400.95    95.1 1393.12
   105.1 1396.05   267.5 1390.72   281.8 1393.62   294.6 1394.12   311.9 1393.56
   324.8 1389.48   340.8 1388.33   398.6 1387.37   525.8    1388   621.2 1386.22
   680.1 1386.25   773.8 1388.11   797.7 1391.28   835.9 1385.17  846.751381.011
   855.3 1378.34   863.1 1377.22   941.6 1376.88     953 1376.99  966.571381.255
   977.8 1387.84    1023 1421.45  1065.7 1444.82  1093.4 1456.69  1130.3 1468.59
#Mann= 7 ,-1 , 0
       0      .1       0  207.61     .06       0  407.36     .05       0
   424.9     .05       0  846.75    .045       0  966.57    .025       0
  970.21      .1       0
#XS Ineff= 2 , 0
          296.44 1394.67
Permanent Ineff=
       F       F
Bank Sta=846.75,966.57
XS Rating Curve= 0 ,0
Exp/Cntr=0.3,0.1

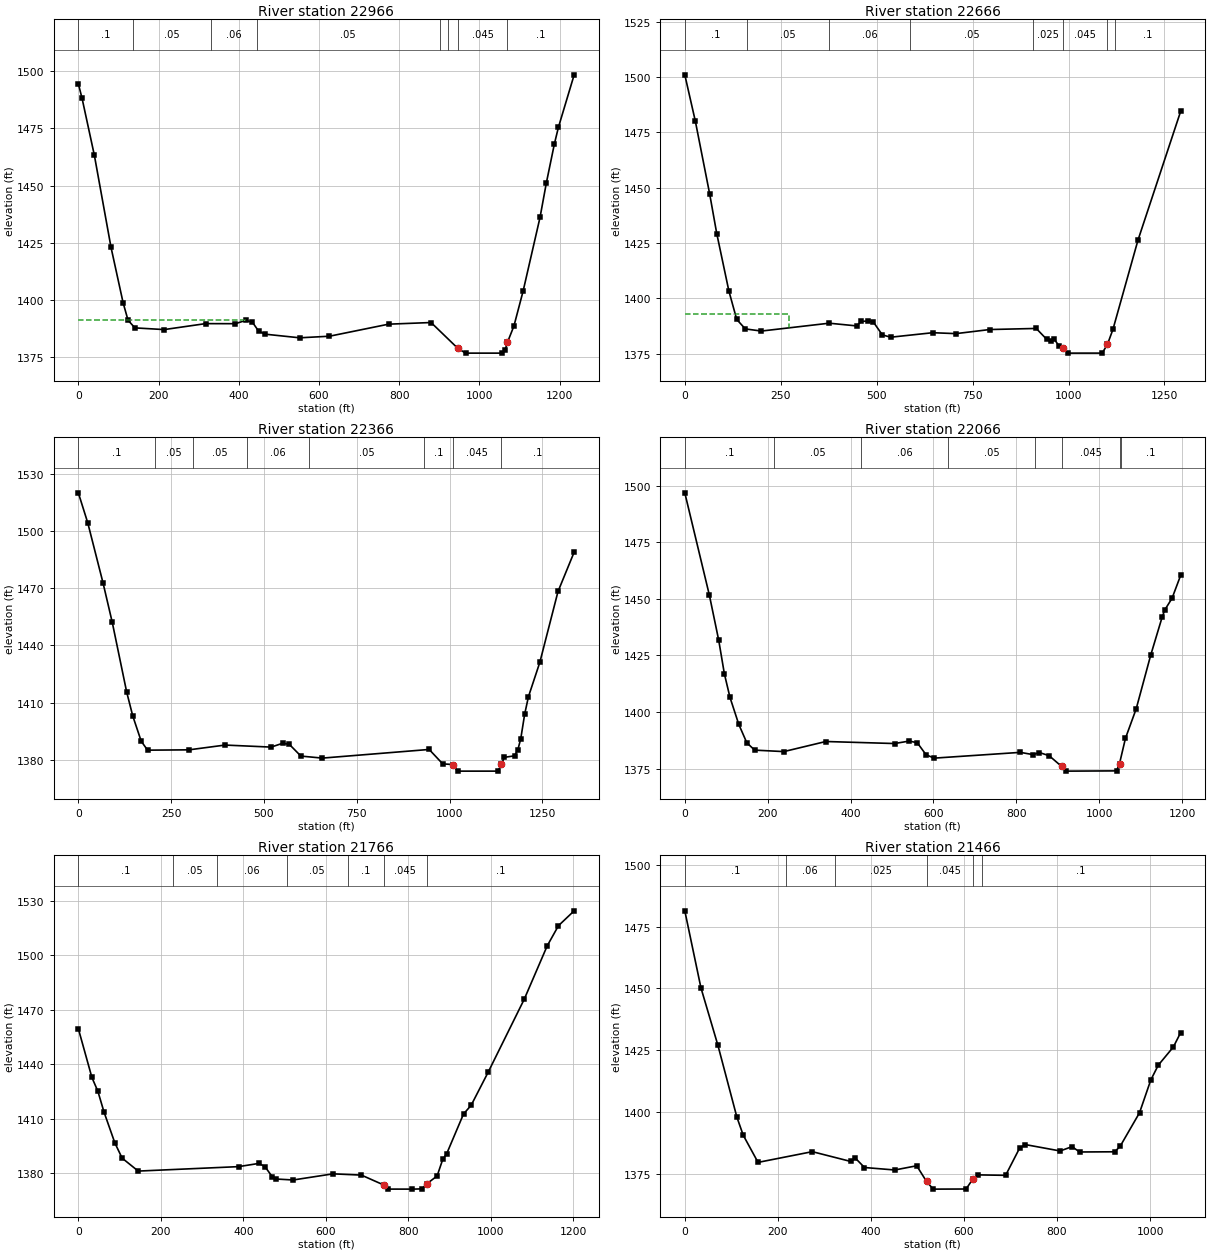
Type RM Length L Ch R = 1 ,22966   ,291.3,300,305.8
XS GIS Cut Line= 3
2443991.47981468693025.7550269662444781.05402294692394.917049795
2444962.26560277692260.075455964
#Sta/Elev= 30
       0 1494.43     9.3 1488.08      40 1463.19    81.5 1423.03   111.7 1398.81
   123.9 1391.23     141 1387.86   214.1 1387.12   317.4 1389.72   391.4 1389.69
     417 1391.09   433.9  1390.4   449.6 1386.45   465.4 1385.12     552 1383.53
   626.2 1384.22   773.6 1389.48   879.7  1390.2  946.721378.868   965.8 1376.84
  1057.6 1376.84  1064.3 1378.16 1070.071381.523  1086.2 1388.63  1109.1 1403.85
  1151.4 1436.12  1167.3 1451.28  1187.2 1468.18  1197.2  1475.4  1236.5 1498.34
#Mann= 8 ,-1 , 0
       0      .1       0  135.73     .05       0  331.18     .06       0
   445.2     .05       0  901.25      .1       0  920.98    .025       0
  946.72    .045       0 1070.07      .1       0
#XS Ineff= 2 , 0
          416.28 1391.48
Permanent Ineff=
       F       F
Bank Sta=946.72,1070.07
XS Rating Curve= 0 ,0
Exp/Cntr=0.3,0.1

Type RM Length L Ch R = 1 ,22666   ,294.6,300,302.6
XS GIS Cut Line= 3
2444055.09057987693172.6300612992444954.64389884692638.920826882
2445166.53619161692513.396471635
#Sta/Elev= 30
       0 1501.03    27.5 1480.07    64.7 1447.33    83.3  1429.3   114.9 1403.37
   135.3 1390.53   157.7 1386.25   199.5 1385.28   376.3 1388.83   447.6 1387.61
   460.1 1389.63   478.7 1389.84   491.4 1389.35   514.8 1383.56   536.5  1382.5
   646.1 1384.53   706.6 1384.12   794.9 1385.97   915.9 1386.46   943.2 1381.54
   953.1 1380.71   962.4 1381.67   976.3 1378.34  986.081377.561   999.4 1375.31
  1087.9 1375.32 1101.581379.322  1115.8 1386.03  1180.9 1426.26  1292.2  1484.5
#Mann= 8 ,-1 , 0
       0      .1       0  161.07     .05       0  374.51     .06       0
  587.96     .05       0  908.12    .025       0  986.08    .045       0
 1101.58    .025       0 1121.55      .1       0
#XS Ineff= 2 , 0
          270.66 1393.17
Permanent Ineff=
       F       F
Bank Sta=986.08,1101.58
XS Rating Curve= 0 ,0
Exp/Cntr=0.3,0.1

Type RM Length L Ch R = 1 ,22366   ,302.4,300,307.5
XS GIS Cut Line= 3
2444138.80333894693364.9731805472445104.13605395692898.780871466
2445335.97843802692773.101660877
#Sta/Elev= 30
       0 1520.16    25.5 1504.32    66.6  1472.8    91.4 1452.13   130.3 1415.48
   146.5 1403.05   169.3 1389.75   186.5 1385.01   298.1 1385.18   395.3 1387.69
   519.4 1386.62   550.7 1388.65   568.5 1388.04   599.6  1381.9   657.4 1380.84
   945.1 1385.38   981.6 1377.81 1008.251377.478  1021.6    1374  1130.5    1374
 1139.941377.706  1147.6 1381.25  1175.1 1382.02  1184.2 1385.34  1191.9 1391.07
  1202.4 1403.94  1212.5 1413.06  1243.3 1431.19  1292.2 1468.34  1335.7 1489.02
#Mann= 8 ,-1 , 0
       0      .1       0   205.9     .05       0  309.52     .05       0
  455.02     .06       0  620.37     .05       0  931.23      .1       0
 1008.25    .045       0 1139.94      .1       0
Bank Sta=1008.25,1139.94
XS Rating Curve= 0 ,0
Exp/Cntr=0.3,0.1

Type RM Length L Ch R = 1 ,22066   ,302.7,300,292.2
XS GIS Cut Line= 3
2444374.26382601693622.2708942892445242.60887411693164.910916626
2445442.09010243693083.874333292
#Sta/Elev= 30
       0 1496.85    59.3 1451.64    81.9 1431.68    95.5  1416.9     109 1406.49
   130.2 1394.58   149.7 1386.39   168.7 1383.16     239 1382.51   340.4 1386.97
   506.3 1386.07   541.8 1387.17   561.1 1386.41   582.3 1381.12   601.8 1379.62
   809.8 1382.17   840.9 1381.16   855.7  1382.1   879.4 1380.69  909.621375.938
   920.8 1373.88    1042 1373.99 1049.211377.212  1063.6 1388.41  1089.5 1401.43
  1124.3 1425.01  1151.9 1441.81  1158.6 1445.17  1175.9 1450.21  1196.7 1460.35
#Mann= 8 ,-1 , 0
       0      .1       0  215.97     .05       0  425.51     .06       0
  635.05     .05       0  844.58    .025       0  909.62    .045       0
 1049.21    .025       0 1052.12      .1       0
Bank Sta=909.62,1049.21
XS Rating Curve= 0 ,0
Exp/Cntr=0.3,0.1

Type RM Length L Ch R = 1 ,21766   ,298.9,300,299.3
XS GIS Cut Line= 3
2444697.52433437693818.4768667072445387.32643244693427.678435713
2445745.07538885 693228.41472663
#Sta/Elev= 30
       0 1459.68    32.9 1432.82    47.4 1425.22    62.2 1413.85    88.6 1396.78
   106.2 1388.44   145.2 1381.31   388.7 1383.76   437.9 1385.53   452.5 1383.77
   470.3 1378.18   479.5 1376.95   520.9 1376.41   617.4 1379.79   686.4  1379.1
  741.021373.617   750.8  1371.4   809.9 1371.38   833.4 1371.52   844.51374.233
     870 1378.62   883.7 1387.81   893.1 1390.81   934.1 1412.77   952.4 1417.46
   993.6 1435.65  1081.2 1475.85    1137 1505.27  1164.3 1516.36  1202.3 1524.52
#Mann= 7 ,-1 , 0
       0      .1       0  229.93     .05       0  335.16     .06       0
  505.85     .05       0  652.89      .1       0  741.02    .045       0
   844.5      .1       0
Bank Sta=741.02,844.5
XS Rating Curve= 0 ,0
Exp/Cntr=0.3,0.1

Type RM Length L Ch R = 1 ,21466   ,307.9,300,290.6
XS GIS Cut Line= 3
2445032.09617177 693959.30401288 2445528.4390111693692.396082133
2445964.13433394693443.025189787
#Sta/Elev= 30
       0 1481.36    34.7 1450.26    71.1 1427.09     112    1398   125.6 1390.74
   157.4 1379.77     274  1384.1   356.7 1380.14   366.3 1381.53   386.2  1377.7
   451.2  1376.7   498.4  1378.4  519.591372.051   533.9 1368.97   604.5 1369.02
  619.341373.115   630.8 1374.72   689.5 1374.54   719.6 1385.55   732.1 1386.95
   806.7 1384.38   832.3 1386.14   848.4 1383.97     924 1384.05   935.7 1386.29
   977.3 1399.82  1001.4 1413.01  1017.5 1419.01    1050 1426.38  1065.6 1432.15
#Mann= 6 ,-1 , 0
       0      .1       0  217.11     .06       0  322.18    .025       0
  519.59    .045       0  619.34    .025       0  638.12      .1       0
Bank Sta=519.59,619.34
XS Rating Curve= 0 ,0
Exp/Cntr=0.3,0.1

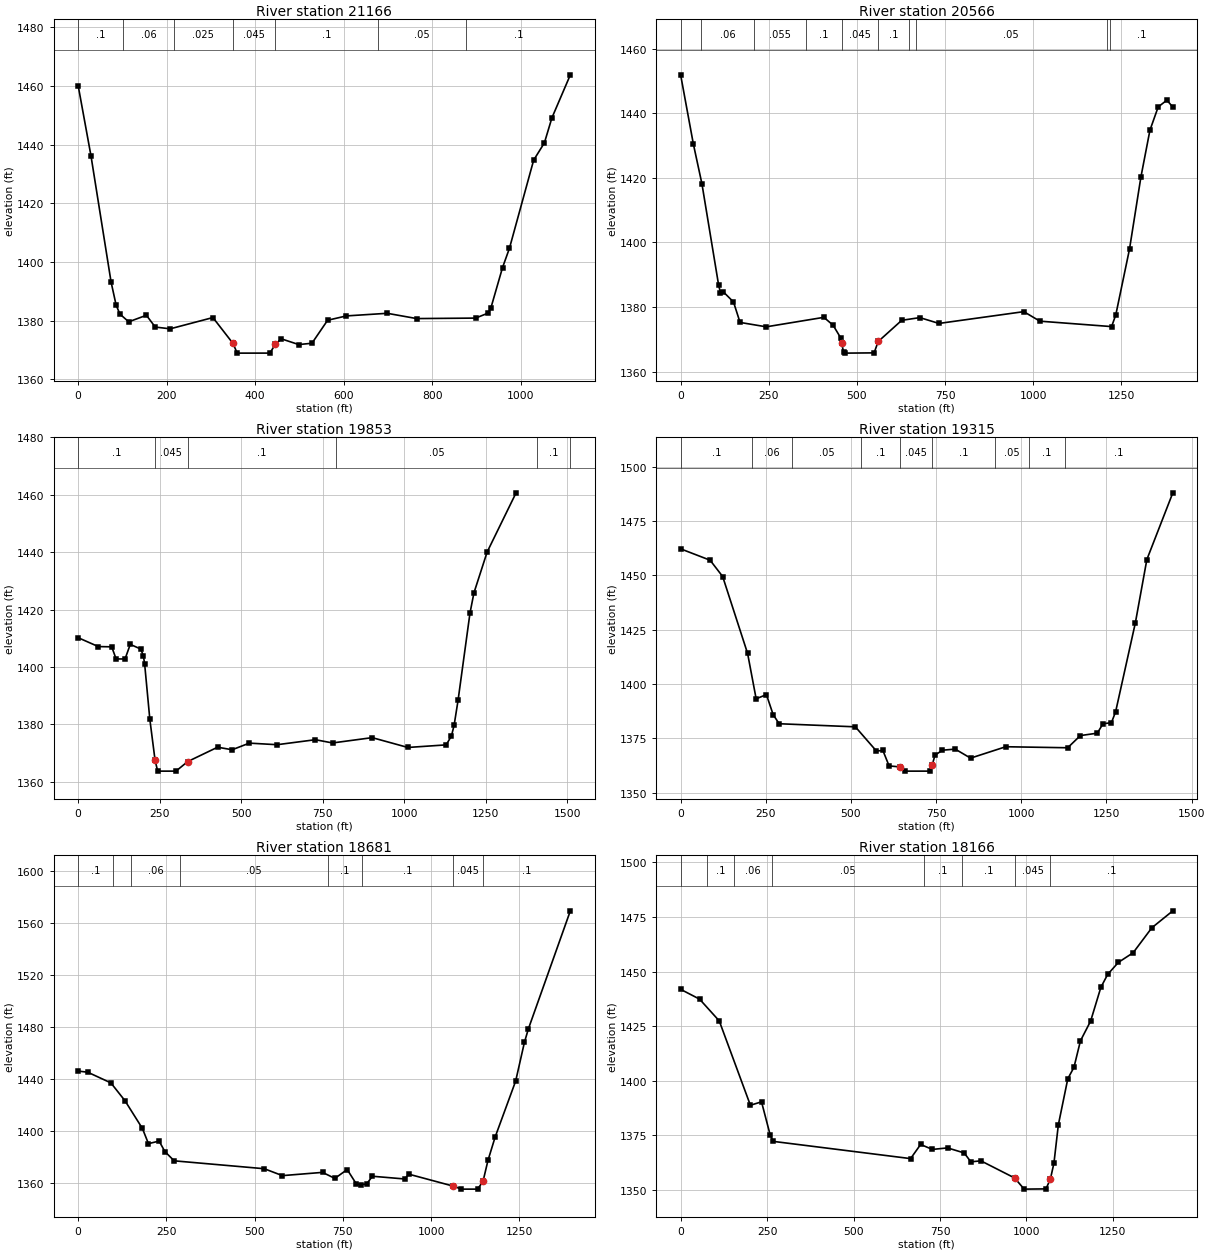
Type RM Length L Ch R = 1 ,21166   ,613,600,594
XS GIS Cut Line= 3
2445387.04723352694183.7113724652445709.40255994 693931.16955471
2446238.06291994693468.278092042
#Sta/Elev= 30
       0 1460.18    28.9 1436.29    74.4  1393.2    85.8 1385.31    94.4 1382.25
   114.3 1379.62   154.2 1381.85   174.2 1377.83     208 1377.23   304.5 1381.07
  349.861372.254   359.4 1368.94   433.3 1368.95  445.431371.917   459.1 1373.81
   498.5 1371.86   528.3 1372.31   563.7 1380.15   606.2 1381.63   698.4 1382.52
     765 1380.72   898.2 1380.89     926 1382.57   932.3 1384.16   958.9 1398.09
   974.6  1404.7  1029.3 1434.75  1053.6 1440.66  1070.5 1449.15  1112.2 1463.84
#Mann= 7 ,-1 , 0
       0      .1       0  102.05     .06       0  215.46    .025       0
  349.86    .045       0  445.43      .1       0  677.55     .05       0
  877.21      .1       0
Bank Sta=349.86,445.43
XS Rating Curve= 0 ,0
Exp/Cntr=0.3,0.1

Type RM Length L Ch R = 1 ,20566   ,741.6,713.6,678.4
XS GIS Cut Line= 3
2445853.88488251 694680.967923882446174.49874261694302.091056958
2446729.14100602693594.264716715
#Sta/Elev= 30
       0 1451.94    36.1 1430.51    60.4 1418.18   107.5 1386.96   112.8 1384.44
   121.3 1384.68   149.9 1381.57   168.5 1375.23   242.8 1373.87   406.2 1376.81
   432.4 1374.36   453.4 1370.53  456.621368.869   461.9 1366.04   465.7 1365.72
   548.6  1365.8  560.271369.326     627 1375.89   678.3 1376.72   732.4 1374.92
     973 1378.57  1018.7 1375.62    1222 1373.94  1233.9 1377.57  1272.8 1397.96
  1305.1 1420.27  1330.7 1434.77  1354.1 1441.99  1378.7 1444.09  1395.6 1441.95
#Mann= 10 ,-1 , 0
       0      .1       0   58.18     .06       0  207.06    .055       0
  355.95      .1       0  456.62    .045       0  560.27      .1       0
  647.27    .025       0  667.17     .05       0  1207.8      .1       0
 1218.43      .1       0
Bank Sta=456.62,560.27
XS Rating Curve= 0 ,0
Exp/Cntr=0.3,0.1

Type RM Length L Ch R = 1 ,19853   ,550.1,537.7,521.1
XS GIS Cut Line= 4
2446733.78151417694938.8142064812446765.37616977694810.323097459
2446780.82922286694480.6126815382446919.86109704693611.230233967
#Sta/Elev= 30
       0 1410.21    61.7 1407.12   102.9 1407.03   116.4 1402.81   143.8  1402.8
   159.8 1407.88   191.8 1406.27   199.8 1403.98   203.8 1401.16   219.8 1381.79
   235.9 1367.49   243.9 1363.75   299.9 1363.75   335.8 1367.07   427.6 1372.08
   472.2 1371.19   524.9  1373.5     610 1372.95   727.4 1374.69   780.1 1373.56
   901.6 1375.41    1011 1371.99  1128.5 1372.89  1144.7 1376.02  1152.8 1379.71
  1164.9 1388.38  1201.4 1418.72  1213.5 1425.77    1254 1440.02  1342.8 1460.65
#Mann= 6 ,-1 , 0
       0      .1       0   235.9    .045       0   335.8      .1       0
  792.17     .05       0 1406.72      .1       0 1509.23      .1       0
Bank Sta=235.9,335.8
XS Rating Curve= 0 ,0
Exp/Cntr=0.3,0.1

Type RM Length L Ch R = 1 ,19315   ,607.7,633.5,648.4
XS GIS Cut Line= 4
2447190.94191968695105.3499491212447345.65486485 694771.00120838
 2447192.2801716694160.8219825482447306.90002111693728.594500542
#Sta/Elev= 30
       0 1462.21    86.5 1456.98   123.4 1449.48   196.6 1414.07   221.7  1393.2
   251.8 1395.16   271.6 1385.93   289.2 1381.74   512.9 1380.32   574.7 1369.19
   593.7 1369.44   611.9 1362.34  643.171361.892   657.2 1359.94   731.5 1359.94
  738.741362.944   746.6 1367.27   768.6 1369.57     806 1370.07   851.1 1365.92
   954.3 1371.16  1136.1 1370.69  1173.4  1376.3    1223  1377.4  1239.9 1381.77
  1264.4 1382.19  1276.8 1387.25  1334.8 1428.21  1368.5 1457.28  1444.7 1487.98
#Mann= 9 ,-1 , 0
       0      .1       0  210.27     .06       0  327.46     .05       0
   530.1      .1       0  643.17    .045       0  738.74      .1       0
  921.92     .05       0 1021.83      .1       0 1128.34      .1       0
Bank Sta=643.17,738.74
XS Rating Curve= 0 ,0
Exp/Cntr=0.3,0.1

Type RM Length L Ch R = 1 ,18681   ,480.6,515.2,540.1
XS GIS Cut Line= 3
2447267.09563878695120.4680291272447728.43690768694506.309480548
2447890.98710752 693901.22374846
#Sta/Elev= 30
       0  1446.2      27 1445.35    92.7 1437.12   132.6 1423.41   182.1    1402
   199.2  1390.3   229.4 1392.29   245.8 1384.21   272.1 1377.08   527.3    1371
   578.8 1365.68   692.4 1368.18   727.4 1363.56   762.4 1370.36   788.2  1359.3
   800.7 1358.81   817.2 1359.15   833.8  1365.2   924.9 1363.11   937.3 1366.77
 1063.441357.554  1086.2 1355.28  1131.9 1355.28 1147.251361.272  1161.3 1377.42
  1181.7 1395.49  1239.7 1438.49  1264.5 1468.25  1275.6 1478.55  1394.7 1569.64
#Mann= 8 ,-1 , 0
       0      .1       0   99.63      .1       0  149.17     .06       0
  288.94     .05       0  708.25      .1       0  803.96      .1       0
 1063.44    .045       0 1147.25      .1       0
Bank Sta=1063.44,1147.25
XS Rating Curve= 0 ,0
Exp/Cntr=0.3,0.1

Type RM Length L Ch R = 1 ,18166   ,294.2,299.1,305.8
XS GIS Cut Line= 3
2447301.47647554695141.8580782122448138.83142811 694570.69616279
2448472.08273011694332.717636123
#Sta/Elev= 30
       0  1441.9    54.8 1437.41   111.7 1427.43   201.7  1388.8   233.9 1390.37
   259.2 1375.02   267.8 1372.25   664.9 1364.36   693.9 1370.84   727.8 1368.57
   771.9 1369.26   819.8 1366.96   839.2 1362.88   868.2 1363.34  965.711355.488
   993.3 1350.38  1056.4 1350.49 1069.261355.099  1079.4 1362.31  1092.1 1379.82
  1119.5 1400.96  1137.2 1406.15    1156 1418.31  1185.5 1427.37    1215 1442.78
  1234.7 1448.73  1265.7 1454.25  1308.4 1458.66  1362.5  1470.1  1423.1 1477.86
#Mann= 8 ,-1 , 0
       0      .1       0   76.69      .1       0  155.27     .06       0
  264.93     .05       0  703.58      .1       0  813.24      .1       0
  965.71    .045       0 1069.26      .1       0
Bank Sta=965.71,1069.26
XS Rating Curve= 0 ,0
Exp/Cntr=0.3,0.1

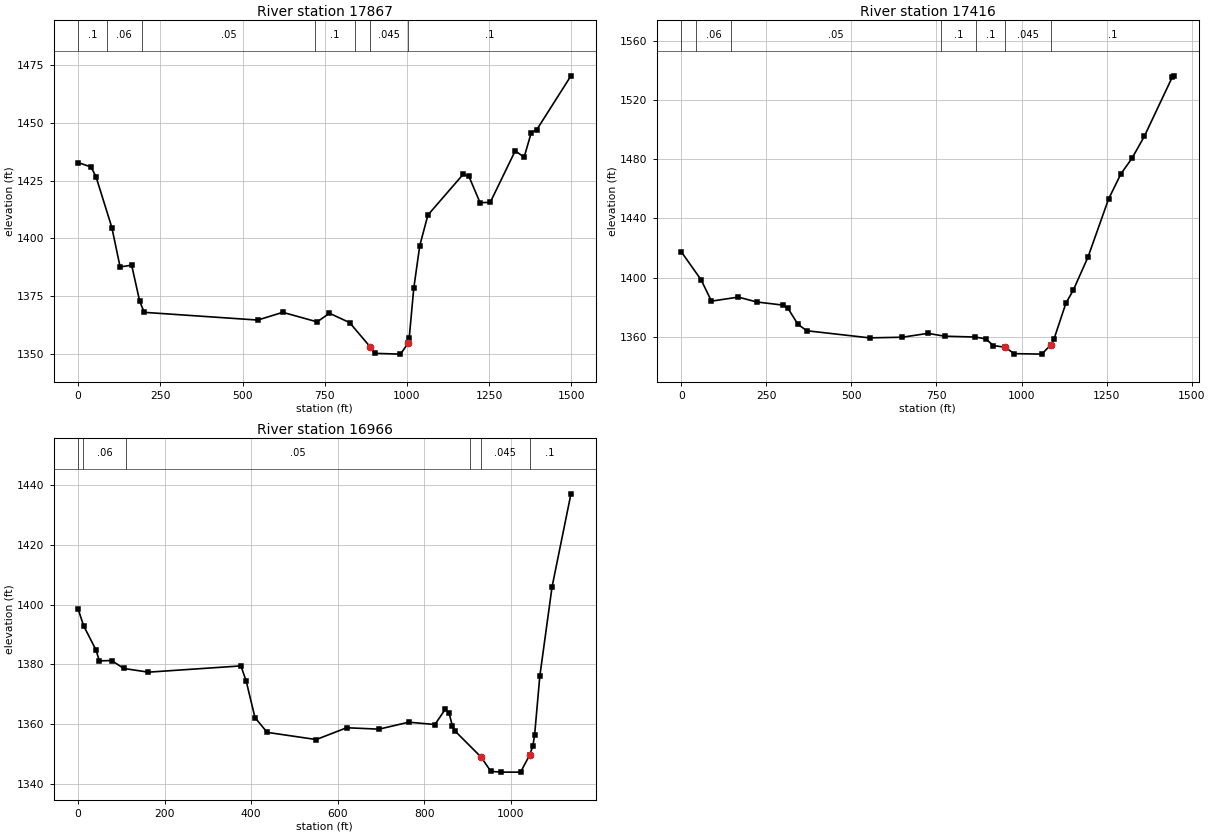
Type RM Length L Ch R = 1 ,17867   ,446.1,450.9,450.7
XS GIS Cut Line= 3
2447483.35012752695276.7498687952448439.96993345694743.500607207
2448712.16066203694445.771871954
#Sta/Elev= 30
       0 1432.84    39.1 1430.95    54.3 1426.69   102.4 1404.68   127.5 1387.55
   162.6 1388.35   187.1 1372.66   200.9 1367.87     546 1364.52   622.1 1367.88
   726.8 1363.73   764.1 1367.48   825.4 1363.42  887.361353.007   901.5 1350.08
   980.1 1349.74 1003.271354.463  1006.8 1356.89  1020.5 1378.22  1038.8 1396.81
  1063.6  1410.1  1170.5 1427.71  1188.2 1426.88  1222.2 1415.44  1253.2  1415.6
  1329.1 1437.94  1356.2 1435.19  1377.9 1445.85  1394.9 1447.17  1498.6 1470.49
#Mann= 7 ,-1 , 0
       0      .1       0   87.21     .06       0  192.85     .05       0
  721.06      .1       0  840.63      .1       0  887.36    .045       0
 1003.27      .1       0
Bank Sta=887.36,1003.27
XS Rating Curve= 0 ,0
Exp/Cntr=0.3,0.1

Type RM Length L Ch R = 1 ,17416   ,432.6,450,474.8
XS GIS Cut Line= 3
2447581.73608559  695636.01489832448505.18797886695222.825107872
 2448887.0940392695011.154599458
#Sta/Elev= 30
       0 1417.41    58.1  1398.5    88.7 1384.07   167.6 1386.79   221.8 1383.49
   298.3 1381.41   313.4 1379.25   342.9 1368.37   369.2 1364.05   553.3 1359.26
   649.7 1359.69   725.2 1362.31   773.6 1360.39   864.5 1359.81   895.1 1358.53
     917 1354.06  951.691352.942   978.3 1348.59  1059.2 1348.27  1087.11354.709
  1095.8 1358.74  1130.5 1382.73  1151.8 1391.34  1195.2 1413.75  1255.8 1453.05
  1292.4  1470.2  1324.7 1480.58    1361 1495.46  1443.3 1535.53  1448.3 1536.28
#Mann= 7 ,-1 , 0
       0      .1       0   43.84     .06       0  146.61     .05       0
  763.22      .1       0  865.99      .1       0  951.69    .045       0
  1087.1      .1       0
Bank Sta=951.69,1087.1
XS Rating Curve= 0 ,0
Exp/Cntr=0.3,0.1

Type RM Length L Ch R = 1 ,16966   ,443.6,448.5,453.8
XS GIS Cut Line= 3
2447638.23630068695793.1937177932448615.84786251695652.691702217
2448765.98109245695630.799685627
#Sta/Elev= 30
       0 1398.46    12.6 1392.93    40.9 1384.93      49 1381.22    77.3 1381.32
   105.6 1378.67   162.2 1377.44   376.3 1379.53   388.5 1374.45   408.8 1362.26
     437 1357.34   550.4 1354.94   620.8 1358.88   695.6 1358.41   764.3 1360.73
   824.9 1359.96   849.1 1365.12   857.2 1363.92   865.3 1359.49   871.7 1357.74
  931.67 1349.07   954.2 1344.31   978.5 1344.06  1022.9 1344.06 1043.551349.669
  1051.2 1352.75  1055.3 1356.36  1067.4 1376.11  1095.7 1405.92  1139.4 1436.99
#Mann= 6 ,-1 , 0
       0     .05       0   11.75     .06       0  111.08     .05       0
  905.73      .1       0  931.67    .045       0 1043.55      .1       0
Bank Sta=931.67,1043.55
XS Rating Curve= 0 ,0
Exp/Cntr=0.3,0.1