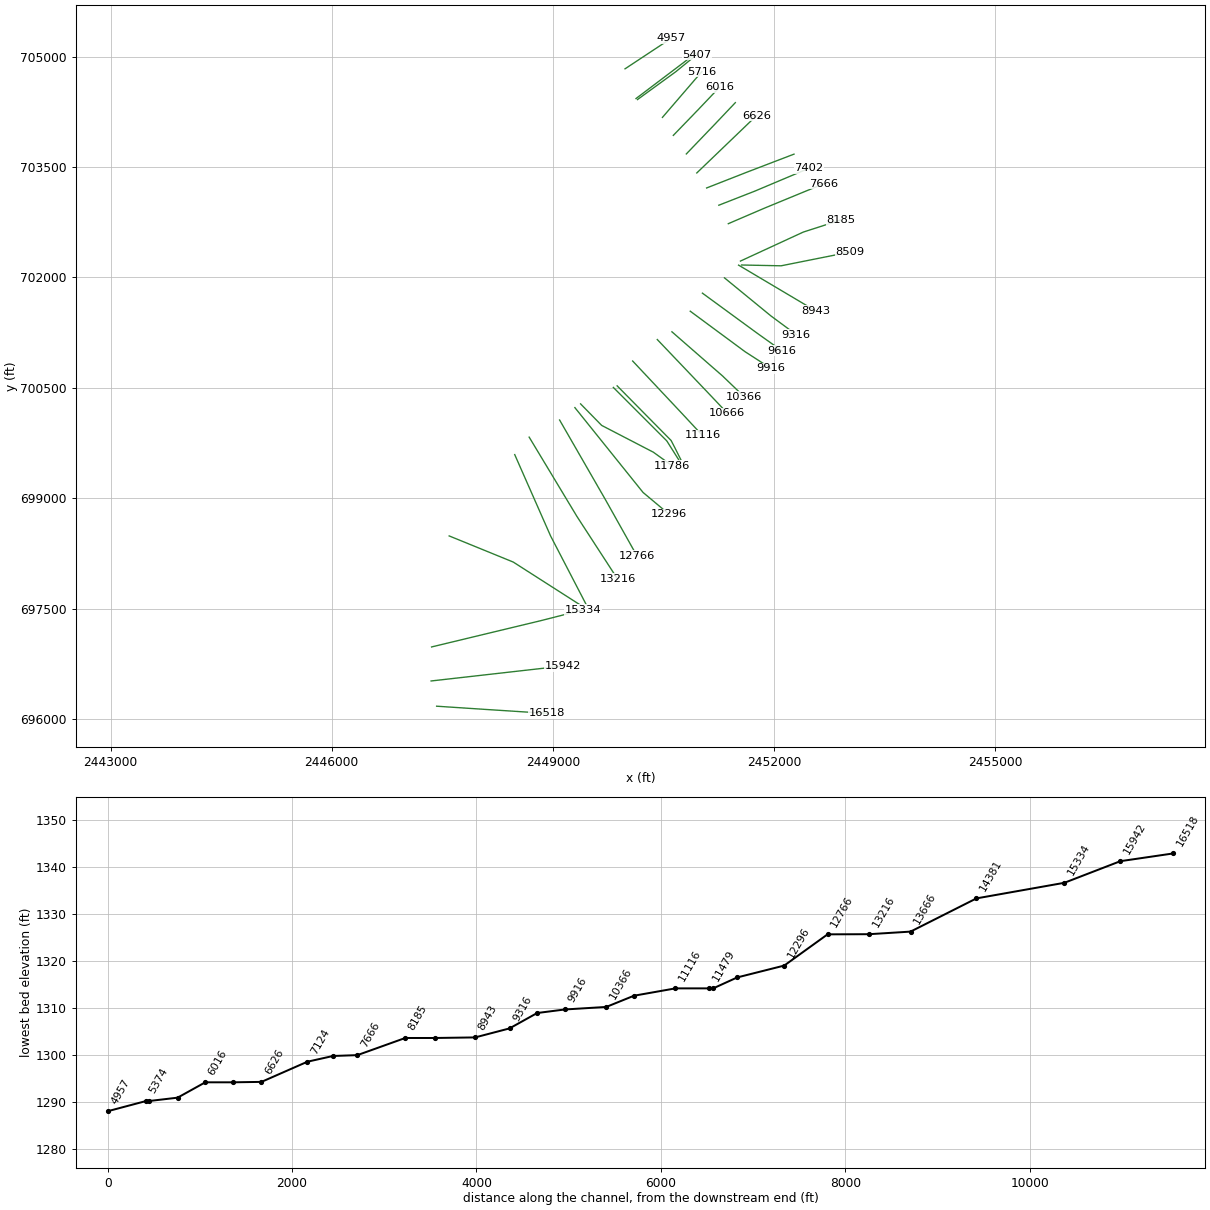
HEC-RAS study NFSBPOTOMC.prj: NFSBPOTOMC

--- NFSBPOTOMC.g01 (geometry) --- (continued)

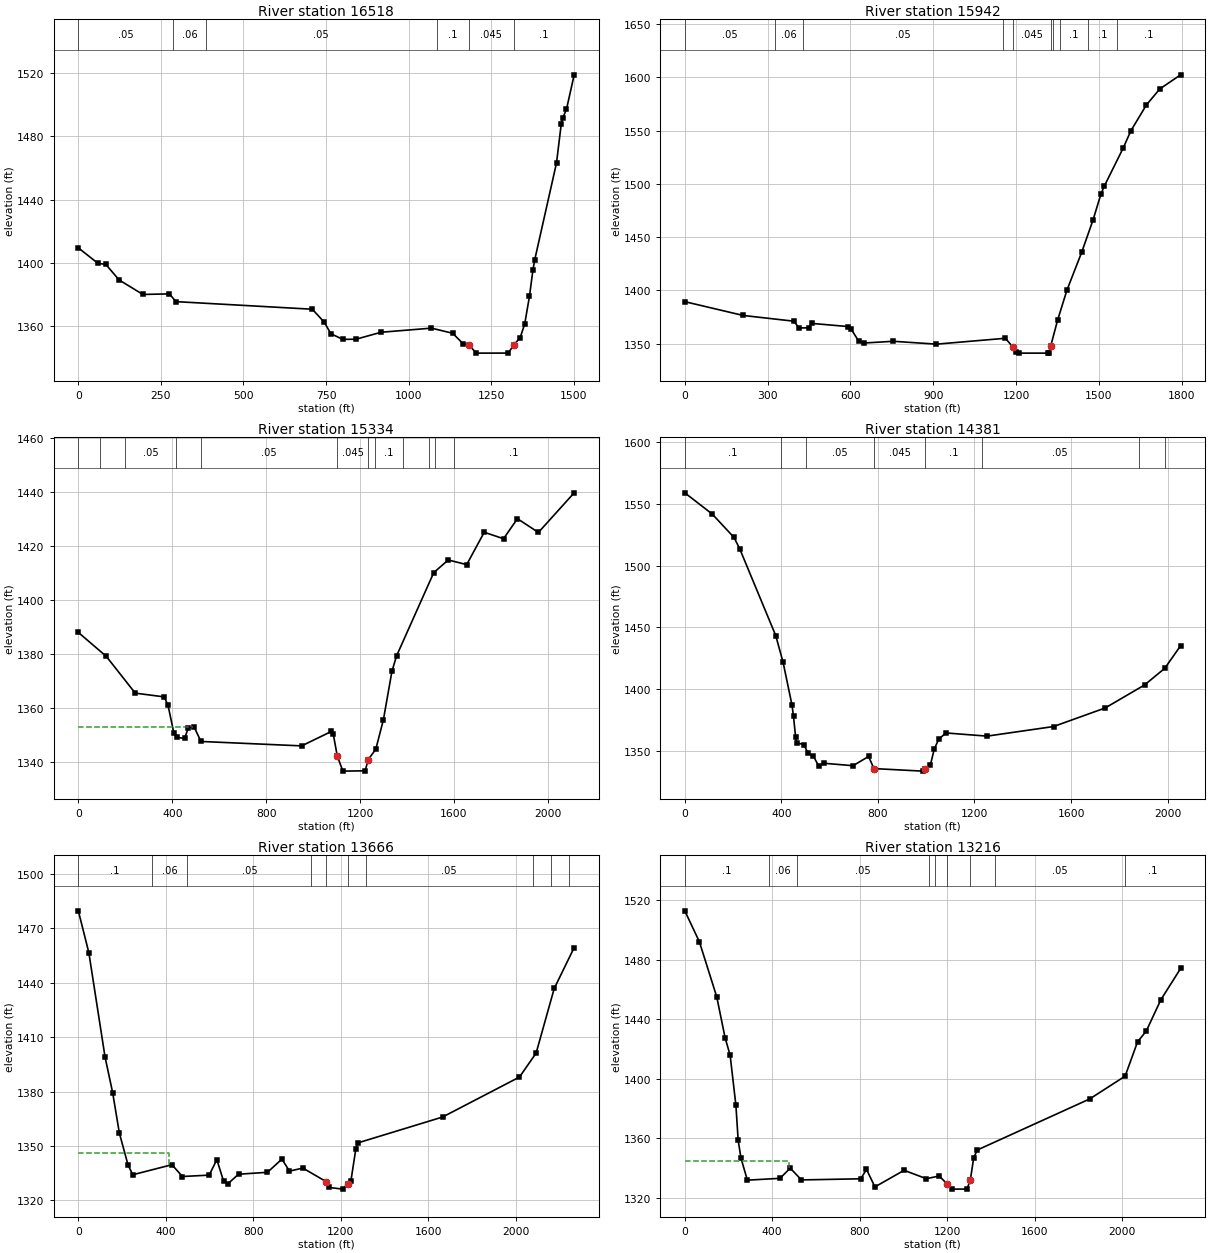
Type RM Length L Ch R = 1 ,16518   ,563.3,575.8,587.4
XS GIS Cut Line= 3
2447423.66422328696178.6670282192448101.54410112696134.034243464
2448921.93123984696081.280740038
#Sta/Elev= 30
       0 1409.47    59.2  1399.7    83.3    1399   123.3 1389.17   195.5 1379.98
   275.7 1380.33   295.7 1375.43   708.6 1370.62   744.7 1362.41   764.7 1355.12
   800.8 1351.55   840.9 1351.65   916.9 1356.06  1069.4 1358.65  1133.5 1355.41
  1165.6 1348.68 1182.181347.979  1205.6 1342.84  1301.8 1342.86 1317.861347.819
  1337.9 1352.65  1351.7 1361.31    1366 1378.73  1376.4 1395.16    1382 1401.92
    1448 1463.26  1462.2  1487.7  1466.2 1491.37  1478.2 1497.19  1501.4 1518.97
#Mann= 6 ,-1 , 0
       0     .05       0  286.53     .06       0   386.3     .05       0
 1084.71      .1       0 1182.18    .045       0 1317.86      .1       0
Bank Sta=1182.18,1317.86
XS Rating Curve= 0 ,0
Exp/Cntr=0.3,0.1

Type RM Length L Ch R = 1 ,15942   ,597,607.7,613.7
XS GIS Cut Line= 2
2447348.68832335696521.2470517162449133.82287645696723.658392295
#Sta/Elev= 30
       0 1389.51   211.4 1376.56   396.6 1371.13   412.7 1364.81   448.9 1364.94
     461 1369.09   592.7 1366.11   601.9 1364.05   630.1 1352.45   650.2  1350.7
   755.4 1352.31   911.9 1349.62  1161.5 1355.13 1189.731346.697  1200.1 1342.07
    1211 1341.19  1314.4 1341.19  1318.5 1341.66 1325.471347.482  1350.7 1372.06
  1384.5 1400.21  1438.8 1436.35  1479.5 1466.42  1507.9 1490.61  1519.7 1497.83
  1588.2  1533.6  1616.3 1549.93  1672.7 1574.26  1721.3 1589.29  1796.6  1602.5
#Mann= 10 ,-1 , 0
       0     .05       0  326.92     .06       0  430.07     .05       0
 1152.14    .025       0 1189.73    .045       0 1325.47    .025       0
 1335.86      .1       0 1358.44      .1       0  1461.6      .1       0
 1564.75      .1       0
Bank Sta=1189.73,1325.47
XS Rating Curve= 0 ,0
Exp/Cntr=0.3,0.1

Type RM Length L Ch R = 1 ,15334   ,973.3,953.5,843.5
XS GIS Cut Line= 3
 2447355.1305677696983.2087262122448839.12366268697340.505911872
2449406.30264643697485.081738204
#Sta/Elev= 30
       0 1387.97   118.9 1379.12   242.3 1365.49   365.8 1364.09   382.2 1360.91
   406.9 1350.69   419.3  1349.1   452.2 1348.73   468.6 1352.56     493 1352.98
   522.1 1347.59   951.1 1345.95  1077.6 1351.29  1085.8 1350.33 1102.841342.154
  1126.8  1336.6  1221.6 1336.72  1234.71340.897  1266.8 1344.69  1299.3 1355.65
  1335.7 1373.62  1355.6 1379.33  1513.7 1410.12  1575.5 1414.81    1654 1413.08
  1728.7 1425.07  1810.9 1422.67  1870.1 1430.09  1959.4    1425  2111.7 1439.67
#Mann= 12 ,-1 , 0
       0     .12       0    91.5      .1       0  199.19     .05       0
  414.57     .06       0  522.26     .05       0 1102.84    .045       0
  1234.7    .025       0 1262.01      .1       0 1383.78      .1       0
 1491.47      .1       0 1518.33      .1       0 1599.57      .1       0
#XS Ineff= 2 , 0
          490.39 1353.02
Permanent Ineff=
       F       F
Bank Sta=1102.84,1234.7
XS Rating Curve= 0 ,0
Exp/Cntr=0.3,0.1

Type RM Length L Ch R = 1 ,14381   ,732.7,714.5,595.5
XS GIS Cut Line= 3
 2447593.8761532 698490.703086542448463.41378418698135.755961791
2449402.03329802697534.497649878
#Sta/Elev= 30
       0 1559.06   113.3  1541.9     204 1522.84   227.6 1513.59   376.8 1443.22
   407.1 1421.57     444 1386.92   450.3 1377.78   458.9 1361.11   463.2 1356.22
   493.5 1354.83   510.7 1347.67   532.4  1345.5     554 1337.68   575.6 1339.69
     697 1337.69   761.3 1345.19  783.331335.357   985.7 1333.29  995.131334.698
  1017.5 1338.39  1033.4 1351.25    1052 1359.21  1081.7 1364.26  1251.9 1361.68
  1527.4 1369.46  1741.4 1384.53  1904.8 1403.23  1988.2  1416.7  2053.9 1435.02
#Mann= 8 ,-1 , 0
       0      .1       0   398.1     .06       0  500.02     .05       0
  783.33    .045       0  995.13      .1       0  1230.5     .05       0
 1879.96      .1       0  1988.2      .1       0
Bank Sta=783.33,995.13
XS Rating Curve= 0 ,0
Exp/Cntr=0.3,0.1

Type RM Length L Ch R = 1 ,13666   ,438.4,450,450.5
XS GIS Cut Line= 3
2448483.30252394699594.5794877112448969.65030453 698490.83858496
2449458.23889428697548.426099718
#Sta/Elev= 30
       0 1479.51    48.2 1456.38   122.1 1399.05     157 1379.35   187.6 1357.14
   226.9 1339.73   248.8 1334.15     428 1339.69   476.1 1333.19   598.5 1333.95
   633.5  1342.5   664.1  1330.7   685.1 1329.32   732.7 1334.45   865.1 1335.51
   931.1 1342.78   965.7 1336.16  1026.9 1337.83 1134.251330.318  1144.9 1327.18
  1209.9 1326.24 1231.221329.213  1246.6 1330.68  1269.2 1348.43  1278.1 1351.69
  1665.7 1365.94  2017.5 1387.96  2093.7 1401.15  2176.5 1436.74  2267.7 1459.26
#Mann= 10 ,-1 , 0
       0      .1       0   336.4     .06       0  498.67     .05       0
 1066.03      .1       0 1134.25    .045       0 1231.22      .1       0
 1313.81     .05       0 2077.37      .1       0 2160.32      .1       0
 2243.89      .1       0
#XS Ineff= 2 , 0
          415.93 1346.33
Permanent Ineff=
       F       F
Bank Sta=1134.25,1231.22
XS Rating Curve= 0 ,0
Exp/Cntr=0.3,0.1

Type RM Length L Ch R = 1 ,13216   ,450.1,450,445.4
XS GIS Cut Line= 3
2448679.14891702699832.1393800382449325.73784694698757.787198052
 2449877.8578057697906.793493211
#Sta/Elev= 30
       0 1512.77    66.8 1491.94   146.2 1454.92   184.2 1427.54   207.5 1415.61
   233.8 1381.94   244.2 1358.45   257.1 1346.49   286.2 1331.72   435.6 1332.95
   482.3  1339.8   533.7 1331.88     805 1332.64   831.2 1338.98   869.8 1327.18
  1003.2 1338.35  1105.2 1332.69  1163.9 1334.53 1198.011329.423  1224.3 1325.69
  1290.7 1325.73 1305.841331.512  1321.9 1346.94  1338.4    1352  1852.5 1386.32
  2014.4 1401.64  2071.5 1424.81  2110.9 1431.87  2177.6 1452.93  2268.3 1474.04
#Mann= 9 ,-1 , 0
       0      .1       0  383.97     .06       0  511.07     .05       0
 1119.08      .1       0 1146.54    .025       0 1198.01    .045       0
 1305.84      .1       0 1419.98     .05       0 2011.57      .1       0
#XS Ineff= 2 , 0
          477.88 1344.76
Permanent Ineff=
       F       F
Bank Sta=1198.01,1305.84
XS Rating Curve= 0 ,0
Exp/Cntr=0.3,0.1

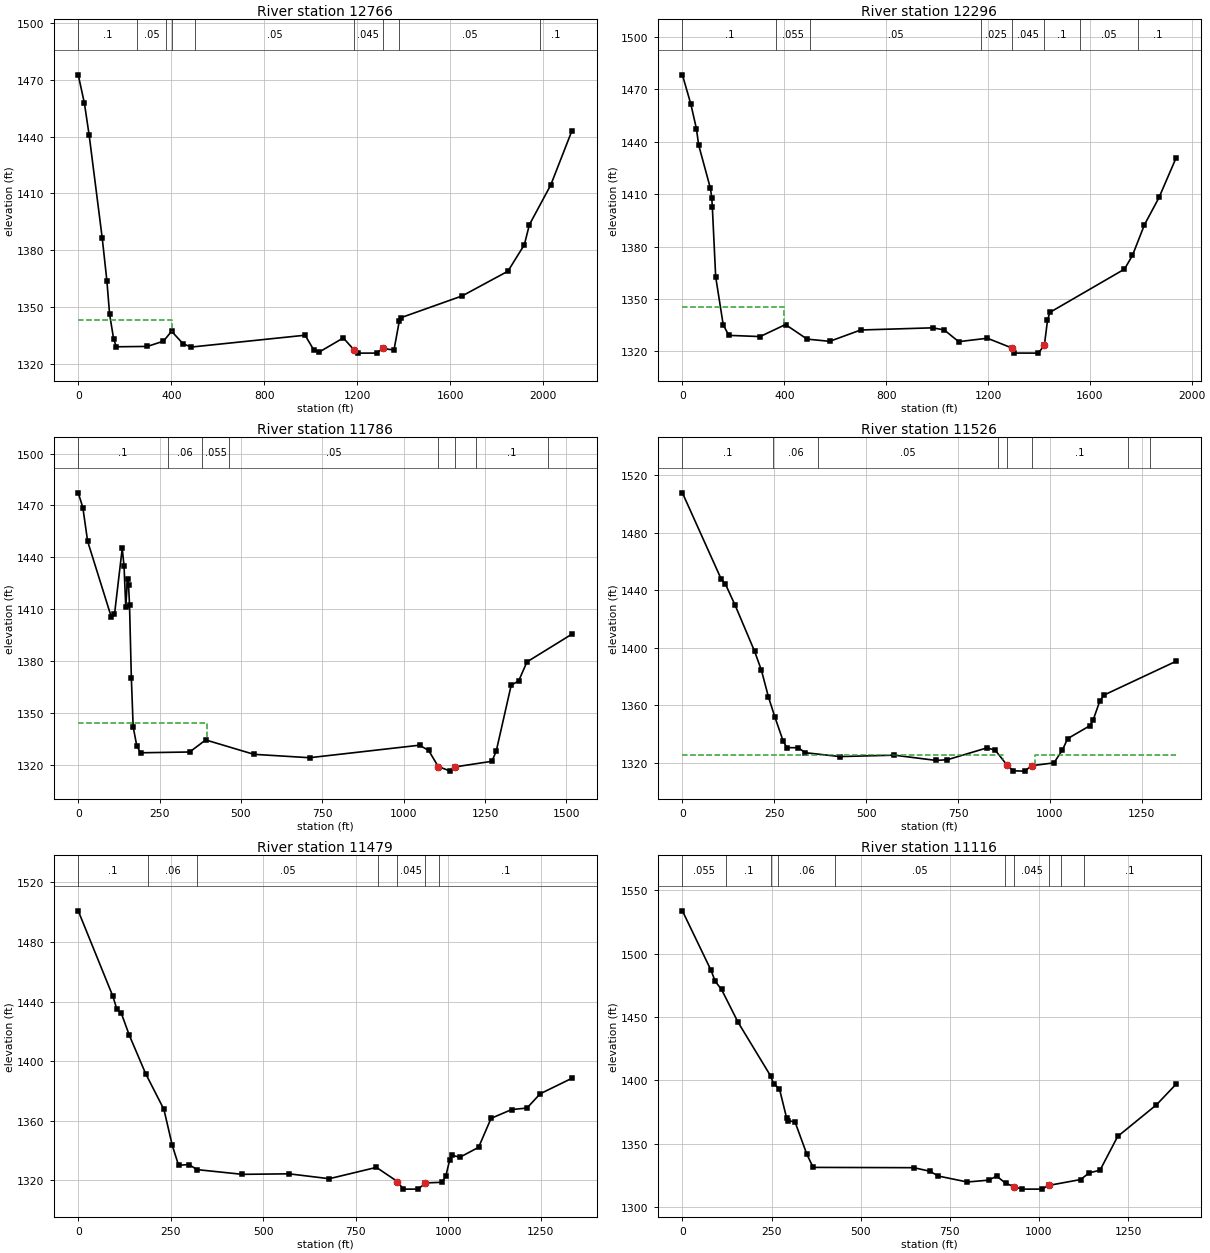
Type RM Length L Ch R = 1 ,12766   ,466.4,470.2,486.9
XS GIS Cut Line= 3
2449092.11856353700064.5178522912449712.70623311 698985.22473529
2450141.94946912698219.245952293
#Sta/Elev= 30
       0 1472.64    26.6 1457.61    47.1 1440.63   103.4 1386.22   123.2 1363.86
   134.9 1346.23   152.5 1332.95   164.2 1329.01   297.2  1329.2   366.4 1331.97
   401.5 1337.21   451.3 1330.53   486.5 1328.87   975.5 1335.12  1012.4 1327.41
  1034.3  1326.1  1139.8 1333.68 1185.141327.479  1204.2 1325.66  1283.5 1325.68
 1308.851328.106  1357.7 1327.32  1380.4 1342.46  1389.3 1344.45  1651.2 1355.89
  1847.7 1368.93  1918.2  1382.9    1940  1393.5  2031.7 1414.42    2123 1443.15
#Mann= 9 ,-1 , 0
       0      .1       0  253.23     .05       0  378.26    .035       0
  401.55    .055       0   503.3     .05       0 1185.14    .045       0
 1308.85      .1       0 1377.38     .05       0 1986.16      .1       0
#XS Ineff= 2 , 0
          402.65 1343.15
Permanent Ineff=
       F       F
Bank Sta=1185.14,1308.85
XS Rating Curve= 0 ,0
Exp/Cntr=0.3,0.1

Type RM Length L Ch R = 1 ,12296   ,488.7,510.6,556.2
XS GIS Cut Line= 3
2449299.49971044700232.8114789582450224.42469785699080.918113455
2450578.20154935698784.502367705
#Sta/Elev= 30
       0  1478.2    33.2 1461.41    54.9 1447.49      64 1437.97   110.2 1413.19
   115.3 1407.91   117.5 1402.79   130.7  1362.7   160.2 1335.33     182 1329.19
   305.1  1328.5   404.9 1335.38   489.8 1327.04   578.4 1325.78   700.1 1332.26
   982.7  1333.5    1028  1332.3  1084.9 1325.59  1197.7 1327.55 1293.621321.991
    1304 1319.07  1397.3 1319.03 1421.381323.471  1433.7 1337.77  1442.6  1342.3
  1735.9 1367.06  1767.3 1374.88  1814.3 1392.41  1871.7 1408.05  1938.8 1430.74
#Mann= 8 ,-1 , 0
       0      .1       0  369.05    .055       0  502.75     .05       0
 1171.26    .025       0 1293.62    .045       0 1421.38      .1       0
 1559.46     .05       0 1790.59      .1       0
#XS Ineff= 2 , 0
             400 1345.24
Permanent Ineff=
       F       F
Bank Sta=1293.62,1421.38
XS Rating Curve= 0 ,0
Exp/Cntr=0.3,0.1

Type RM Length L Ch R = 1 ,11786   ,268.8,260,251.7
XS GIS Cut Line= 4
2449376.81582877700283.543004796 2449662.8109917699991.243392542
2450364.06877553699627.5033063742450622.30447951699441.539767548
#Sta/Elev= 30
       0 1477.29    14.2 1468.75    28.9 1449.31   101.6 1405.56   111.4 1407.03
   135.2 1445.16   140.8 1434.86   146.1 1411.25   151.5 1427.72   154.6  1423.9
   157.6 1412.67   163.2 1370.57   168.8  1342.1     180 1331.08   191.5 1327.11
   342.3 1327.56   391.7 1334.53   539.7 1326.22   710.8 1324.26  1048.7 1331.49
  1076.7 1328.45 1106.251319.143  1143.4 1316.51  1156.71318.921  1271.2 1322.19
  1284.4 1328.06  1330.4  1366.2  1353.2 1368.58  1378.9 1379.62  1517.1 1395.66
#Mann= 8 ,-1 , 0
       0      .1       0  275.57     .06       0  379.32    .055       0
  464.35     .05       0 1106.25    .045       0  1156.7     .05       0
 1221.56      .1       0 1443.61     .05       0
#XS Ineff= 2 , 0
          396.46 1344.59
Permanent Ineff=
       F       F
Bank Sta=1106.25,1156.7
XS Rating Curve= 0 ,0
Exp/Cntr=0.5,0.3

Type RM Length L Ch R = 1 ,11526   ,46.3,46.1,46.8
XS GIS Cut Line= 3
2449821.18534687700506.8775318712450546.27247936699781.312053874
2450715.55134028  699512.7413968
#Sta/Elev= 30
       0 1507.59   105.7 1447.56   117.1 1444.15   143.7 1429.33   196.3 1397.53
   214.9 1384.35   234.2 1365.68   251.2 1352.08   273.8 1335.36   283.9 1330.51
     315 1330.45   334.8 1326.98   428.2 1324.31   576.8 1325.28   689.9 1321.64
   720.9 1322.12   828.4 1330.33     851  1328.8  882.081318.734   900.5 1314.39
   931.6 1314.19  949.931317.958  1010.8 1319.93  1033.7 1328.81  1048.2 1336.79
  1109.2 1345.85  1117.8 1349.97  1135.2  1362.6  1146.8 1367.03  1343.2 1390.55
#Mann= 8 ,-1 , 0
       0      .1       0  246.98     .06       0  369.45     .05       0
  859.32    .025       0  882.08    .045       0  949.93      .1       0
 1212.64     .05       0 1272.03      .1       0
#XS Ineff= 2 , 0
             872  1325.6     959          1325.6
Permanent Ineff=
       F       F
Bank Sta=882.08,949.93
XS Rating Curve= 0 ,0
Exp/Cntr=0.5,0.3

Type RM Length L Ch R = 1 ,11479   ,364.7,363.2,361.2
XS GIS Cut Line= 4
2449872.92540085700528.5474360442450604.78778228699786.596164048
2450651.82312128699696.1977227932450737.03981435699526.110464543
#Sta/Elev= 30
       0  1500.9    93.7 1443.52   104.3 1434.96   116.5 1432.11   138.2 1417.33
   182.1 1391.72   231.6 1367.65   254.2 1343.48   271.2 1330.19   298.8 1330.68
   321.6 1327.26   443.7 1324.11   569.8 1324.45   678.5 1321.18   805.8 1328.78
  862.481319.303   878.8 1314.19   918.9  1314.2  938.351318.329   983.9  1318.8
   993.7 1323.28  1003.7 1333.62  1010.8 1336.78    1032 1335.66    1082 1342.25
  1115.7 1361.68  1171.1 1367.55  1212.8  1368.6  1248.4 1378.16  1334.3 1388.58
#Mann= 7 ,-1 , 0
       0      .1       0  189.17     .06       0   320.1     .05       0
  811.34    .025       0  862.48    .045       0  938.35    .055       0
  975.08      .1       0
Bank Sta=862.48,938.35
XS Rating Curve= 0 ,0
Exp/Cntr=0.5,0.3

Type RM Length L Ch R = 1 ,11116   ,449.5,450,450.8
XS GIS Cut Line= 3
 2450083.6680896700865.3174317932450751.37705603700154.508157879
 2451030.3354876699854.525818214
#Sta/Elev= 30
       0 1533.67    80.2 1486.83    92.1 1478.03   109.7  1471.7   156.4 1445.65
   247.3 1403.53   255.7 1397.32   272.2 1393.32   292.5 1370.09   296.6 1368.29
   316.1 1367.04   349.1 1341.69   366.7 1331.33   649.1  1331.1   694.8 1328.26
     717 1324.56     799 1319.81   859.5 1321.27   881.4 1324.47   906.6 1318.85
  931.271316.023   952.8 1314.19  1008.5  1314.2 1026.941317.089  1116.7 1321.73
  1141.5 1327.07  1171.4 1329.08    1221 1355.76  1329.8  1380.7  1384.9 1397.01
#Mann= 10 ,-1 , 0
       0    .055       0   123.5      .1       0  248.82     .05       0
  269.29     .06       0  427.86     .05       0  903.58      .1       0
  931.27    .045       0 1026.94    .025       0  1061.6     .06       0
 1126.66      .1       0
Bank Sta=931.27,1026.94
XS Rating Curve= 0 ,0
Exp/Cntr=0.3,0.1

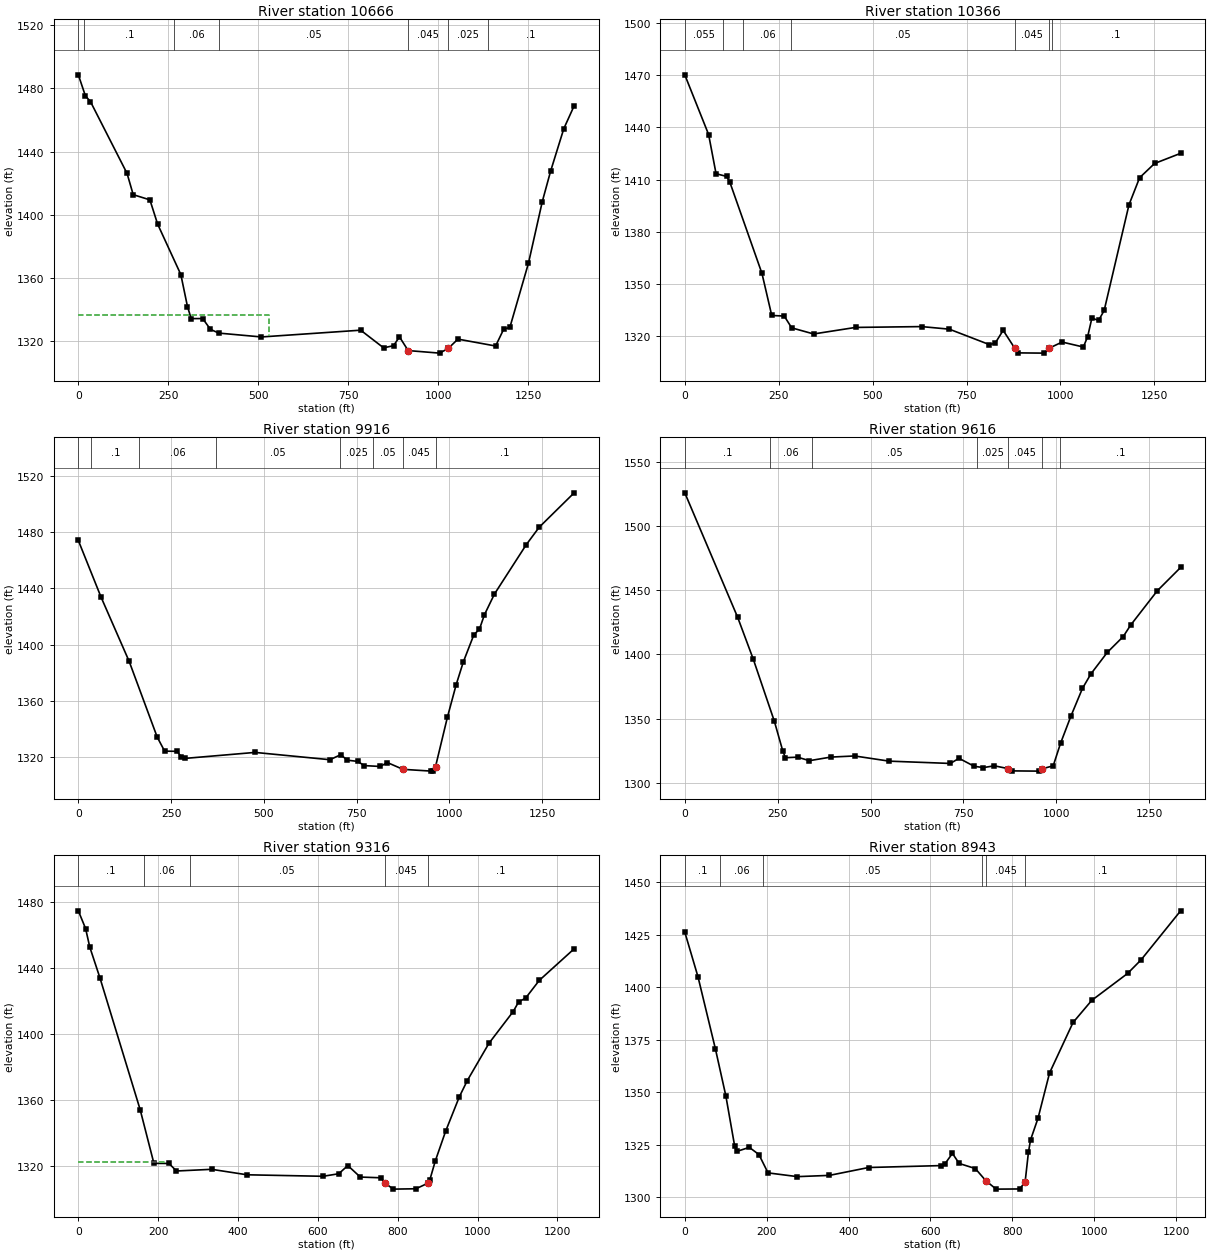
Type RM Length L Ch R = 1 ,10666   ,297.8,300,302.8
XS GIS Cut Line= 3
2450417.54504654701157.1915199612451085.47645345700455.894038051
2451367.19964328700158.703031376
#Sta/Elev= 30
       0 1488.49    19.7 1475.16    33.6 1471.61   135.5 1426.14   152.5 1412.76
   198.9 1409.48   220.3  1394.2   284.9 1362.26   303.3 1342.07   313.7 1334.44
   345.7 1334.47   367.1 1327.66   390.3 1325.29   508.9 1322.85   784.7 1327.13
   848.4 1315.97     876 1317.33   892.5  1322.9  916.671314.242    1004 1312.63
 1028.111315.608    1055 1321.48  1159.7 1317.13  1182.3 1327.83  1199.3 1328.87
    1251 1369.47  1289.5 1408.44  1312.4  1427.5  1349.2 1454.46    1378 1468.93
#Mann= 7 ,-1 , 0
       0    .055       0   17.11      .1       0  266.44     .06       0
   391.1     .05       0  916.67    .045       0 1028.11    .025       0
 1139.39      .1       0
#XS Ineff= 2 , 0
          530.27 1336.53
Permanent Ineff=
       F       F
Bank Sta=916.67,1028.11
XS Rating Curve= 0 ,0
Exp/Cntr=0.3,0.1

Type RM Length L Ch R = 1 ,10366   ,445.2,450,457.5
XS GIS Cut Line= 3
2450616.40061995701261.9714941232451302.16532451700663.324725538
2451597.50528502700379.661907047
#Sta/Elev= 30
       0 1470.29    63.4 1435.96    83.2 1413.42   111.6 1411.86   119.9 1408.55
   205.4 1356.08   231.4 1331.91   264.7 1331.56   284.5 1324.79   342.9 1321.27
   454.4 1325.03   630.4 1325.51   704.1 1324.03   810.2  1315.2     826 1315.91
   847.4 1323.35  878.361313.045   886.6 1310.39   957.1 1310.25  969.94 1313.11
  1004.4 1316.62  1060.9 1313.76  1072.3 1319.71  1083.6 1330.39  1101.5 1329.05
  1116.3 1334.81  1182.3 1395.53  1210.6 1411.12  1250.5 1419.31  1319.8 1425.15
#Mann= 7 ,-1 , 0
       0    .055       0  101.31      .1       0  155.56     .06       0
  283.91     .05       0  878.36    .045       0  969.94     .05       0
  976.58      .1       0
Bank Sta=878.36,969.94
XS Rating Curve= 0 ,0
Exp/Cntr=0.3,0.1

Type RM Length L Ch R = 1 ,9916    ,299.9,300,298.3
XS GIS Cut Line= 3
2450864.52053052701542.0457371322451609.91110012 700991.01665546
2451953.79623911700768.890131205
#Sta/Elev= 30
       0 1474.24      61 1433.97   137.1 1387.93   212.6 1333.96   232.6 1323.97
   266.4 1323.83   276.4 1320.14   287.9  1318.8   476.3 1323.06   678.2 1317.85
   707.4 1321.47   724.6 1317.52   753.2 1316.65   770.3 1313.65   813.6 1313.04
     833 1315.81  875.011310.989   951.8 1309.71   956.7 1309.87  962.721312.986
   994.6 1348.07  1018.4 1371.47  1037.6 1387.61    1066 1406.99    1081 1410.96
  1094.6 1421.33  1121.5 1436.05  1207.3 1471.29  1242.2 1483.73  1336.3 1508.24
#Mann= 8 ,-1 , 0
       0    .055       0   35.17      .1       0  164.53     .06       0
  370.36     .05       0  705.54    .025       0  795.23     .05       0
  875.01    .045       0  962.72      .1       0
Bank Sta=875.01,962.72
XS Rating Curve= 0 ,0
Exp/Cntr=0.3,0.1

Type RM Length L Ch R = 1 ,9616    ,302.8,300,300.8
XS GIS Cut Line= 3
2451029.86403185701786.9274652152451776.62500551701240.342928454
2452110.07676643701002.645897299
#Sta/Elev= 30
       0 1526.14   142.3 1429.01   184.5 1396.21   241.1 1347.88     264 1324.48
     271 1319.43   303.5 1319.86   335.5 1317.11   392.8 1319.91   457.1  1320.8
   550.2 1316.75   714.9 1314.95   738.3 1318.96   779.3 1312.71   804.1 1311.74
   833.5  1313.1  869.581310.968   880.5 1309.15   952.6 1308.96   961.21310.698
   991.9 1313.13  1011.5 1330.59  1039.8 1352.08  1070.5 1373.47  1093.3  1384.8
  1137.3 1401.56  1180.4 1413.99  1200.4 1422.93  1272.1  1449.7  1334.9  1467.9
#Mann= 7 ,-1 , 0
       0      .1       0  230.27     .06       0  341.73     .05       0
  787.55    .025       0  869.58    .045       0   961.2    .055       0
 1009.93      .1       0
Bank Sta=869.58,961.2
XS Rating Curve= 0 ,0
Exp/Cntr=0.3,0.1

Type RM Length L Ch R = 1 ,9316    ,366.1,373,377.8
XS GIS Cut Line= 3
2451328.63147894701994.8922723832451959.41925937701477.806692377
2452302.10820651701224.030625135
#Sta/Elev= 30
       0 1474.58    18.2 1463.81    28.6 1452.64    54.5 1433.61     155 1353.82
   189.3 1321.33   227.1 1321.26   245.9 1316.69   333.8 1317.71   422.7 1314.39
   613.1 1313.48   652.4 1315.03   675.1    1320   706.4 1313.01   757.9 1312.57
  767.661309.493   788.8 1305.69   845.8 1305.91  875.42 1309.26   880.2 1311.04
   894.4  1322.9   920.2 1340.88   954.5 1361.75   974.5 1371.61  1028.8 1394.24
  1089.4 1413.47  1103.2 1419.36  1120.4 1421.58  1154.7 1432.37  1242.1 1451.53
#Mann= 5 ,-1 , 0
       0      .1       0  164.39     .06       0  279.23     .05       0
  767.66    .045       0  875.42      .1       0
#XS Ineff= 2 , 0
          216.81 1322.37
Permanent Ineff=
       F       F
Bank Sta=767.66,875.42
XS Rating Curve= 0 ,0
Exp/Cntr=0.3,0.1

Type RM Length L Ch R = 1 ,8943    ,395.6,434.2,470.1
XS GIS Cut Line= 2
2451520.64454636702167.3873342132452561.98990461701548.678269789
#Sta/Elev= 30
       0 1426.22    32.3 1404.87    74.9 1370.48   100.2 1348.28   121.6 1324.55
   127.4 1321.76   157.6 1323.68   181.1 1320.25   203.3 1311.52   275.1 1309.73
   353.4 1310.33   449.1 1314.08   625.9 1314.99   635.3 1315.76   653.8  1320.8
   670.3 1316.01   709.7 1313.58  735.561307.762   760.6 1303.78   818.5 1303.86
  831.511307.368   839.5 1321.34   844.6  1327.2   862.9 1337.54   891.1 1359.12
   948.5 1383.16   994.2  1393.7  1081.7 1406.51  1114.5 1412.96  1211.3 1436.35
#Mann= 6 ,-1 , 0
       0      .1       0   85.51     .06       0  192.26     .05       0
     726      .1       0  735.56    .045       0  831.51      .1       0
Bank Sta=735.56,831.51
XS Rating Curve= 0 ,0
Exp/Cntr=0.3,0.1

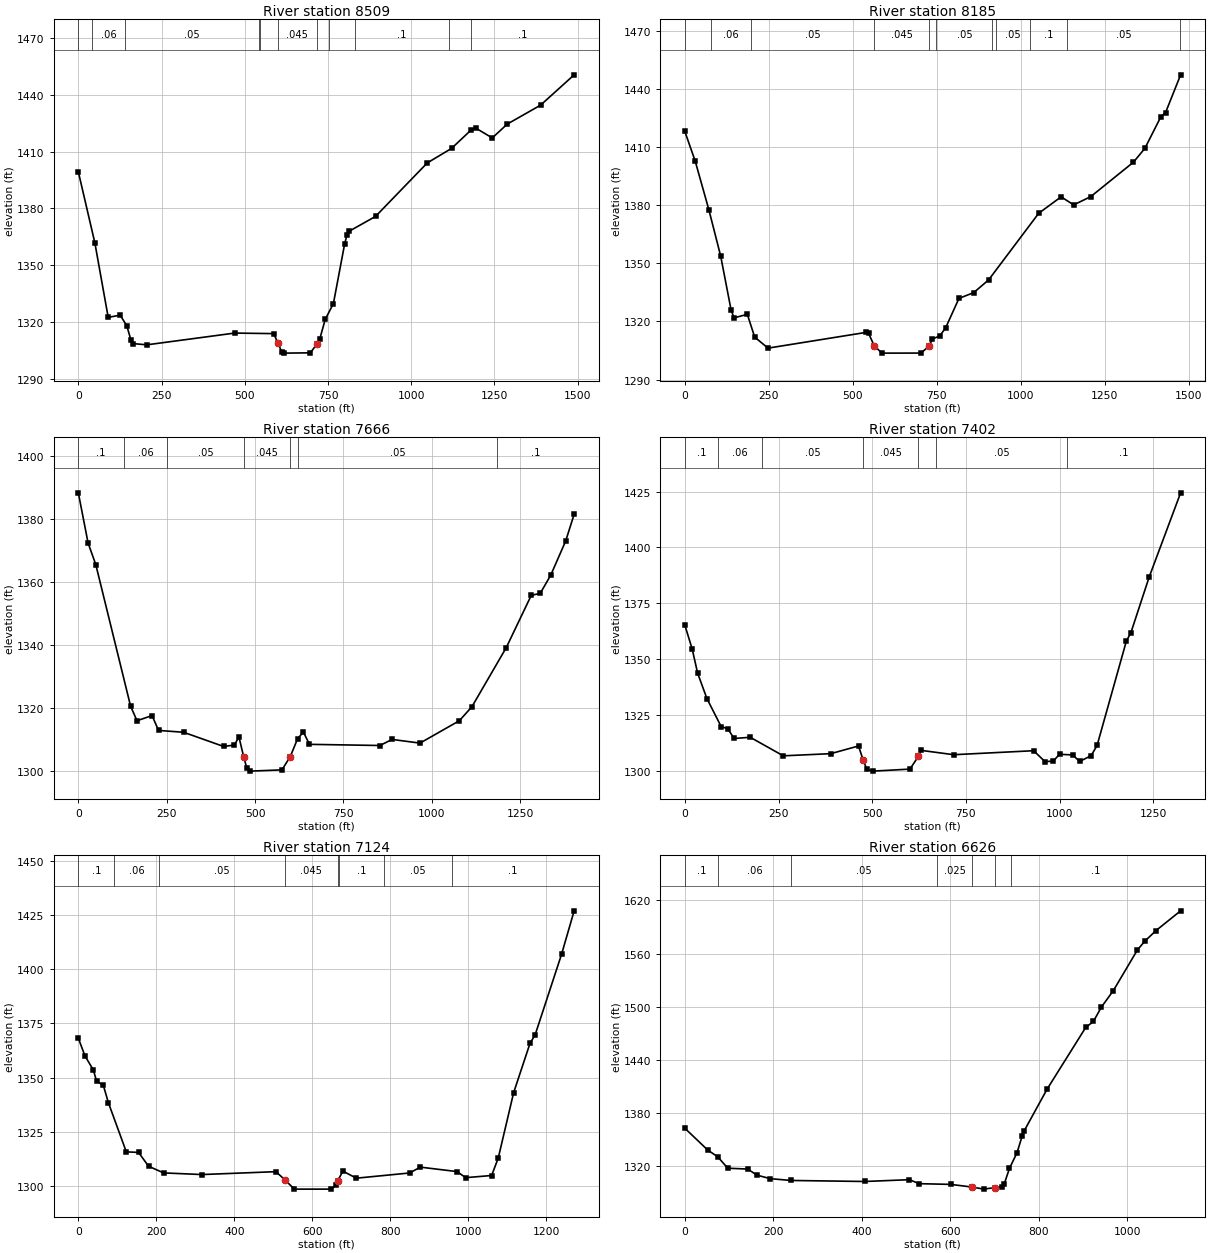
Type RM Length L Ch R = 1 ,8509    ,307.1,323.7,342.8
XS GIS Cut Line= 3
2451561.09262818702169.2328029572452097.35697562702158.342404798
2453031.96337411702344.866966128
#Sta/Elev= 30
       0 1399.31    49.7 1361.77    89.7 1322.53   125.7 1323.68   145.7 1318.06
   157.7 1310.75   165.7 1308.67   205.7 1308.04   469.7 1314.24   586.7 1313.95
  600.181308.851   611.2 1304.12     619 1303.66   696.9 1303.82  715.821308.247
   725.4 1311.22   741.7 1321.48   766.2  1329.8   799.8 1361.11     807 1366.06
   813.4 1367.95   892.7 1375.77  1048.1 1403.99  1121.1 1411.66  1179.5 1421.31
  1194.5 1422.29  1243.4 1417.18  1288.3 1424.47  1388.5 1434.47  1489.4 1450.47
#Mann= 11 ,-1 , 0
       0      .1       0   40.32     .06       0  140.62     .05       0
  542.14      .1       0  545.98     .05       0  600.18    .045       0
  715.82      .1       0  754.19      .1       0  829.59      .1       0
  1113.2    .055       0  1178.3      .1       0
Bank Sta=600.18,715.82
XS Rating Curve= 0 ,0
Exp/Cntr=0.3,0.1

Type RM Length L Ch R = 1 ,8185    ,518.7,519,517.2
XS GIS Cut Line= 3
 2451545.8013202702222.4866334652452398.92953518702616.491094798
2452909.36092901 702780.98650071
#Sta/Elev= 30
       0 1418.11    31.2 1402.62    71.5 1377.74   106.8 1353.76   137.6  1326.1
   146.4 1321.84   186.1 1323.69   208.1 1311.91   247.8 1306.24   538.6 1314.33
   547.4 1313.79  563.83 1307.43     587 1303.66   703.3 1303.69  727.781307.423
   736.8 1310.93   758.9 1312.54   776.5 1316.71   816.1 1331.89   860.2 1334.91
   904.3 1341.42  1053.5 1375.82  1120.2 1384.32  1157.6 1380.16  1208.5 1384.43
  1335.6  1402.2  1369.8  1409.4    1417 1425.58  1431.2 1427.82    1476 1447.28
#Mann= 11 ,-1 , 0
       0      .1       0   76.64     .06       0  196.43     .05       0
  563.83    .045       0  727.78    .025       0   749.1     .05       0
  915.18      .1       0  925.28     .05       0 1028.41      .1       0
 1139.06     .05       0 1474.54      .1       0
Bank Sta=563.83,727.78
XS Rating Curve= 0 ,0
Exp/Cntr=0.3,0.1

Type RM Length L Ch R = 1 ,7666    ,265.9,264.2,264.5
XS GIS Cut Line= 3
2451381.34692469702730.314357966 2451862.3833642702937.131529629
2452674.85647678703272.058681294
#Sta/Elev= 30
       0 1388.43    27.6 1372.48    49.4 1365.62   147.7  1320.7   165.9 1316.03
   208.6 1317.67   226.8 1312.95   297.6 1312.37   410.8 1307.86   441.3  1308.3
   454.3 1310.89  467.651304.563   476.1 1301.13   485.6 1300.02   575.9 1300.42
  599.511304.646   620.2 1310.32   636.5 1312.43   653.8 1308.53     853 1308.16
   887.4 1310.09   966.4 1308.92  1077.8 1316.04  1113.5 1320.53  1210.4 1339.27
  1281.1 1355.87  1306.5  1356.5  1336.4 1362.33  1378.4 1373.12  1402.4 1381.63
#Mann= 7 ,-1 , 0
       0      .1       0  128.62     .06       0  250.84     .05       0
  467.65    .045       0  599.51    .055       0  620.34     .05       0
 1184.69      .1       0
Bank Sta=467.65,599.51
XS Rating Curve= 0 ,0
Exp/Cntr=0.3,0.1

Type RM Length L Ch R = 1 ,7402    ,279,278.4,276.8
XS GIS Cut Line= 3
2451252.29370511702980.8686468752451739.56274369703171.739984289
 2452476.1301682703482.423418045
#Sta/Elev= 30
       0 1365.28    19.8 1354.45    34.3 1343.67      59 1332.33    97.1 1319.74
   114.6 1318.85   131.5 1314.45   174.5    1315   262.7 1306.69   389.3 1307.66
   463.4  1311.1  475.381305.033     485 1300.84     501 1299.84   600.6 1300.74
  623.251306.488     631 1309.12   717.5 1307.19   930.5 1308.98   960.9  1304.1
   982.6 1304.33    1000 1307.38  1034.7 1307.09  1053.3 1304.19  1083.9 1306.75
  1099.8 1311.33    1178  1358.1  1190.1 1361.86  1238.7  1386.7  1322.7 1424.45
#Mann= 7 ,-1 , 0
       0      .1       0   89.88     .06       0  205.27     .05       0
  475.38    .045       0  623.25    .055       0  669.07     .05       0
  1020.7      .1       0
Bank Sta=475.38,623.25
XS Rating Curve= 0 ,0
Exp/Cntr=0.3,0.1

Type RM Length L Ch R = 1 ,7124    ,491.2,497.6,513.8
XS GIS Cut Line= 3
 2451087.0384582703215.2129944562451631.51341912703428.656137124
2452272.48949936703674.477823958
#Sta/Elev= 30
       0 1368.22    16.9  1360.1    38.4 1353.57    46.9 1348.39    64.1 1346.49
      77 1338.49     123  1315.8   154.4 1315.55   180.1 1309.17   218.7  1306.1
   316.9 1305.34   506.7 1306.67  529.121302.995   553.9 1298.62   648.3 1298.62
   661.1  1300.5  664.64 1302.27   678.2 1306.93   712.9 1303.67   849.2 1306.06
     877 1308.76   970.9 1306.71   993.2 1303.91  1059.7  1304.9  1076.7 1312.98
  1116.1 1343.08  1158.1 1365.84  1171.2 1369.74    1239  1406.9  1271.3 1426.94
#Mann= 8 ,-1 , 0
       0      .1       0   92.22     .06       0  207.62     .05       0
  529.12    .045       0  664.64    .025       0  668.85      .1       0
  783.75     .05       0  957.23      .1       0
Bank Sta=529.12,664.64
XS Rating Curve= 0 ,0
Exp/Cntr=0.3,0.1

Type RM Length L Ch R = 1 ,6626    ,311.5,309.8,310.5
XS GIS Cut Line= 2
2450953.53249159703418.8149494682451761.43474719704194.950864375
#Sta/Elev= 30
       0 1363.07    51.8 1338.42    74.5 1330.79    97.1 1317.92   142.4 1316.97
   162.5 1310.18   193.3 1306.12   240.2 1304.11   406.6 1302.96   507.3 1304.98
   529.9 1300.48   600.7 1299.69  649.861296.621   675.6 1294.34  701.691296.167
   716.1 1296.99   721.8 1300.32   733.6 1317.76   750.7 1335.49   762.2 1354.14
   767.1 1360.31   818.5 1407.04   905.8 1476.66   923.2 1483.44   941.2 1499.62
   968.4 1518.36  1022.3 1563.82  1038.9 1573.79  1064.6 1585.95  1120.3 1608.26
#Mann= 7 ,-1 , 0
       0      .1       0   75.05     .06       0   240.3     .05       0
  570.81    .025       0  649.86    .045       0  701.69    .025       0
  736.06      .1       0
Bank Sta=649.86,701.69
XS Rating Curve= 0 ,0
Exp/Cntr=0.3,0.1

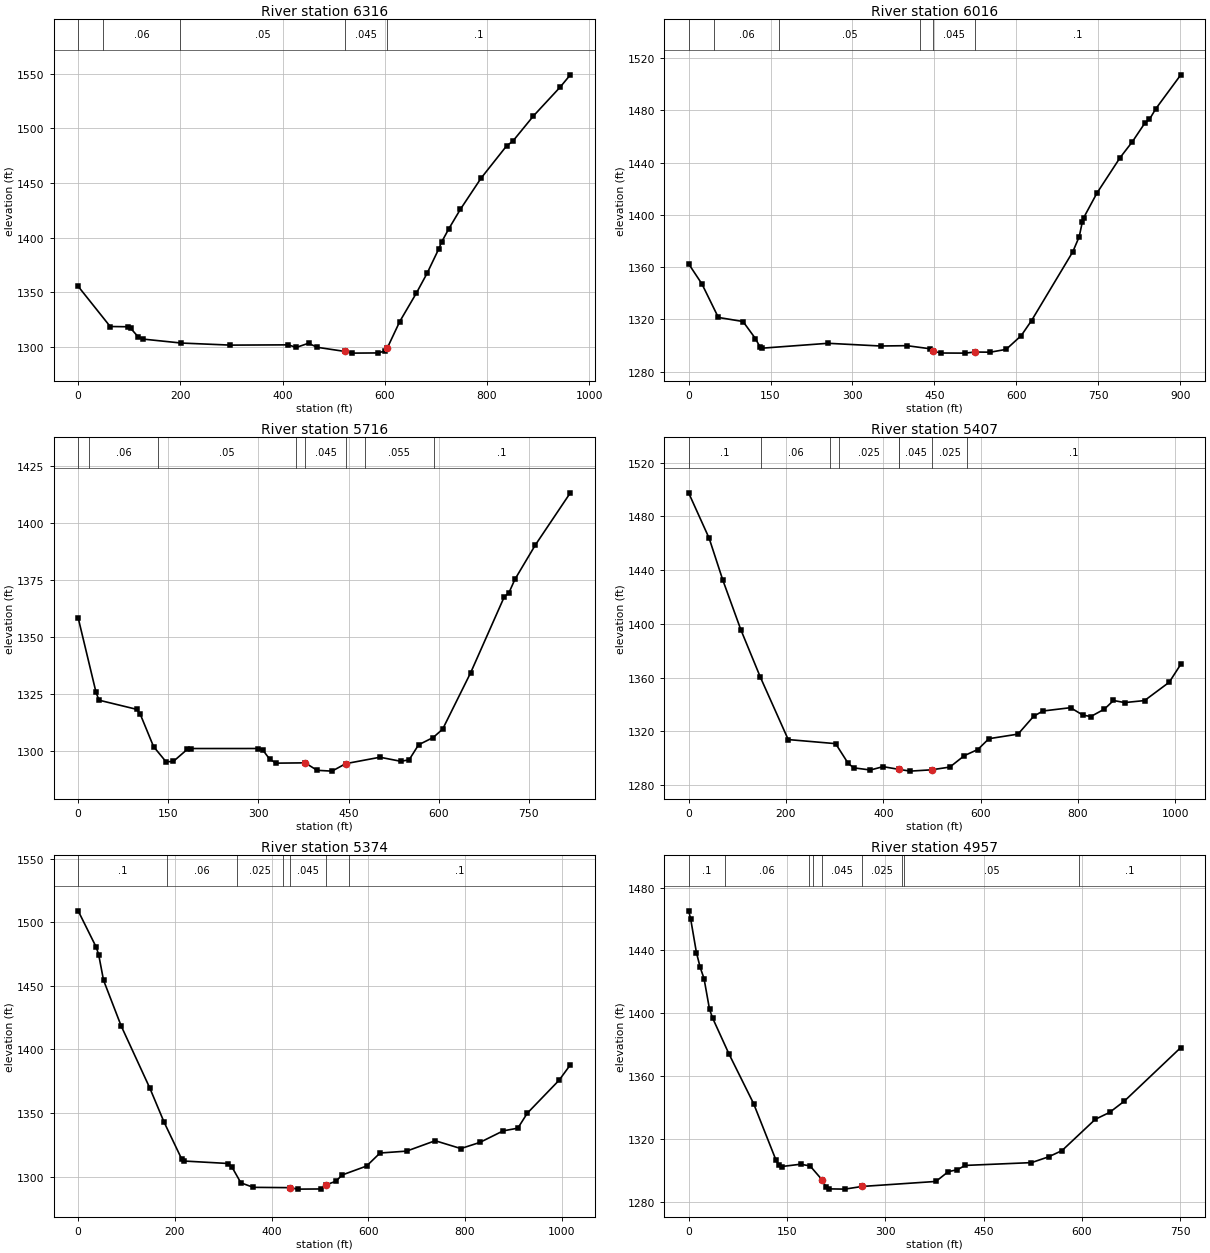
Type RM Length L Ch R = 1 ,6316    ,300.5,300,300.7
XS GIS Cut Line= 3
2450811.33330095703676.9712572992451194.66717994704076.427151293
 2451476.4235062704373.586333871
#Sta/Elev= 30
       0  1355.4    62.7 1318.61    97.4 1318.38   102.8 1316.95   116.9 1309.45
   126.2 1307.14   201.8 1303.48     298 1301.58   411.2 1301.82   426.7 1299.47
   450.8 1303.28   467.7 1299.59  521.771295.808   535.6 1294.25   586.6 1294.43
   600.3 1296.17  605.321299.322   629.3 1323.18   661.8 1349.17   682.8 1367.31
   705.9 1389.91     711 1395.75   725.2 1407.97   747.8 1425.78   788.5 1454.43
   838.6 1484.05   850.2 1488.03   890.9 1511.33   943.1 1537.67   963.1 1548.96
#Mann= 5 ,-1 , 0
       0      .1       0   49.56     .06       0  199.24     .05       0
  521.77    .045       0  605.32      .1       0
Bank Sta=521.77,605.32
XS Rating Curve= 0 ,0
Exp/Cntr=0.3,0.1

Type RM Length L Ch R = 1 ,6016    ,298,300,301.7
XS GIS Cut Line= 3
2450635.36875784703929.3742958012450976.96814027704282.842092797
 2451258.7247946704580.000947297
#Sta/Elev= 30
       0 1362.55    24.4 1347.16    54.4 1321.55    99.6 1318.43   122.3 1305.39
   130.8 1298.85   133.6    1298   255.2 1301.77   351.4  1299.7   399.5 1299.96
   441.6 1297.62   447.6  1295.9   461.7 1294.34   505.8 1294.25  524.161295.094
   552.3 1294.97   581.3 1297.11   608.9 1307.63   627.9 1319.19   703.4 1371.81
   715.1 1383.34   720.9  1394.8   723.1 1397.69   747.5 1416.64   789.9 1443.77
   812.6 1456.07   835.2 1470.18   843.7  1473.1   855.4 1481.23   901.1 1507.14
#Mann= 6 ,-1 , 0
       0      .1       0   46.95     .06       0  166.31     .05       0
  424.31    .025       0   447.6    .045       0  524.16      .1       0
Bank Sta=447.6,524.16
XS Rating Curve= 0 ,0
Exp/Cntr=0.3,0.1

Type RM Length L Ch R = 1 ,5716    ,315.2,309.1,299.8
XS GIS Cut Line= 3
2450487.31656054704173.3583878732450754.30290321  704483.8554703
2451021.28957394704794.352880791
#Sta/Elev= 30
       0 1358.26    29.8 1325.49    34.7 1322.11    97.3  1318.1   103.4 1315.92
   125.5 1301.75   146.4 1295.04   158.6 1295.29   181.4 1300.51   187.9  1300.9
   299.7 1300.91     307 1300.33   318.5 1296.31   329.1 1294.49  377.69 1294.62
   397.7 1291.34   422.4 1290.99  445.281294.269   502.2 1297.08   536.8 1295.31
   550.7 1295.93   566.5 1302.55   590.7 1305.72   606.5 1309.39   653.1 1334.14
   708.9 1367.34   716.9 1369.28   726.8 1375.12   760.8 1390.19     819 1413.06
#Mann= 8 ,-1 , 0
       0      .1       0   17.76     .06       0  132.61     .05       0
   362.3    .025       0  377.69    .045       0  445.28      .1       0
  477.15    .055       0     592      .1       0
Bank Sta=377.69,445.28
XS Rating Curve= 0 ,0
Exp/Cntr=0.5,0.3

Type RM Length L Ch R = 1 ,5407    ,31.4,32.9,33.5
XS GIS Cut Line= 3
2450148.62038752704415.2158437972450668.63017428704793.435231715
2450953.98065344705025.927876964
#Sta/Elev= 30
       0  1497.6    42.2 1463.73      70 1432.86   107.2 1395.68   147.3 1360.32
   204.6 1313.79     302 1310.75   327.7  1296.1     339 1292.73   373.6 1291.12
   399.3 1293.61  432.711291.546   455.1 1290.28  499.231291.264   536.7 1293.31
   566.5 1301.84     594 1306.36   616.9 1314.44   676.7 1317.85   708.6 1331.07
   727.6 1335.06   784.6 1337.54     810 1331.98   826.3 1330.97   854.3 1336.52
   872.8  1342.9   895.7 1341.35   936.6 1342.84   987.3  1356.5  1011.1 1369.89
#Mann= 8 ,-1 , 0
       0      .1       0  149.48     .06       0  290.52     .05       0
  309.42    .025       0  431.56     .06       0  432.71    .045       0
  499.23    .025       0   572.6      .1       0
#XS Ineff= 2 ,-1
       0     422  1291.2     510 1011.08  1291.2
Permanent Ineff=
       F       F
Bank Sta=432.71,499.23
XS Rating Curve= 0 ,0
Exp/Cntr=0.5,0.3

Type RM Length L Ch R = 1 ,5374    ,422.1,417,421.9
XS GIS Cut Line= 3
2450128.86091262 704429.222049372450766.98791718704912.223051876
2450939.34485593705045.225410551
#Sta/Elev= 30
       0 1508.96    37.5 1480.29    42.5 1474.42    52.5 1454.44    88.9 1418.59
   148.2  1369.7   177.9 1342.76   213.8 1314.21   218.1 1312.38   310.9 1310.41
   318.4 1307.43   336.6 1295.22   362.3 1291.68  437.981291.435   453.9 1290.28
   502.2 1290.41  513.631293.765     533 1296.47   546.2 1301.42   596.5 1308.41
   624.4 1318.66   679.3 1320.14   738.5 1328.32   791.5 1322.16   830.9 1326.98
     879 1336.05   909.4 1338.17   929.1 1350.01   994.6 1375.78    1018 1387.94
#Mann= 7 ,-1 , 0
       0      .1       0  183.93     .06       0  327.76    .025       0
  424.33      .1       0  437.98    .045       0  513.63    .025       0
  560.04      .1       0
Bank Sta=437.98,513.63
XS Rating Curve= 0 ,0
Exp/Cntr=0.5,0.3

Type RM Length L Ch R = 1 ,4957    ,437.6,440.9,444
XS GIS Cut Line= 2
2449980.09972718704832.9863337132450606.32025951705246.776516631
#Sta/Elev= 30
       0 1465.23     3.2 1459.88    11.9 1438.67    17.6 1429.28    23.5 1422.13
    31.9  1402.5    36.7 1396.89    61.5 1374.18    99.1 1342.55   133.2 1306.62
   137.4  1303.4   141.9 1302.48   170.7 1303.96   185.2 1302.88  203.621293.996
   209.3 1289.66   213.9 1288.27   238.1 1288.11  264.711289.817   377.1    1293
   395.9  1299.2   409.8 1300.49   421.9  1303.2   522.9 1304.98   548.9 1308.65
   569.4 1312.63   620.2 1332.55     642 1336.93   664.4 1344.09   750.6 1378.22
#Mann= 9 ,-1 , 0
       0      .1       0    55.1     .06       0   184.2    .055       0
  190.16    .025       0  203.62    .045       0  264.71    .025       0
  325.22      .1       0  329.18     .05       0  595.34      .1       0
Bank Sta=203.62,264.71
XS Rating Curve= 0 ,0
Exp/Cntr=0.3,0.1