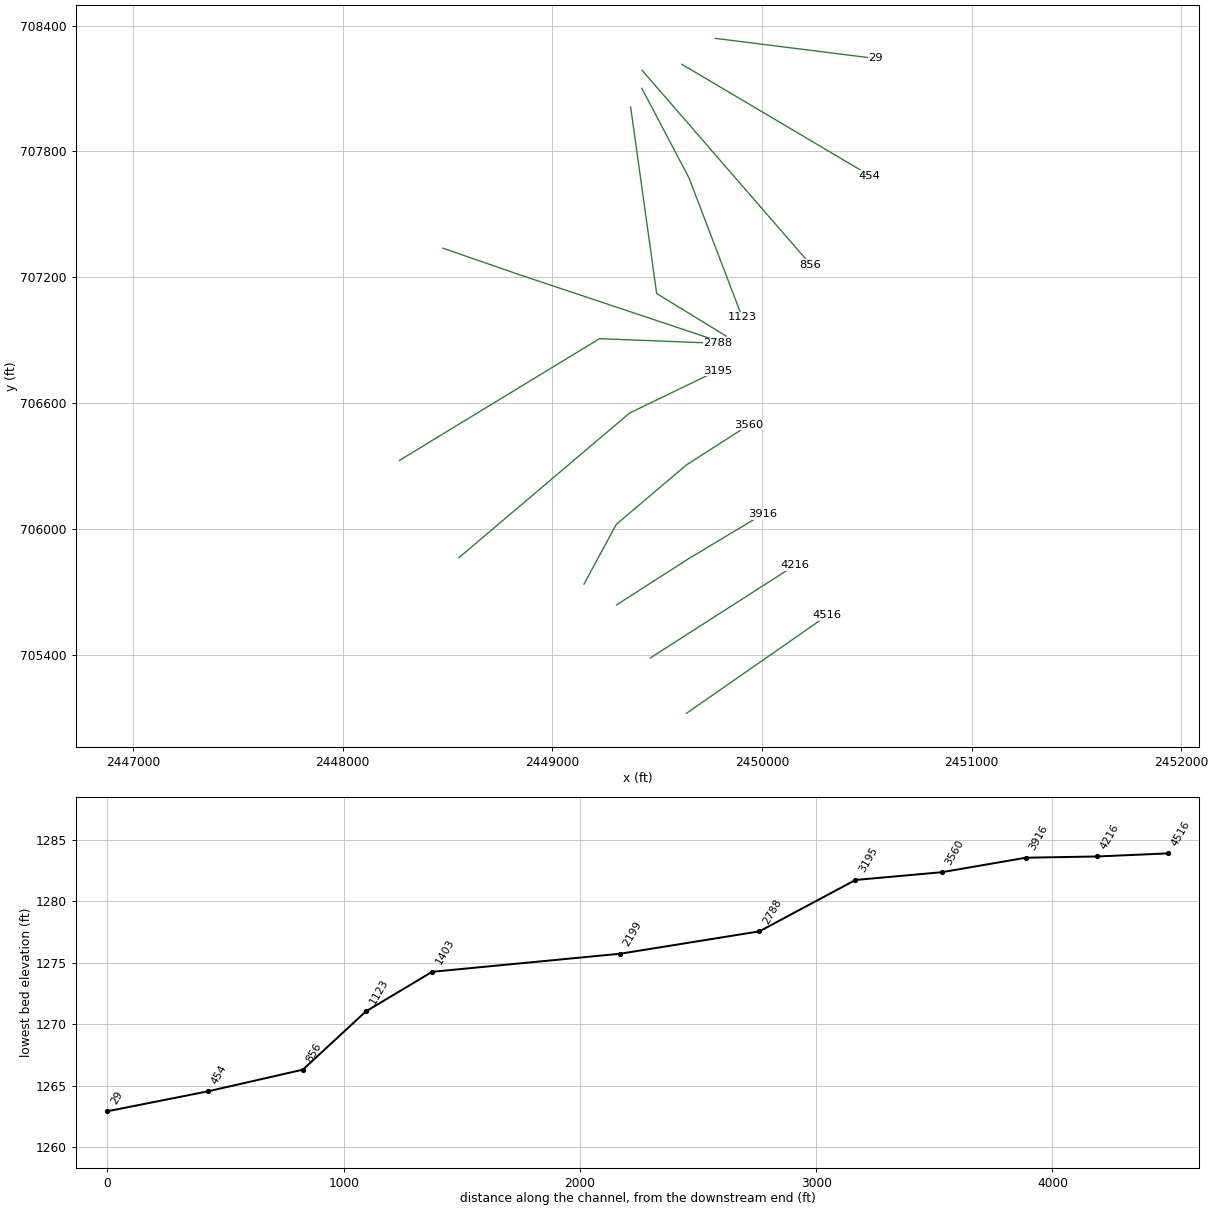
HEC-RAS study NFSBPOTOMC.prj: NFSBPOTOMC

--- NFSBPOTOMC.g01 (geometry) --- (continued)

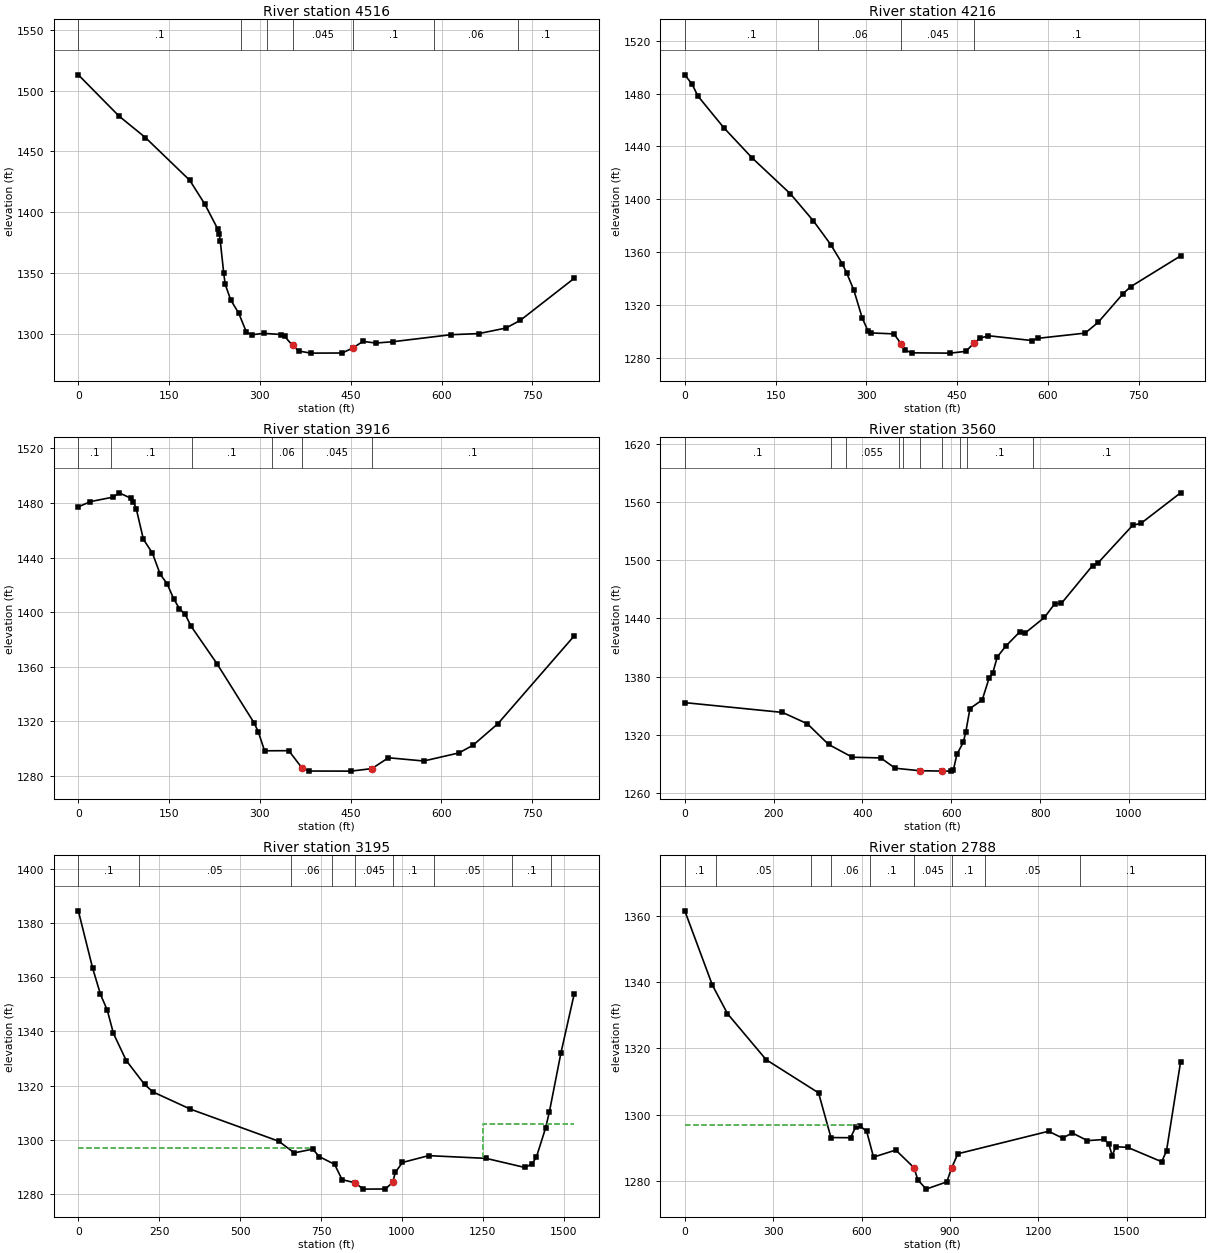
Type RM Length L Ch R = 1 ,4516    ,302.1,300,299.3
XS GIS Cut Line= 3
2449639.60762602705119.6130570472449975.76804295705353.464623466
2450311.92845985705587.316189885
#Sta/Elev= 30
       0 1513.01    67.2 1479.05   110.8 1461.36   184.1 1426.15   208.9 1406.57
   229.9 1386.48   232.8 1382.08   234.5 1375.94   240.2 1349.58   242.6 1340.61
   251.7 1327.69   264.9 1316.81   277.6 1301.24   286.4 1298.96   305.9 1300.22
   335.2 1299.24   340.8 1297.68  353.841290.234   364.4 1285.62   383.9 1283.91
   435.7 1284.02  453.231288.063   470.1 1293.59   491.1 1292.22     519 1293.26
   615.1 1299.06   661.6    1300   706.2 1304.54   729.9 1310.84     819 1345.46
#Mann= 7 ,-1 , 0
       0      .1       0  268.87     .06       0  311.37    .055       0
  353.84    .045       0  453.23      .1       0  587.65     .06       0
   725.8      .1       0
Bank Sta=353.84,453.23
XS Rating Curve= 0 ,0
Exp/Cntr=0.3,0.1

Type RM Length L Ch R = 1 ,4216    ,300.3,300,297.9
XS GIS Cut Line= 3
2449467.84090918705384.263446376 2449812.6276212705605.198700041
2450157.41466129705826.133625627
#Sta/Elev= 30
       0 1494.16    12.3 1486.91    21.4 1478.26    64.2 1454.26   111.1 1431.36
   174.5 1404.11   212.5 1383.63     241 1365.79     260 1351.43   267.5 1344.17
   279.1 1331.45   293.2 1310.08   302.7 1300.39   307.5 1298.94   345.5 1298.21
  357.821290.369   364.5 1285.89   374.6 1283.88   438.3 1283.66   464.3 1285.01
  477.091290.981     488    1295   501.6 1296.81   573.5 1293.18   583.1 1294.85
   661.3  1298.8   682.8 1306.96     724 1328.68   736.5 1333.91     819 1357.21
#Mann= 4 ,-1 , 0
       0      .1       0  219.73     .06       0  357.82    .045       0
  477.09      .1       0
Bank Sta=357.82,477.09
XS Rating Curve= 0 ,0
Exp/Cntr=0.3,0.1

Type RM Length L Ch R = 1 ,3916    ,354,355.9,361.4
XS GIS Cut Line= 3
2449306.01642969 705636.875802042449650.77033335705857.789730296
 2450002.1587382706068.494689465
#Sta/Elev= 30
       0  1477.2    19.9 1481.04    57.9 1484.38    67.4 1487.48    86.4 1483.59
    91.1 1481.02    95.9 1475.39   107.5 1453.42   122.4 1443.29   135.2 1427.88
   146.8 1420.75   157.6 1409.76   167.1  1402.6   176.6 1398.36   186.1 1389.84
   228.9 1362.39   290.7 1318.67   297.3 1312.37   307.7 1298.46   347.7 1298.54
  369.711285.775   380.9 1283.63   450.5 1283.56  485.041285.408   512.3 1293.36
   570.6 1290.98   628.9 1296.91     652 1302.52   693.1 1318.26   819.2 1382.61
#Mann= 6 ,-1 , 0
       0      .1       0   53.76      .1       0   187.1      .1       0
  320.45     .06       0  369.71    .045       0  485.04      .1       0
Bank Sta=369.71,485.04
XS Rating Curve= 0 ,0
Exp/Cntr=0.3,0.1

Type RM Length L Ch R = 1 ,3560    ,366.4,365.4,367.3
XS GIS Cut Line= 4
2449151.19882593705736.4044743782449305.05022427706021.038091466
2449639.06924129706304.2350316352449937.66936585706495.703808799
#Sta/Elev= 30
       0 1353.07   219.9 1342.97     276 1331.22   323.6 1309.95   377.2 1296.72
   441.1 1296.01   473.6 1285.37  528.991282.792  579.251282.438   598.5 1282.38
   604.8 1283.85   612.7 1299.93   626.9 1312.05   632.6 1322.77   641.9 1346.91
   669.5 1355.84   685.2  1378.6   692.9 1383.15   703.5 1400.24   722.3 1411.24
   754.6  1426.3   766.1 1424.88   809.5 1440.94   833.1 1455.29   847.9 1455.55
   917.9 1494.49   931.1 1497.68  1008.2 1536.05  1027.2 1538.18  1116.2 1569.59
#Mann= 10 ,-1 , 0
       0      .1       0   328.4     .06       0  361.94    .055       0
  481.33      .1       0  490.94    .025       0  528.99    .045       0
  579.25    .025       0  619.95    .055       0  634.26      .1       0
   783.9      .1       0
Bank Sta=528.99,579.25
XS Rating Curve= 0 ,0
Exp/Cntr=0.3,0.1

Type RM Length L Ch R = 1 ,3195    ,416.8,406.8,397
XS GIS Cut Line= 3
2448554.47823462705862.2181991342449368.97430903706552.516687289
2449787.64473152 706754.60322538
#Sta/Elev= 30
       0 1384.56    44.3 1363.35    68.5 1353.69    89.5 1347.85   108.5 1339.26
   148.2 1329.24   204.8 1320.41   231.1 1317.63   346.4  1311.3   619.4 1299.45
   667.6 1295.15   724.4 1296.53   744.9 1293.75   792.1  1290.9   815.2 1285.26
  855.731284.077   880.5 1281.75   949.4 1281.81   971.71284.251   979.8 1287.93
  1001.8  1291.6  1082.8 1294.12  1260.6 1293.11  1380.5 1289.74  1402.8  1291.1
  1416.1 1293.66  1444.2  1304.3  1456.1 1310.35  1491.6 1331.99  1532.6 1353.77
#Mann= 9 ,-1 , 0
       0      .1       0  188.96     .05       0  656.44     .06       0
  785.47      .1       0  855.73    .045       0   971.7      .1       0
  1098.3     .05       0 1340.71      .1       0 1461.91      .1       0
#XS Ineff= 2 ,-1
       0  713.62 1297.04 1250.88 1532.56 1305.93
Permanent Ineff=
       F       F
Bank Sta=855.73,971.7
XS Rating Curve= 0 ,0
Exp/Cntr=0.3,0.1

Type RM Length L Ch R = 1 ,2788    ,619.8,589.5,531.3
XS GIS Cut Line= 3
 2448270.9181062706326.4554596252449225.22131568706907.015322134
2449790.75364921706884.877899215
#Sta/Elev= 30
       0 1361.46    93.4 1339.11   144.9 1330.45     276  1316.6     454 1306.59
   496.1 1293.11   562.7 1293.07   580.4 1296.38     594 1296.62   617.3    1295
   640.6 1287.22   716.2 1289.35  777.931284.023   791.1 1280.36   819.2 1277.57
   889.4 1279.76  905.591283.925   926.8 1288.23  1234.6 1295.01  1282.7 1292.93
  1314.7 1294.53  1366.7 1292.19  1422.9 1292.53  1438.8 1291.25  1450.8 1287.69
  1462.8 1290.35  1502.8 1290.17  1618.9 1285.82  1635.1 1289.13    1683 1316.01
#Mann= 9 ,-1 , 0
       0      .1       0  104.83     .05       0  428.32      .1       0
  496.78     .06       0  627.43      .1       0  777.93    .045       0
  905.59      .1       0 1019.39     .05       0 1342.42      .1       0
#XS Ineff= 2 , 0
          588.13 1296.78
Permanent Ineff=
       F       F
Bank Sta=777.93,905.59
XS Rating Curve= 0 ,0
Exp/Cntr=0.3,0.1

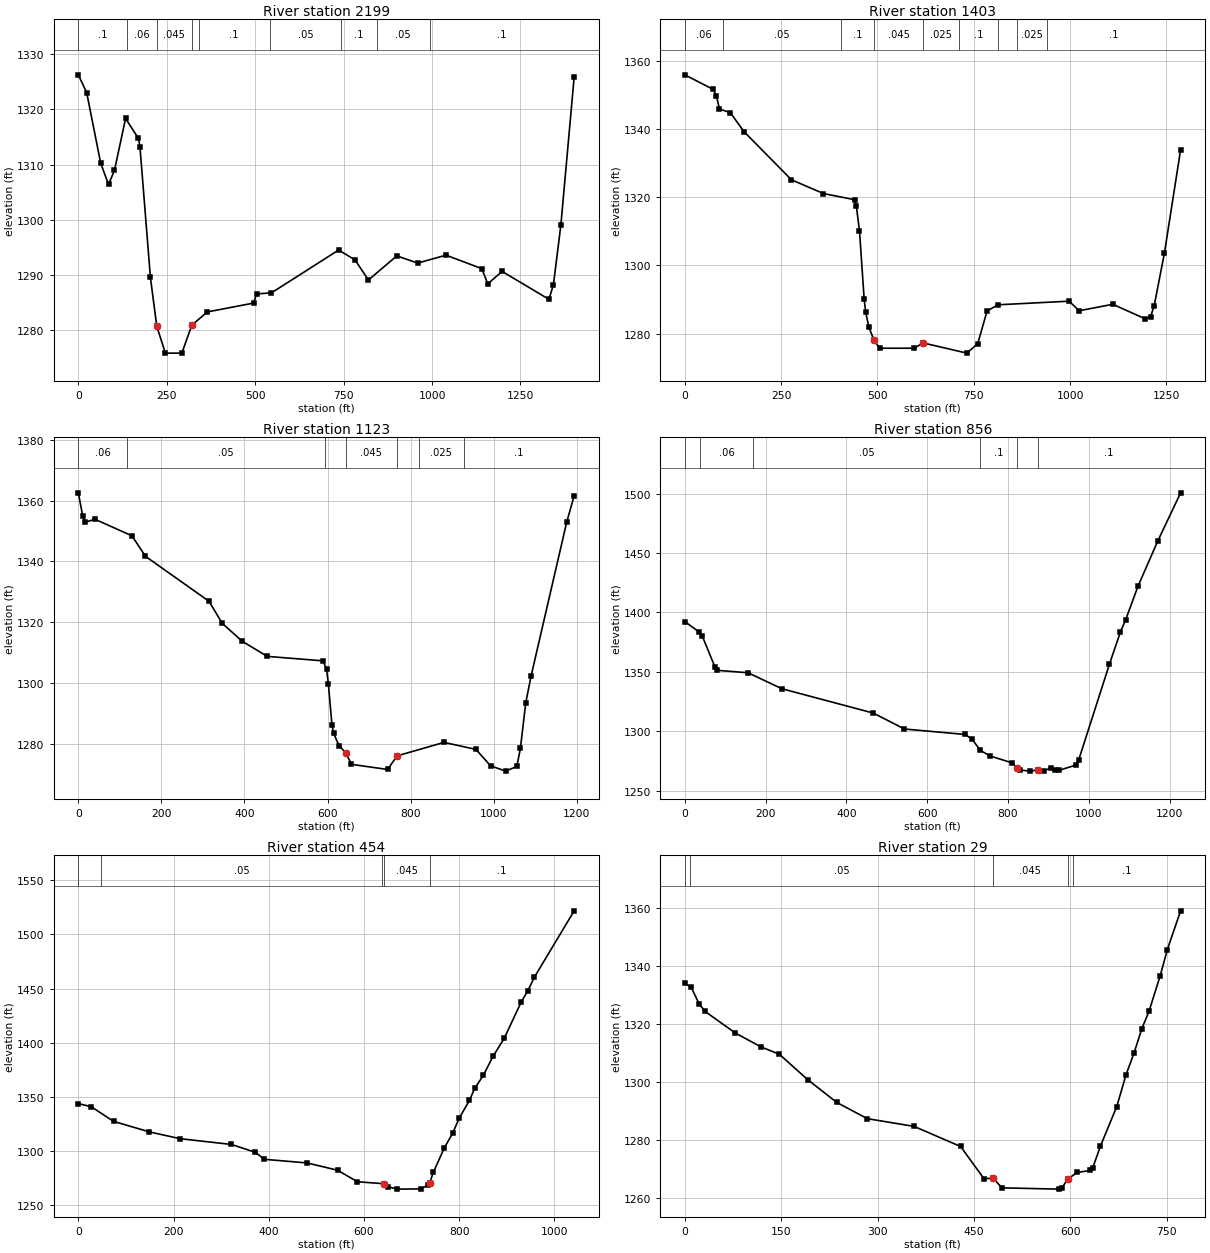
Type RM Length L Ch R = 1 ,2199    ,839.6,795.6,728
XS GIS Cut Line= 3
2448478.15259987707338.603697792 2448844.8280476707211.685972631
2449806.29233202706890.337533966
#Sta/Elev= 30
       0 1326.29    23.6 1323.07    63.1 1310.27    85.3 1306.38   102.2 1308.95
   133.6 1318.36     170 1314.74   174.2 1313.24   203.8 1289.49  221.731280.635
   246.1 1275.75   292.7 1275.75  320.711280.823   364.7 1283.23   495.5 1284.84
   503.9  1286.5   546.1  1286.7   735.9 1294.47   782.3 1292.68   820.1 1289.03
   900.4 1293.41   959.4  1292.1  1039.5 1293.54  1140.8 1291.09  1157.6 1288.33
  1198.1 1290.59  1330.5 1285.52  1343.2 1288.18  1364.3 1299.05  1401.8 1325.88
#Mann= 9 ,-1 , 0
       0      .1       0  138.46     .06       0  221.73    .045       0
  320.71    .025       0  340.08      .1       0  541.43     .05       0
  742.69      .1       0  843.32     .05       0  993.09      .1       0
Bank Sta=221.73,320.71
XS Rating Curve= 0 ,0
Exp/Cntr=0.3,0.1

Type RM Length L Ch R = 1 ,1403    ,268,280.5,294.7
XS GIS Cut Line= 3
2449373.66229177708011.9783352912449497.82575735707122.373487204
2449829.26472703706919.356832877
#Sta/Elev= 30
       0 1355.93    73.8 1351.65    81.9 1349.81      90 1345.91   118.2 1344.82
   154.3 1339.18   276.9 1325.13   359.9  1321.1   441.3 1319.28   445.4 1317.31
   453.4 1310.14   465.6 1290.03   469.7 1286.22   477.7 1281.92  491.031278.053
   505.9 1275.72   594.8 1275.72  618.781277.268     732 1274.28   760.4 1277.08
   784.6 1286.66   812.9 1288.46   997.4 1289.52  1023.6 1286.71  1110.9 1288.61
  1194.8 1284.35  1208.9 1284.95  1218.3 1288.21  1244.7 1303.53  1286.9 1333.97
#Mann= 9 ,-1 , 0
       0     .06       0   99.78     .05       0  405.42      .1       0
  491.03    .045       0  618.78    .025       0  711.06      .1       0
  812.93     .05       0  861.28    .025       0  939.45      .1       0
Bank Sta=491.03,618.78
XS Rating Curve= 0 ,0
Exp/Cntr=0.3,0.1

Type RM Length L Ch R = 1 ,1123    ,262.5,266.8,275.5
XS GIS Cut Line= 3
 2449426.9154661708101.3895737982449652.60399112707672.681113631
2449905.50440395707010.007242128
#Sta/Elev= 30
       0 1362.54    10.6 1354.85    16.4 1352.89    40.2 1353.84   129.1 1348.41
   161.6 1341.67   314.7 1326.89   346.4 1319.66   394.6 1313.74   454.9 1308.78
   589.2 1307.31   597.7 1304.48     602 1299.81   610.6 1286.31   614.8 1283.43
   627.7 1279.46  643.881277.026   657.7 1273.29   744.7  1271.6  767.411276.071
   880.3  1280.5   957.4  1278.2   992.6  1272.8    1029 1271.06  1055.8 1272.61
  1064.4 1278.56  1077.2 1293.47  1090.1 1302.33  1175.7 1352.81  1193.8 1361.59
#Mann= 7 ,-1 , 0
       0     .06       0  117.72     .05       0  594.69      .1       0
  643.88    .045       0  767.41      .1       0  819.32    .025       0
  927.84      .1       0
Bank Sta=643.88,767.41
XS Rating Curve= 0 ,0
Exp/Cntr=0.3,0.1

Type RM Length L Ch R = 1 ,856     ,391.7,401.5,409.9
XS GIS Cut Line= 2
2449428.13363951708187.3575777112450232.24390793707260.096636966
#Sta/Elev= 30
       0 1392.23    34.5 1383.66      43 1380.19    74.7 1353.97      80 1351.17
   156.6 1349.13   240.4 1335.66   466.5  1315.2   543.8 1301.77   694.1 1297.18
   711.1 1293.23   731.3  1283.9     755 1279.16   810.3 1273.25  821.791269.261
   830.2 1267.19   855.7 1266.32  873.151267.409   889.3 1266.62   906.7 1269.01
   915.2 1267.04   925.9 1266.91   969.5 1271.58   975.3    1276  1051.3 1356.48
  1078.5 1383.59  1091.3 1393.71  1122.2 1422.21  1170.4  1459.7  1227.4 1500.58
#Mann= 6 ,-1 , 0
       0      .1       0   38.68     .06       0  168.06     .05       0
  731.13      .1       0  821.79    .045       0  873.15      .1       0
Bank Sta=821.79,873.15
XS Rating Curve= 0 ,0
Exp/Cntr=0.3,0.1

Type RM Length L Ch R = 1 ,454     ,402.9,425.5,444
XS GIS Cut Line= 2
2449618.24119893 708215.599319132450514.48940644707685.272295788
#Sta/Elev= 30
       0 1343.65    27.2 1340.72    73.9 1327.23   149.3 1317.46     214 1311.16
   321.3 1305.89   371.7 1298.63     391 1292.11   480.5 1288.78   544.4 1282.04
   586.2 1271.38  642.391269.521   651.3 1266.67   669.9 1264.56   719.2 1264.75
   734.9 1268.45  738.151270.625   745.5 1279.94   768.8 1302.77   786.4 1316.44
     800  1330.2   821.4 1346.52   832.5 1357.67   850.6 1369.78     871 1387.34
   894.4 1403.89   930.1 1437.45   944.1 1447.97     958  1460.6  1041.4 1521.87
#Mann= 5 ,-1 , 0
       0     .06       0   48.53     .05       0  637.96    .025       0
  642.39    .045       0  738.15      .1       0
Bank Sta=642.39,738.15
XS Rating Curve= 0 ,0
Exp/Cntr=0.3,0.1

Type RM Length L Ch R = 1 ,29      ,28.97,28.79,28.61
XS GIS Cut Line= 2
2449776.85144603 708339.699136542450542.38797268708243.518554628
#Sta/Elev= 30
       0    1334      10 1332.54    22.1 1326.96    31.1 1324.33    78.5 1316.82
   118.8    1312     147  1309.5   191.4 1300.69   236.4 1292.87   284.1 1287.25
   356.7 1284.59   429.2 1277.66   465.5 1266.57  479.721266.685   493.7 1263.38
   582.2 1262.94   586.5 1263.18  595.661266.376   610.7 1268.69   630.8 1269.38
   634.8 1270.24   646.9 1277.84   672.2 1291.42   686.5  1302.3   699.3 1310.05
   711.3 1318.35   722.3 1324.24   739.7 1336.47   750.9 1345.59   771.6 1358.97
#Mann= 5 ,-1 , 0
       0     .06       0     7.8     .05       0  479.72    .045       0
  595.66    .025       0  604.07      .1       0
Bank Sta=479.72,595.66
XS Rating Curve= 0 ,0
Exp/Cntr=0.3,0.1
LCMann Table=0

Chan Stop Cuts=-1
Use User Specified Reach Order=0
Composite Channel Slope=5